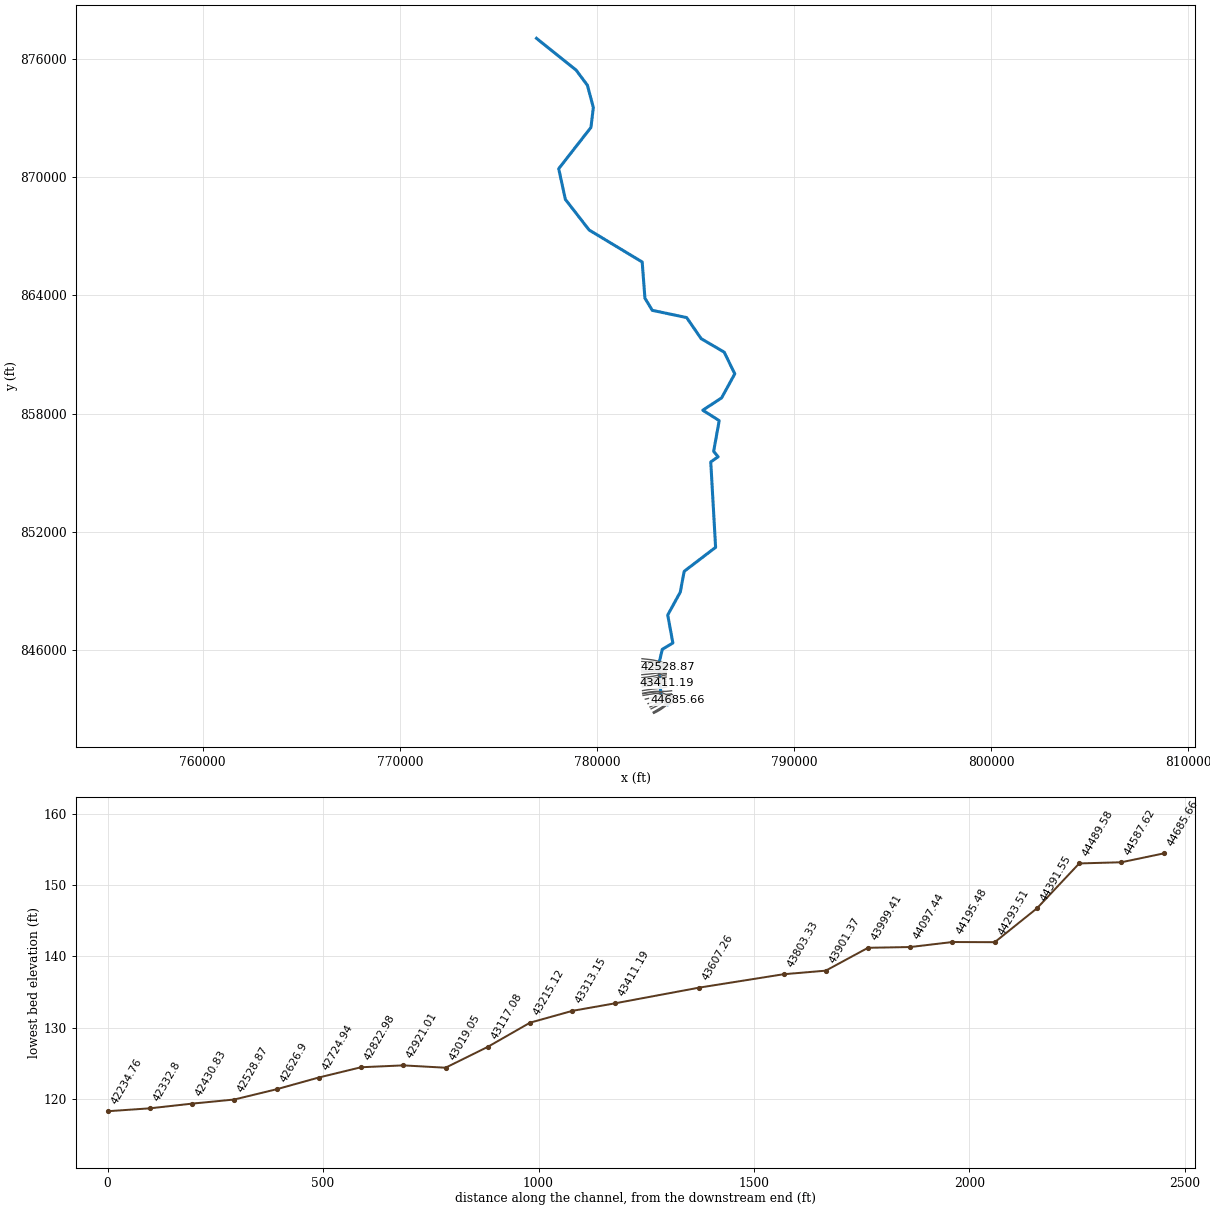
--- 15937_ras.prj (project) ---

Proj Title=15937
Current Plan=p01
Default Exp/Contr=0.3,0.1
English Units
Geom File=g01
Flow File=f01
Plan File=p01
Y Axis Title=Elevation
X Axis Title(PF)=Main Channel Distance
X Axis Title(XS)=Station
BEGIN DESCRIPTION:
RFD model 15937 exported to HEC-RAS
END DESCRIPTION:

--- 15937_ras.p01 (plan) ---

Plan Title=Plan 01
Program Version=4.10
Short Identifier=Plan 01
Geom File=g01
Flow File=f01
Subcritical Flow
Calc Critical at every XS
Secant Critical Depth

--- 15937_ras.f01 (steady flow) ---

Flow Title=Flow 01
Program Version=5.01
Number of Profiles= 6
Profile Names=10yr,25yr,50yr,100yr,100plus,500yr
River Rch & RM=15937,170,44685.66
 2889.32 4718.61 6471.84 8085.5911804.9613918.35
River Rch & RM=15937,170,44587.62
 3815.59 6248.58 8587.8710744.7215687.2917819.25
River Rch & RM=15937,170,44391.55
 3817.12 6251.13 8591.42 10749.215693.8317825.77
River Rch & RM=15937,170,44293.51
  3817.7 6252.09 8592.7510750.8815696.2817828.21
River Rch & RM=15937,170,44195.48
 3835.81 6282.29 8634.7710803.9715773.7917905.59
River Rch & RM=15937,170,43999.41
 3837.14 6284.51 8637.8610807.8715779.4917911.28
River Rch & RM=15937,170,43901.37
 3838.46 6286.72 8640.9410811.7715785.1817916.98
River Rch & RM=15937,170,43803.33
 3841.68 6292.09 8648.4210821.23   15799 17930.8
River Rch & RM=15937,170,43607.26
  3844.9 6297.46 8655.91 10830.715812.8217944.63
River Rch & RM=15937,170,43411.19
 3847.16 6301.25 8661.1910837.3715822.5617954.38
River Rch & RM=15937,170,43313.15
 3858.33  6319.9 8687.1610870.2215870.5218002.32
River Rch & RM=15937,170,43215.12
 3859.65 6322.11 8690.2410874.11 15876.2   18008
River Rch & RM=15937,170,43117.08
 3861.92  6325.9 8695.5210880.7915885.9518017.74
River Rch & RM=15937,170,42921.01
 3864.18 6329.68 8700.7910887.4615895.6918027.48
River Rch & RM=15937,170,42822.98
 3867.21 6334.73 8707.8310896.3615908.6818040.46
River Rch & RM=15937,170,42724.94
 3868.15 6336.31 8710.0310899.1315912.7418044.52
River Rch & RM=15937,170, 42626.9
 3872.87 6344.19 8721.0110913.0315933.02 18064.8
River Rch & RM=15937,170,42528.87
 3873.81 6345.77  8723.2 10915.815937.0718068.86
River Rch & RM=15937,170,42430.83
 3874.94 6347.65 8725.8310919.1315941.9318073.72
River Rch & RM=15937,170, 42332.8
 3875.88 6349.22 8728.02 10921.915945.9818077.77
River Rch & RM=15937,170,42234.76
 4113.38 6745.71 9280.2211620.0416965.2619090.64
River Rch & RM=15937,170,42136.72
 4114.12 6746.95 9281.9511622.2316968.4619093.82
River Rch & RM=15937,170,42038.69
 4114.68 6747.88 9283.2511623.8716970.86 19096.2
River Rch & RM=15937,170,41940.65
 4117.09 6751.91 9288.8711630.9916981.2519106.51
River Rch & RM=15937,170,41744.58
 4117.83 6753.15  9290.611633.1816984.4519109.68
River Rch & RM=15937,170,41450.47
 4130.99 6775.17 9321.3211672.0617041.2119165.97
River Rch & RM=15937,170,41156.37
 4151.74 6809.88 9369.7111733.3217130.6419254.63
River Rch & RM=15937,170,40960.29
 4154.14  6813.9 9375.3211740.4217141.02 19264.9
River Rch & RM=15937,170,40764.22
 4156.18  6817.3 9380.0711746.4317149.79 19273.6
River Rch & RM=15937,170,40568.15
 4159.31 6822.56  9387.411755.7117163.3419287.04
River Rch & RM=15937,170,40372.08
 4161.71 6826.57    939311762.81 17173.719297.31
River Rch & RM=15937,170,40139.41
    4163 6828.73 9396.0211766.6217179.2719302.84
River Rch & RM=15937,170,39980.88
 4163.37 6829.35 9396.8811767.7117180.8619304.42
River Rch & RM=15937,170, 39668.7
 4805.83 7895.5110876.3213631.6319902.1821939.19
River Rch & RM=15937,170,39571.18
 4879.91 8019.5211049.3813850.7820222.1422249.38
River Rch & RM=15937,170,39473.66
 4881.15 8021.61 11052.313854.4720227.5322254.61
River Rch & RM=15937,170,39278.62
 4891.49 8038.9311076.48 13885.120272.2522297.93
River Rch & RM=15937,170,38986.06
 4894.69 8044.2911083.9713894.5920286.1122311.37
River Rch & RM=15937,170,38888.54
    4905 8061.57 11108.113925.1720330.7522354.64
River Rch & RM=15937,170, 38693.5
  4908.2 8066.9311115.5813934.6520344.5922368.07
River Rch & RM=15937,170,38498.46
 4910.32  8070.511120.5713940.9720353.8222377.01
River Rch & RM=15937,170,38400.94
 4914.58 8077.6411130.5413953.6120372.27 22394.9
River Rch & RM=15937,170,38303.42
 4924.17 8093.71   1115313982.06 20413.822435.13
River Rch & RM=15937,170, 38205.9
 4925.42  8095.8 11155.913985.7420419.1822440.34
River Rch & RM=15937,170,38010.86
  4926.3 8097.2811157.9813988.3720423.0322444.07
River Rch & RM=15937,170,37913.34
 4927.01 8098.4711159.6413990.48 20426.122447.05
River Rch & RM=15937,170,37815.82
 4927.37 8099.0611160.4713991.5320427.6422448.54
River Rch & RM=15937,170, 37718.3
 4928.25 8100.5511162.5413994.1620431.4822452.26
River Rch & RM=15937,170,37523.26
 4970.19  8170.911260.8314118.7320613.3522628.44
River Rch & RM=15937,170,37425.74
 4971.26 8172.6811263.3114121.8920617.96 22632.9
River Rch & RM=15937,170,37328.22
 4971.79 8173.5711264.5614123.4620620.2622635.12
River Rch & RM=15937,170, 37230.7
 4972.85 8175.3411267.0414126.6120624.8622639.57
River Rch & RM=15937,170,37035.66
 4973.38 8176.2311268.2914128.1920627.16 22641.8
River Rch & RM=15937,170,36725.48
 5139.16 8453.9511656.0214619.3221344.2123333.02
River Rch & RM=15937,170,36299.44
 5149.49 8471.2911680.2614650.0621389.0823376.27
River Rch & RM=15937,170,36199.64
 5151.05 8473.9111683.9414654.7221395.8923382.87
River Rch & RM=15937,170,36000.05
 5157.12 8484.1211698.2314672.88 21422.4 23408.5
River Rch & RM=15937,170,35800.46
 5159.37 8487.9111703.5414679.6221432.2423418.03
River Rch & RM=15937,170,35600.86
 5162.14 8492.5811710.0714687.9121444.3523429.74
River Rch & RM=15937,170,35301.47
 5271.75 8676.3911966.8815013.4121919.5723886.35
River Rch & RM=15937,170,35101.88
 5273.81 8679.8611971.7515019.59 21928.623895.06
River Rch & RM=15937,170,35002.08
 5275.01 8681.8811974.5915023.1921933.8623900.15
River Rch & RM=15937,170,34902.29
 5286.57 8701.3412001.8215057.7821984.3623948.81
River Rch & RM=15937,170,34589.83
 5291.02 8708.8312012.3315071.1422003.8723967.68
River Rch & RM=15937,170,34480.29
 5291.87 8710.2712014.3515073.7122007.63 23971.3
River Rch & RM=15937,170,34173.19
 5297.68 8720.0712028.0915091.1922033.1423995.97
River Rch & RM=15937,170,33976.61
 5298.87 8722.0912030.9215094.7822038.3824001.05
River Rch & RM=15937,170,33878.33
 5381.53 8861.1512225.62   1534222399.31 24348.2
River Rch & RM=15937,170,33780.04
  5385.1 8867.1812234.0715352.7522415.0224363.35
River Rch & RM=15937,170,33681.76
  5423.6 8931.9412324.7315467.8522583.0624524.65
River Rch & RM=15937,170,33583.47
 5424.79 8933.9412327.5415471.4322588.2924529.68
River Rch & RM=15937,170,33485.18
  5425.3  8934.812328.7515472.9622590.5324531.84
River Rch & RM=15937,170, 33386.9
 5429.71 8942.2512339.1915486.2522609.9324550.53
River Rch & RM=15937,170,33190.32
 5469.03 9008.3712431.7515603.7522781.4724714.94
River Rch & RM=15937,170,32993.75
 5485.26 9035.78 12470.215652.6822852.9124783.73
River Rch & RM=15937,170,32895.46
 5486.61 9038.0612473.4115656.7522858.8624789.46
River Rch & RM=15937,170,32797.18
 5487.96 9040.3412476.6115660.8322864.8124795.18
River Rch & RM=15937,170,32698.89
 5509.96 9077.38 12528.515726.7622961.0724887.49
River Rch & RM=15937,170, 32600.6
 5511.14 9079.38 12531.315730.3222966.27 24892.5
River Rch & RM=15937,170,32502.32
  5513.5 9083.37 12536.915737.4522976.67 24902.5
River Rch & RM=15937,170,32305.74
 5521.43 9096.76 12555.715761.3623011.58 24936.1
River Rch & RM=15937,170,32207.46
 5523.28 9099.8912560.0915766.9523019.7524943.95
River Rch & RM=15937,170,32109.17
 5526.99 9106.1612568.8915778.1423036.0924959.67
River Rch & RM=15937,170,32010.88
 5527.33 9106.7212569.6915779.1623037.57 24961.1
River Rch & RM=15937,170, 31912.6
 5529.36 9110.1512574.4915785.2623046.4924969.67
River Rch & RM=15937,170,31814.31
  5547.4 9140.6112617.2415839.6623125.9125046.03
River Rch & RM=15937,170,31716.02
 5548.41 9142.3212619.6415842.7223130.3725050.31
River Rch & RM=15937,170,31617.74
 5549.26 9143.7512621.6415845.2623134.0825053.87
River Rch & RM=15937,170,31421.16
  5549.6 9144.3212622.4515846.2823135.57 25055.3
River Rch & RM=15937,170,31322.88
 5551.29 9147.1812626.4515851.37   2314325062.43
River Rch & RM=15937,170,31224.59
 5565.11 9170.5112659.1915893.0423203.8325120.88
River Rch & RM=15937,170,31126.31
 5584.98 9203.98 12706.115952.6323290.8425204.17
River Rch & RM=15937,170,31028.02
 5585.83 9205.4112708.0915955.1723294.5625207.73
River Rch & RM=15937,170,30929.73
 5587.01  9207.412710.8915958.7323299.7525212.71
River Rch & RM=15937,170,30831.45
 5587.52 9208.2612712.0915960.2623301.9825214.84
River Rch & RM=15937,170,30733.16
 5588.53 9209.9712714.4915963.3123306.4325219.11
River Rch & RM=15937,170,30634.87
 5589.04 9210.8212715.6915964.8323308.6525221.25
River Rch & RM=15937,170, 30438.3
 5589.38 9211.3912716.4915965.8523310.1425222.67
River Rch & RM=15937,170,30340.01
 5589.54 9211.6812716.8915966.3623310.8825223.38
River Rch & RM=15937,170,30143.44
 5618.76 9260.8712785.8116053.9223438.72 25345.6
River Rch & RM=15937,170,29750.29
 5631.59 9282.5212816.16 16092.523495.0625399.54
River Rch & RM=15937,170,29321.42
 5636.67 9291.0712828.1516107.7423517.3125420.81
River Rch & RM=15937,170,29213.96
 5637.35 9292.2112829.7516109.7823520.2725423.65
River Rch & RM=15937,170,28909.41
 5638.36 9293.9212832.1516112.8223524.72 25427.9
River Rch & RM=15937,170,28377.01
 7103.23 11735.916231.8320406.5529793.5631223.84
River Rch & RM=15937,170,28127.01
 7118.9111762.3116268.8520453.5929862.2431287.26
River Rch & RM=15937,170,26627.01
 7163.71 11837.616374.2320587.3130057.4731466.79
River Rch & RM=15937,170,25877.01
 7177.9411861.4816407.6220629.6530119.29 31523.5
River Rch & RM=15937,170,25377.01
 7215.6511924.6516495.8520741.37 30282.431672.58
River Rch & RM=15937,170,23761.52
  7402.812234.6916925.8221282.3831072.2832381.05
River Rch & RM=15937,170,23542.79
 7416.35 12257.216957.0621321.7331129.7332432.62
River Rch & RM=15937,170,23277.95
 7419.9612263.1616965.3221332.1231144.8932446.15
River Rch & RM=15937,170,23035.69
 7554.7112484.1517269.7821712.8431700.7532935.02
River Rch & RM=15937,170,22793.44
 7555.5712485.5717271.7421715.3131704.3532938.22
River Rch & RM=15937,170,22551.19
 7559.1612491.5117279.9621725.6531719.4532951.67
River Rch & RM=15937,170,22066.69
 7720.9812760.1917653.1222195.7732405.8233565.49
River Rch & RM=15937,170,21824.44
 7726.7612769.8217666.5422212.7232430.5733587.74
River Rch & RM=15937,170,21582.19
 7730.04 12775.317674.1822222.3832444.6733600.45
River Rch & RM=15937,170,21339.94
 7733.8212781.6117682.97 22233.532460.9133615.07
River Rch & RM=15937,170,21097.69
  7738.412789.2717693.6522247.0132480.6333632.86
River Rch & RM=15937,170,20855.44
 7749.2512807.38 17718.922278.9132527.2133674.77
River Rch & RM=15937,170,20613.19
 7754.4312816.0717731.0422294.2932549.6733695.09
River Rch & RM=15937,170,20370.94
 7756.0612818.7917734.84 22299.132556.6933701.44
River Rch & RM=15937,170,20128.69
 7759.6312824.78 17743.222309.6932572.15 33715.4
River Rch & RM=15937,170,19886.44
 7761.7112828.2717748.0922315.8932581.2133723.65
River Rch & RM=15937,170,19644.19
 7775.8512852.0317781.3222358.0432642.7333779.48
River Rch & RM=15937,170,19401.94
 7777.1212854.1617784.3222361.85 32648.333784.55
River Rch & RM=15937,170,19159.69
  7834.212950.27   1791922532.9232898.0634011.91
River Rch & RM=15937,170,18895.69
  7857.312989.2917973.7822602.6132999.8134104.83
River Rch & RM=15937,170,18410.47
 8758.7714500.1620085.0225276.9736904.3837602.31
River Rch & RM=15937,170,17925.26
 8766.4814513.1620103.2625300.1736938.25 37632.7
River Rch & RM=15937,170,17440.05
 8775.3714528.1820124.3625327.0336977.4637667.95
River Rch & RM=15937,170,16954.83
 8781.65 14538.820139.2825346.0137005.1837692.86
River Rch & RM=15937,170,16751.31
 8782.8714540.8720142.1825349.7137010.5737697.72
River Rch & RM=15937,170,16479.89
 8790.1814553.2420159.5825371.8737042.9437726.88
River Rch & RM=15937,170,16136.52
 8792.9214557.88 20166.125380.1837055.06 37737.8
River Rch & RM=15937,170, 15930.9
  8795.214561.7420171.53 25387.137065.1737746.91
River Rch & RM=15937,170,15635.13
 8796.8714564.5720175.5225392.1737072.5737753.59
River Rch & RM=15937,170,15287.22
  9038.414972.5320748.4626121.1538136.8838707.45
River Rch & RM=15937,170,14910.92
  9049.614991.4820775.11 26155.138186.4538751.93
River Rch & RM=15937,170,13461.67
 9207.1915260.0521154.39 26640.138894.54 39392.2
River Rch & RM=15937,170,12434.45
11087.9918395.7525522.2132155.2946946.72 46337.8
River Rch & RM=15937,170,11405.69
11106.1418426.6225565.7632210.8947027.9146408.91
River Rch & RM=15937,170,11140.32
11107.8518429.5325569.8632216.1447035.5646415.63
River Rch & RM=15937,170,10031.77
11150.4918502.2725672.6832347.6747227.6146584.56
River Rch & RM=15937,170,9548.251
11166.24 18529.125710.5732396.1147298.3246646.59
River Rch & RM=15937,170,9060.829
11252.5118675.1925916.12   3265847680.68 46979.1
River Rch & RM=15937,170,7072.182
13300.5622101.0130699.0638708.2856514.0954423.77
River Rch & RM=15937,170,5185.483
13419.2222306.2430991.6939085.4657064.7754904.08
River Rch & RM=15937,170,3062.386
13518.6722479.3231239.4439405.8557532.5455314.85
River Rch & RM=15937,170, 320.317
21028.9635607.7150093.2163857.0793231.3385682.32
Boundary for River Rch & Prof#=15937,170,1
Up Type= 0
Dn Type= 3
Dn Slope=0.000500
Boundary for River Rch & Prof#=15937,170,2
Up Type= 0
Dn Type= 3
Dn Slope=0.000500
Boundary for River Rch & Prof#=15937,170,2
Up Type= 0
Dn Type= 3
Dn Slope=0.000500
Boundary for River Rch & Prof#=15937,170,2
Up Type= 0
Dn Type= 3
Dn Slope=0.000500
Boundary for River Rch & Prof#=15937,170,2
Up Type= 0
Dn Type= 3
Dn Slope=0.000500
Boundary for River Rch & Prof#=15937,170,2
Up Type= 0
Dn Type= 3
Dn Slope=0.000500

--- 15937_ras.g01 (geometry) ---

Geom Title=15937
Program Version=4.10

River Reach=15937,170
Reach XY= 30
783596.882468045 843247.25216946783254.066298038843623.976995423
783117.901445895845228.850739151783309.286684096846045.390452564
783846.513453037846370.507338464783585.665481895847789.938941404
784222.831858695848947.703734353784419.480476201850002.934342921
786014.832013011851222.021799102785768.973612398855551.560339138
786140.843920231855814.921136945785915.728919864856091.381171361
 786197.42587015857649.417817071785363.540627569858176.932929263
 786317.98239091858800.917932004 786988.06614244860023.254470289
786449.679564238861124.041231498785283.300990105861805.647719339
784545.666290909862876.683138505782800.646712214863244.720076308
782430.206527293863858.495365649782290.549972802865697.971028417
779600.587578148867316.782447964778393.804605037868871.535606474
778055.774475813870429.504470289779691.269701153872522.097659722
779812.930044293873532.663175732779510.875523686874661.467635959
778940.930725813875426.987109169776930.032506645877041.908925682

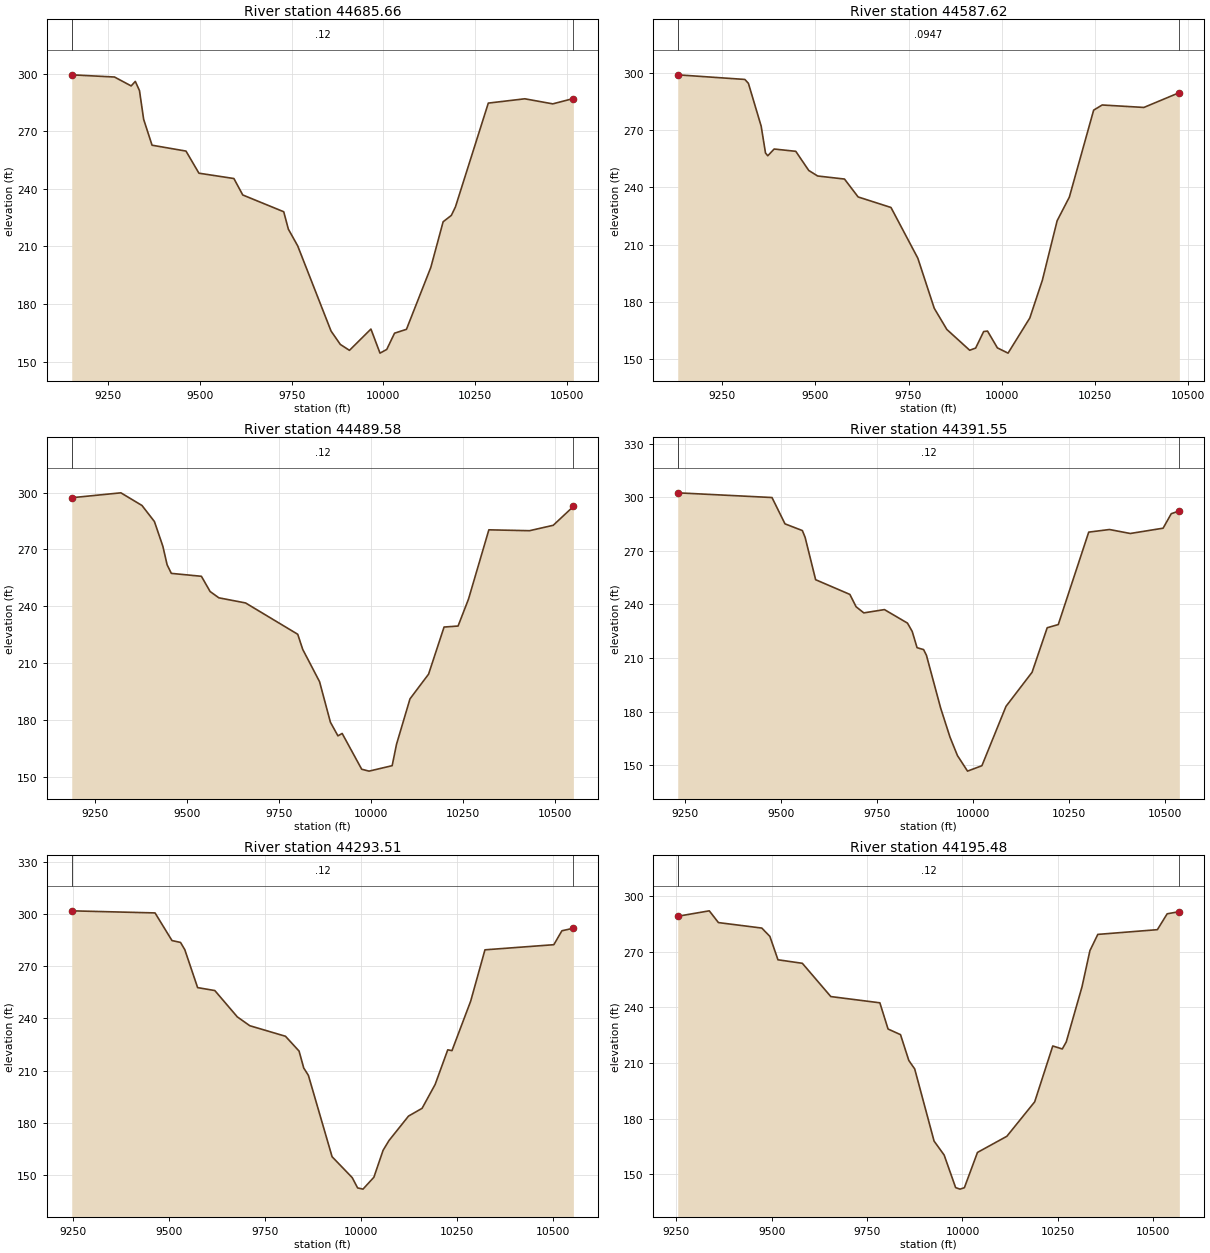
Type RM Length L Ch R = 1 ,44685.66,98.035800,98.035800,98.035800
XS GIS Cut Line= 6
782880.876088028842798.711260591783064.181485684842892.753582008
783218.589049233842984.383087253783347.186218485843072.952660134
783546.179895763843226.517485936784067.209518621843461.004189155
#Sta/Elev= 30
9151.772299.44689268.157298.30559313.452293.66399324.776296.0205  9336.1291.2348
9347.423276.27589370.293262.77459462.671259.70589497.923248.18549593.011245.4099
9617.211236.8324 9728.67228.09339741.293219.01329766.644210.32199857.431165.9324
9882.736158.94199907.557155.87239965.959166.97499990.671154.423710008.95156.3321
10030.21164.817710062.61166.820410128.88199.077110162.43222.873410184.79226.1925
10195.98230.642810285.39284.711110384.69 286.95610460.81284.3134 10516.9287.1042
#Mann= 3 , 0 , 0
9151.772    0.12       09151.772    0.12       0 10516.9    0.12       0
#XS Ineff= 2 , 0
       0                               0
Bank Sta=9151.772,10516.9
Exp/Cntr=0.3,0.1

Type RM Length L Ch R = 1 ,44587.62,98.035900,98.035900,98.035900
XS GIS Cut Line= 6
782866.247148735842823.176900445783288.793385933843067.042638707
783433.422208652843186.307435569783635.741403682843429.015330314
783798.986149245843536.287421729 783942.74127533843598.574352799
#Sta/Elev= 30
9130.863298.87659310.858296.45939320.447294.41849354.682272.01359366.288  257.95
9372.415256.5018  9389.5260.03439447.532258.83269482.301248.80159506.185245.9137
9578.164244.3137 9614.72234.94849702.884229.42849774.886202.86619818.911176.6621
9852.782165.55159914.004154.6922 9929.94155.8307 9951.45164.4879 9961.81164.7299
  9988.3155.927310016.87153.183810075.27171.588210108.85191.320310148.55222.4928
 10181.3 234.87110246.49280.389110269.36283.0875 10381.2 281.80110476.38289.5623
#Mann= 3 , 0 , 0
9130.863  0.0947       09130.863  0.0947       010476.38  0.0947       0
#XS Ineff= 2 , 0
       0                               0
Bank Sta=9130.863,10476.38
Exp/Cntr=0.3,0.1

Type RM Length L Ch R = 1 ,44489.58,98.035800,98.035800,98.035800
XS GIS Cut Line= 6
782845.474503126842857.917359481 783306.06028165843131.523123687
783438.510095372843268.251968602783467.673172934843391.137217341
783544.943335919843494.455732809783876.598839468843671.679150334
#Sta/Elev= 30
9185.505297.25819319.209299.84419376.564293.17279410.466284.67569433.443271.5993
9444.932261.8808 9456.42257.34669538.223255.81179561.949247.76219585.676244.4591
9658.374241.74199800.274225.21739813.869217.23959859.627200.2169 9889.19178.8144
 9909.64171.62319921.138172.89659974.284154.01639994.323153.017710057.15155.8973
10068.99 167.18510105.64191.140410156.21204.185110198.36229.033310236.47229.5699
10264.79243.7699 10320.2280.327610430.77279.859310495.33282.713910550.13292.6603
#Mann= 3 , 0 , 0
9185.505    0.12       09185.505    0.12       010550.13    0.12       0
#XS Ineff= 2 , 0
       0                               0
Bank Sta=9185.505,10550.13
Exp/Cntr=0.3,0.1

Type RM Length L Ch R = 1 ,44391.55,98.035900,98.035900,98.035900
XS GIS Cut Line= 6
782743.121331398 843029.09421565783125.800000674843224.755718352
783440.159416046843432.803510367783549.519081432843533.716598421
 783620.76465782843582.035735166 783865.07488139843684.416156632
#Sta/Elev= 30
9230.083302.45099475.857  299.829509.776 285.0879555.001281.33749562.197277.5642
9589.675253.83629678.878245.60579695.189238.6898 9715.27235.27269769.045237.1112
9829.121229.54869841.481224.88939854.122 215.8019871.137214.7399 9878.56211.5505
 9915.64181.99959940.028165.72439959.399 155.4489985.734146.729610023.17149.7588
10086.02182.977910154.02202.057110193.45226.9612 10222.3228.735610301.68280.4594
10355.82281.922610410.08   279.710495.62282.661110516.87290.768910538.03292.3281
#Mann= 3 , 0 , 0
9230.083    0.12       09230.083    0.12       010538.03    0.12       0
#XS Ineff= 2 , 0
       0                               0
Bank Sta=9230.083,10538.03
Exp/Cntr=0.3,0.1

Type RM Length L Ch R = 1 ,44293.51,98.035800,98.035800,98.035800
XS GIS Cut Line= 6
782685.877494151843124.829598634783135.714852477843337.109244023
783272.341227754843425.361127167783405.720663957843544.931750753
783489.961956248843597.251340067783833.535462639843719.275514201
#Sta/Elev= 30
9248.034301.83569464.568300.62989508.603284.75399530.816283.68299541.922279.5283
9575.242257.72799619.951256.04349678.374240.93029710.915235.83469803.618 229.786
9838.963221.27869851.098211.55629863.233207.31119924.825160.57789977.161148.5818
9991.101142.681610005.17141.978810033.49 148.82410057.38 164.28210072.67169.8719
10123.44183.926210158.71188.388710192.67202.095410225.49222.004510236.43221.5197
10285.06249.965310322.17279.433110501.24282.380410522.17290.374610552.04291.8428
#Mann= 3 , 0 , 0
9248.034    0.12       09248.034    0.12       010552.04    0.12       0
#XS Ineff= 2 , 0
       0                               0
Bank Sta=9248.034,10552.04
Exp/Cntr=0.3,0.1

Type RM Length L Ch R = 1 ,44195.48,98.035800,98.035800,98.035800
XS GIS Cut Line= 6
782586.682639252843290.724442176 782837.08334525843376.844074536
783106.303898296843478.057978897783179.161950487843509.291056073
783385.258047939843612.683396639783820.350744257843733.848097676
#Sta/Elev= 30
9254.059289.0972 9336.71292.03389360.718285.69159474.315282.73729495.485278.2524
9516.655265.64459580.542263.74149655.094245.81199783.616242.44569805.094 228.315
9837.716225.28799859.476211.36139874.874206.80969925.651167.90639952.034160.3865
9982.128142.82419993.573142.004310005.02142.767310039.33161.7847 10116.3170.4844
10189.24189.071110236.62219.176110261.58217.568910271.92221.345310313.26251.1218
10333.93270.5642 10354.6279.324810510.68281.874810536.26290.414610568.27291.6063
#Mann= 3 , 0 , 0
9254.059    0.12       09254.059    0.12       010568.27    0.12       0
#XS Ineff= 2 , 0
       0                               0
Bank Sta=9254.059,10568.27
Exp/Cntr=0.3,0.1

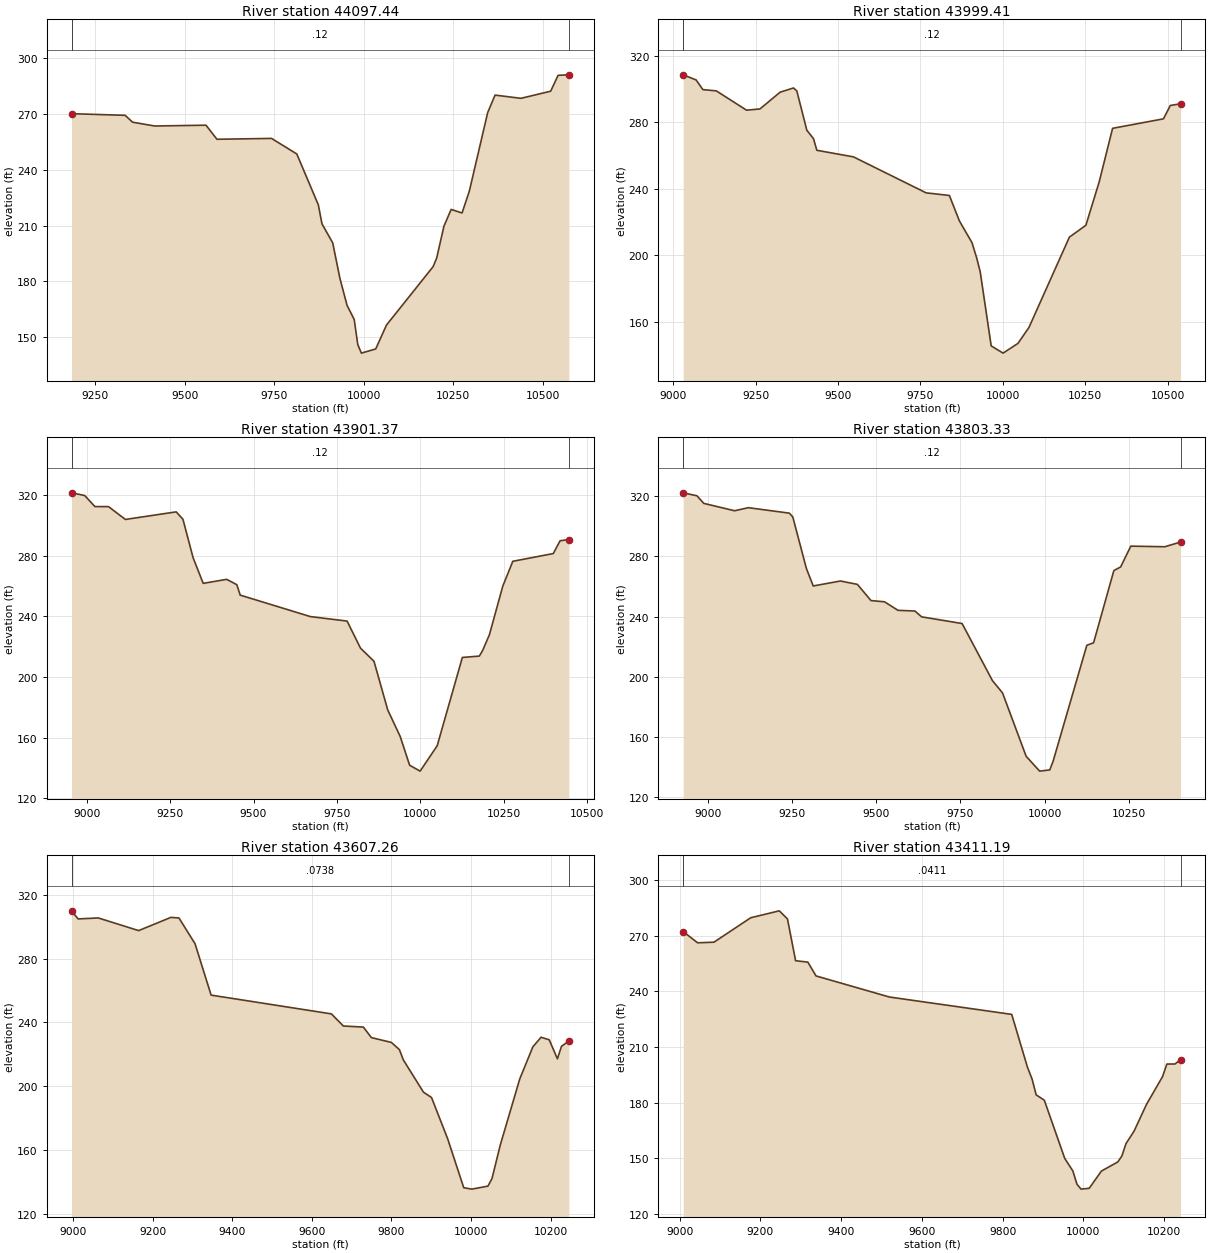
Type RM Length L Ch R = 1 ,44097.44,98.035900,98.035900,98.035900
XS GIS Cut Line= 6
782449.804768527843519.640881152 782902.07810441843624.112139917
783113.455730902843652.065602136783457.274388648843657.214643953
783572.117894527843676.954820297783813.974121155843740.895944264
#Sta/Elev= 30
9184.113270.20429333.853269.31079354.405265.6372 9416.06263.56749559.462264.0048
9590.093256.42719742.485256.88359812.971248.51789873.229221.07029883.235210.9093
9913.251 200.6699933.261181.6503 9953.27167.03029973.274159.42289983.276145.9068
9993.278141.3004 10033.3143.547810063.32 156.397 10193.5187.835810203.53192.5086
10223.73209.597910243.95218.665510274.31216.746210294.71228.516410345.92270.7944
10366.51280.207610438.77278.467510521.76282.299110542.51290.848410572.57291.1169
#Mann= 3 , 0 , 0
9184.113    0.12       09184.113    0.12       010572.57    0.12       0
#XS Ineff= 2 , 0
       0                               0
Bank Sta=9184.113,10572.57
Exp/Cntr=0.3,0.1

Type RM Length L Ch R = 1 ,43999.41,98.035800,98.035800,98.035800
XS GIS Cut Line= 6
782336.686960776843708.820663084782963.836081105843809.430312556
783171.548682011843794.853812012783355.318631657843706.256302122
783443.125802025843686.746330971783805.063359354843750.744680991
#Sta/Elev= 30
9030.456308.61829069.639305.54399090.092299.7334    9131298.95399222.675287.3444
9263.393288.1021 9324.47298.17039365.036300.7128 9375.16298.93519405.531275.2958
9425.779270.20879435.902263.22389546.964259.26449767.446237.61459837.953236.0377
9868.479220.69949906.718207.61239920.878198.43319931.584190.05629964.896145.5473
   10001141.195210046.14147.069810079.59156.695410202.11210.960810252.22218.1269
10292.66244.322410333.18276.435810487.53282.141710508.23290.160610539.34291.2209
#Mann= 3 , 0 , 0
9030.456    0.12       09030.456    0.12       010539.34    0.12       0
#XS Ineff= 2 , 0
       0                               0
Bank Sta=9030.456,10539.34
Exp/Cntr=0.3,0.1

Type RM Length L Ch R = 1 ,43901.37,98.035900,98.035900,98.035900
XS GIS Cut Line= 6
782316.194435529843793.285407122782714.975509939843863.577868201
783034.719857256843891.177055669783246.918715864843871.113769836
783497.894378557843761.143977338  783770.6749566843788.752915616
#Sta/Elev= 30
8954.145321.27788993.698319.49879024.275312.21699064.994312.18829115.783303.7461
9268.082308.74219288.318303.86119318.672278.58389349.026261.65469419.649264.3023
9449.901260.76299459.952253.92279670.524239.76549780.628236.81449820.843218.9701
9861.302210.33769902.514178.2814 9939.94160.80219968.173141.86549999.636137.9889
 10050.8154.683510126.33212.853510177.37213.764210187.41217.584610207.48227.8584
10247.48259.761710277.63276.1849   10399281.283310419.48 289.72510445.77290.4895
#Mann= 3 , 0 , 0
8954.145    0.12       08954.145    0.12       010445.77    0.12       0
#XS Ineff= 2 , 0
       0                               0
Bank Sta=8954.145,10445.77
Exp/Cntr=0.3,0.1

Type RM Length L Ch R = 1 ,43803.33,196.071700,196.071700,196.071700
XS GIS Cut Line= 6
 782314.89646903843820.747645667 782657.72342809843880.995682878
 782916.01287957843911.608325478783121.766874678843918.332261261
783503.652226443843913.622512807783781.018948708843944.887441725
#Sta/Elev= 30
8927.607 322.122  8968.4320.1518 8988.73315.11689080.213310.23129120.872312.2682
9242.556308.63389252.686306.14789293.152 271.8849313.349260.33259394.083263.6239
9444.422261.38149484.633250.64629524.797249.82499564.881 244.162 9614.95243.7083
9634.977239.84299755.006235.41679845.021197.52929875.025189.35289945.037147.3196
9985.043137.486610015.05138.284510025.05144.098410125.07220.9932 10145.1222.6332
10205.23270.550810225.34272.946910255.51286.756310356.43286.347410403.07289.4753
#Mann= 3 , 0 , 0
8927.607    0.12       08927.607    0.12       010403.07    0.12       0
#XS Ineff= 2 , 0
       0                               0
Bank Sta=8927.607,10403.07
Exp/Cntr=0.3,0.1

Type RM Length L Ch R = 1 ,43607.26,196.071700,196.071700,196.071700
XS GIS Cut Line= 6
782308.646737575843952.978805898782603.774026957844001.521668353
782758.601859954844023.052568824783198.311813614844073.223019354
783344.099402932844096.491274148783543.065208983844143.005742129
#Sta/Elev= 30
8995.874309.86329012.475304.79129063.231305.39599164.575297.48169245.585305.7552
9265.837305.40779306.308289.26629346.693257.08649648.935245.33999679.094237.7426
9729.359237.07669749.465230.49699799.749227.46079819.926222.94959830.015216.4259
9880.457196.30939900.656192.95829941.138167.19429981.621136.505410001.87135.6079
10042.45137.492310052.72142.283910073.26163.040310122.42204.602210155.44224.7354
10175.99230.704310196.53229.093110217.08217.201710227.35225.062810245.86228.3077
#Mann= 3 , 0 , 0
8995.874  0.0738       08995.874  0.0738       010245.86  0.0738       0
#XS Ineff= 2 , 0
       0                               0
Bank Sta=8995.874,10245.86
Exp/Cntr=0.3,0.1

Type RM Length L Ch R = 1 ,43411.19,98.035800,98.035800,98.035800
XS GIS Cut Line= 6
782299.714336682844141.969603686782463.225963022844167.647859843
782787.091042572844214.993632306783279.894651868844284.141524808
783433.932863796844308.149862177 783518.46732158844322.425626758
#Sta/Elev= 30
9008.546272.24459044.264266.21479084.754266.54359175.854279.71939246.598283.4513
9266.811279.09929287.023256.56119317.342255.78599337.555248.35189519.453236.9755
9822.392227.61269861.246199.24049872.882192.6858 9882.98 184.2289903.176181.3313
9953.666150.00239973.861143.18969983.959136.08189994.057 133.39810014.28133.8335
10044.65143.141810085.13148.056110095.25151.241910105.37157.889910125.61164.7027
10155.98178.963610196.04194.056910206.69200.838710226.97200.861810240.63203.2853
#Mann= 3 , 0 , 0
9008.546  0.0411       09008.546  0.0411       010240.63  0.0411       0
#XS Ineff= 2 , 0
       0                               0
Bank Sta=9008.546,10240.63
Exp/Cntr=0.3,0.1

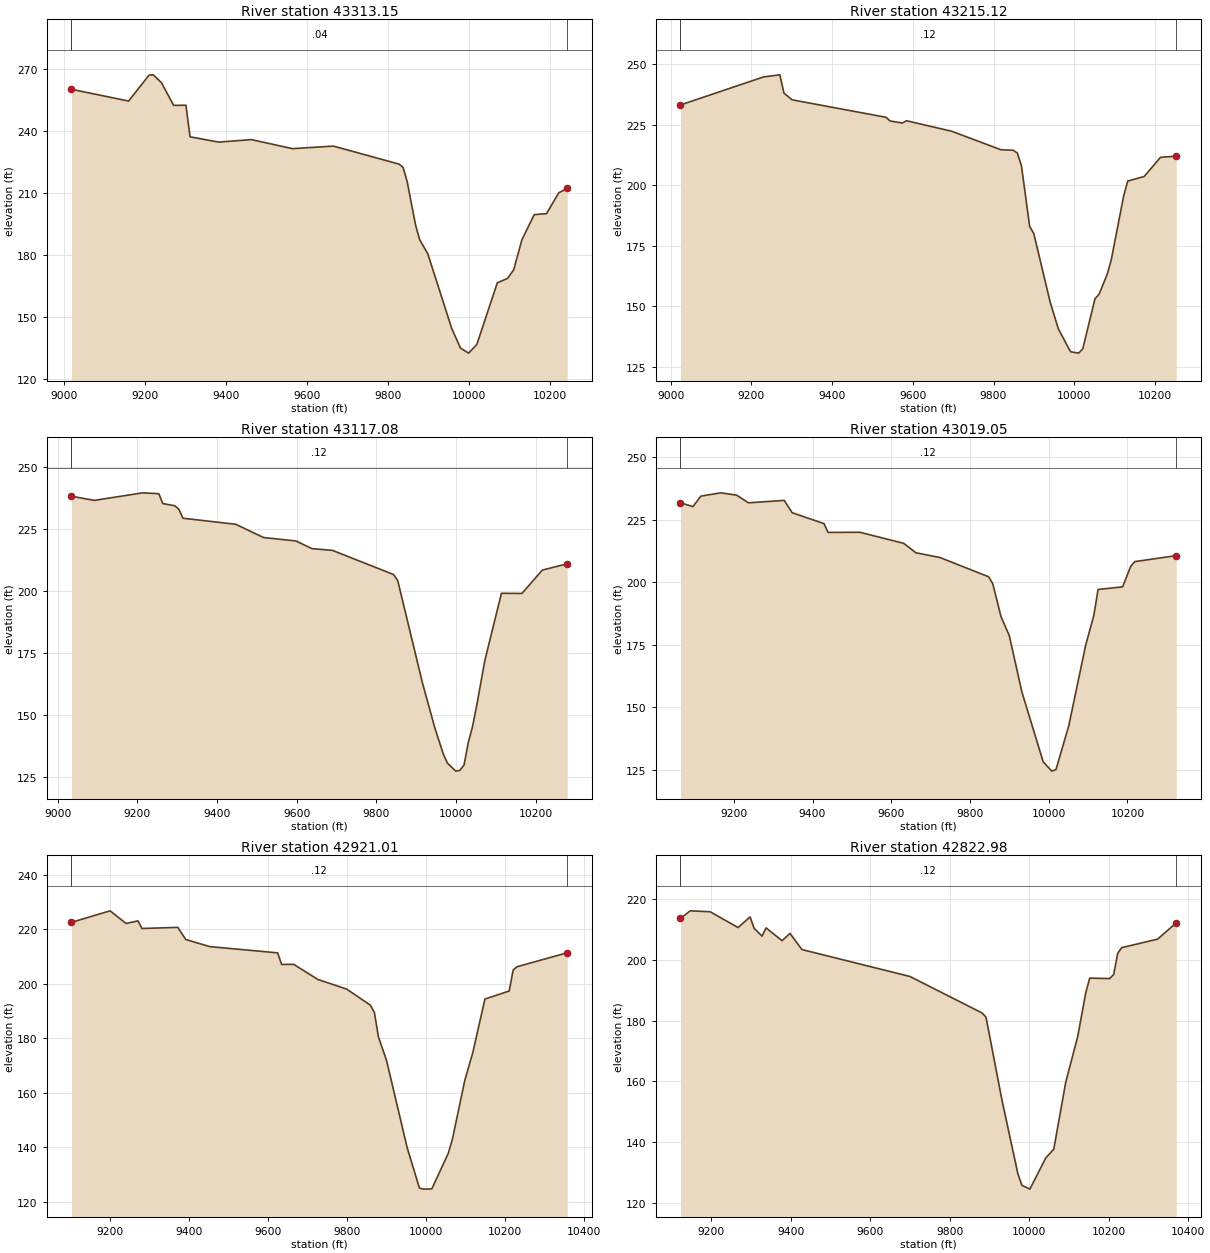
Type RM Length L Ch R = 1 ,43313.15,98.035800,98.035800,98.035800
XS GIS Cut Line= 6
782295.343887574844234.439105848782679.662263385844291.002199915
783126.946222564844361.000860696783265.402436187844381.100291295
 783381.77625826844398.217889544783505.332660508844418.231389901
#Sta/Elev= 30
9017.906260.15869159.066254.46779209.605267.05239219.713267.17049239.928263.4147
9270.251252.37359300.575252.43989310.682 237.1449381.436234.58329462.376235.7836
9563.593231.4097 9664.81232.63649826.757223.91869836.879222.29779847.001215.2545
9867.231 194.6239877.336187.40599897.545180.55629956.537144.41499978.384134.7909
9998.593132.352410018.81136.588710069.35166.423410094.51168.542310109.78172.7098
10130.02187.241610160.41 199.458 10190.8199.9175 10221.2210.069410241.79212.1038
#Mann= 3 , 0 , 0
9017.906    0.04       09017.906    0.04       010241.79    0.04       0
#XS Ineff= 2 , 0
       0                               0
Bank Sta=9017.906,10241.79
Exp/Cntr=0.3,0.1

Type RM Length L Ch R = 1 ,43215.12,98.035900,98.035900,98.035900
XS GIS Cut Line= 6
782291.120659817844323.793714148782578.031799453844363.790066831
782847.392980966844406.081776373783175.077529281844466.948125156
783333.360349569844489.868014508783503.227980379844519.509488856
#Sta/Elev= 30
9024.398 233.2139230.249244.78689270.636245.65569280.732238.12149300.926235.3334
 9533.71228.10989543.832226.5903  9574.2225.73239584.322226.68329696.192222.3585
9818.245214.71219848.758 214.5059858.929213.3397  9869.1208.05599889.442183.0451
9899.613180.12449940.169151.81669960.383140.77069990.703 131.26710010.91130.6982
10021.01132.488110051.32153.177310061.42 155.04310081.63163.261610091.78169.3941
10122.24195.569110132.39201.786210172.99203.6452 10213.6211.5784 10252.4212.0456
#Mann= 3 , 0 , 0
9024.398    0.12       09024.398    0.12       0 10252.4    0.12       0
#XS Ineff= 2 , 0
       0                               0
Bank Sta=9024.398,10252.4
Exp/Cntr=0.3,0.1

Type RM Length L Ch R = 1 ,43117.08,98.035800,98.035800,98.035800
XS GIS Cut Line= 6
782287.643434063844397.364490602782686.116803095844453.297805356
782877.930454339844485.921850311783024.783135566844516.484938763
783337.291383368844604.873753642783506.047419124844642.859934407
#Sta/Elev= 30
9034.316 238.2299092.181236.58119213.245239.62449253.668 239.2699263.774235.2964
9294.092234.39429304.197 232.9319314.303229.37159446.855226.93319516.719221.5798
9597.868 220.2059638.493217.09199689.564216.40789843.422206.63629853.743  204.16
9915.815162.83479947.147144.58159968.035134.23419978.479130.51829999.373127.3099
10009.83127.601910020.26129.827510030.69138.821810041.12 145.05810051.56153.4302
10072.42171.977910114.03199.080110165.45199.008210216.87 208.46310279.12210.9617
#Mann= 3 , 0 , 0
9034.316    0.12       09034.316    0.12       010279.12    0.12       0
#XS Ineff= 2 , 0
       0                               0
Bank Sta=9034.316,10279.12
Exp/Cntr=0.3,0.1

Type RM Length L Ch R = 1 ,43019.05,98.035900,98.035900,98.035900
XS GIS Cut Line= 6
782283.594092087844483.040041861782725.025286922 844543.25530565
782968.976397808844589.705276115783089.827291129844622.769837937
 783329.75866717844714.588132802783508.555556918844752.590963348
#Sta/Elev= 30
9064.599231.80939096.251230.25919116.407234.44879166.798235.78299207.111234.8649
9237.346231.7831 9328.25232.75229348.457227.81569429.284223.45129439.387219.9416
 9520.27219.9965 9632.02215.54749662.497211.79479723.738209.88999847.457202.1702
9857.899199.42059878.785186.23439899.898178.62469931.777 156.1279985.937128.1298
10007.66124.383910018.56125.043610051.15142.646910093.87174.767210114.88 186.872
10125.39197.093810187.73198.134110208.21206.321510218.45208.241110323.81210.6477
#Mann= 3 , 0 , 0
9064.599    0.12       09064.599    0.12       010323.81    0.12       0
#XS Ineff= 2 , 0
       0                               0
Bank Sta=9064.599,10323.81
Exp/Cntr=0.3,0.1

Type RM Length L Ch R = 1 ,42921.01,98.035800,98.035800,98.035800
XS GIS Cut Line= 6
 782277.72981693844607.115758314782824.143821457844678.046895451
783085.464673304844733.436407979783254.074214509844782.712967022
783360.856677629844805.851734537783510.261134306844827.209974355
#Sta/Elev= 30
9102.605222.54369200.455226.77359240.714222.13879270.943223.08519281.019220.2913
9371.705220.71149391.857216.25469452.314213.65739624.201211.35529634.313207.1115
9664.719207.15439725.778201.62469799.049198.06069858.689192.19689868.975189.5403
 9879.26180.53049899.831171.86589951.683140.0611 9982.97125.10269993.399124.7133
10014.24124.795710055.88 137.82310066.28142.948310097.49164.444310117.96174.7666
10148.65194.4299   10210197.363710220.11205.082410230.22206.288310356.75211.3813
#Mann= 3 , 0 , 0
9102.605    0.12       09102.605    0.12       010356.75    0.12       0
#XS Ineff= 2 , 0
       0                               0
Bank Sta=9102.605,10356.75
Exp/Cntr=0.3,0.1

Type RM Length L Ch R = 1 ,42822.98,98.035900,98.035900,98.035900
XS GIS Cut Line= 6
782270.540454328844759.227535448782658.170853529 844796.28979131
783064.834800062844845.733966746783231.047415565 844858.71304121
783472.770121452844883.743255408783511.613551318844886.378218834
#Sta/Elev= 30
9122.085213.74479146.625216.26279196.827215.95629267.161210.74619297.303214.2516
9307.351210.53619327.446207.91359337.494210.63879377.684206.4204 9397.78208.8174
9427.922203.47839699.694194.6052 9881.02182.58199891.093 181.2189931.346153.7883
9971.475129.46589981.507125.722910001.57124.452210041.69134.776410061.74137.6228
10091.84159.7283   10122174.798710142.11189.162710152.16194.058210202.43193.9119
10212.48195.267410222.54202.189710232.59204.114610323.07 206.92710369.82212.2662
#Mann= 3 , 0 , 0
9122.085    0.12       09122.085    0.12       010369.82    0.12       0
#XS Ineff= 2 , 0
       0                               0
Bank Sta=9122.085,10369.82
Exp/Cntr=0.3,0.1

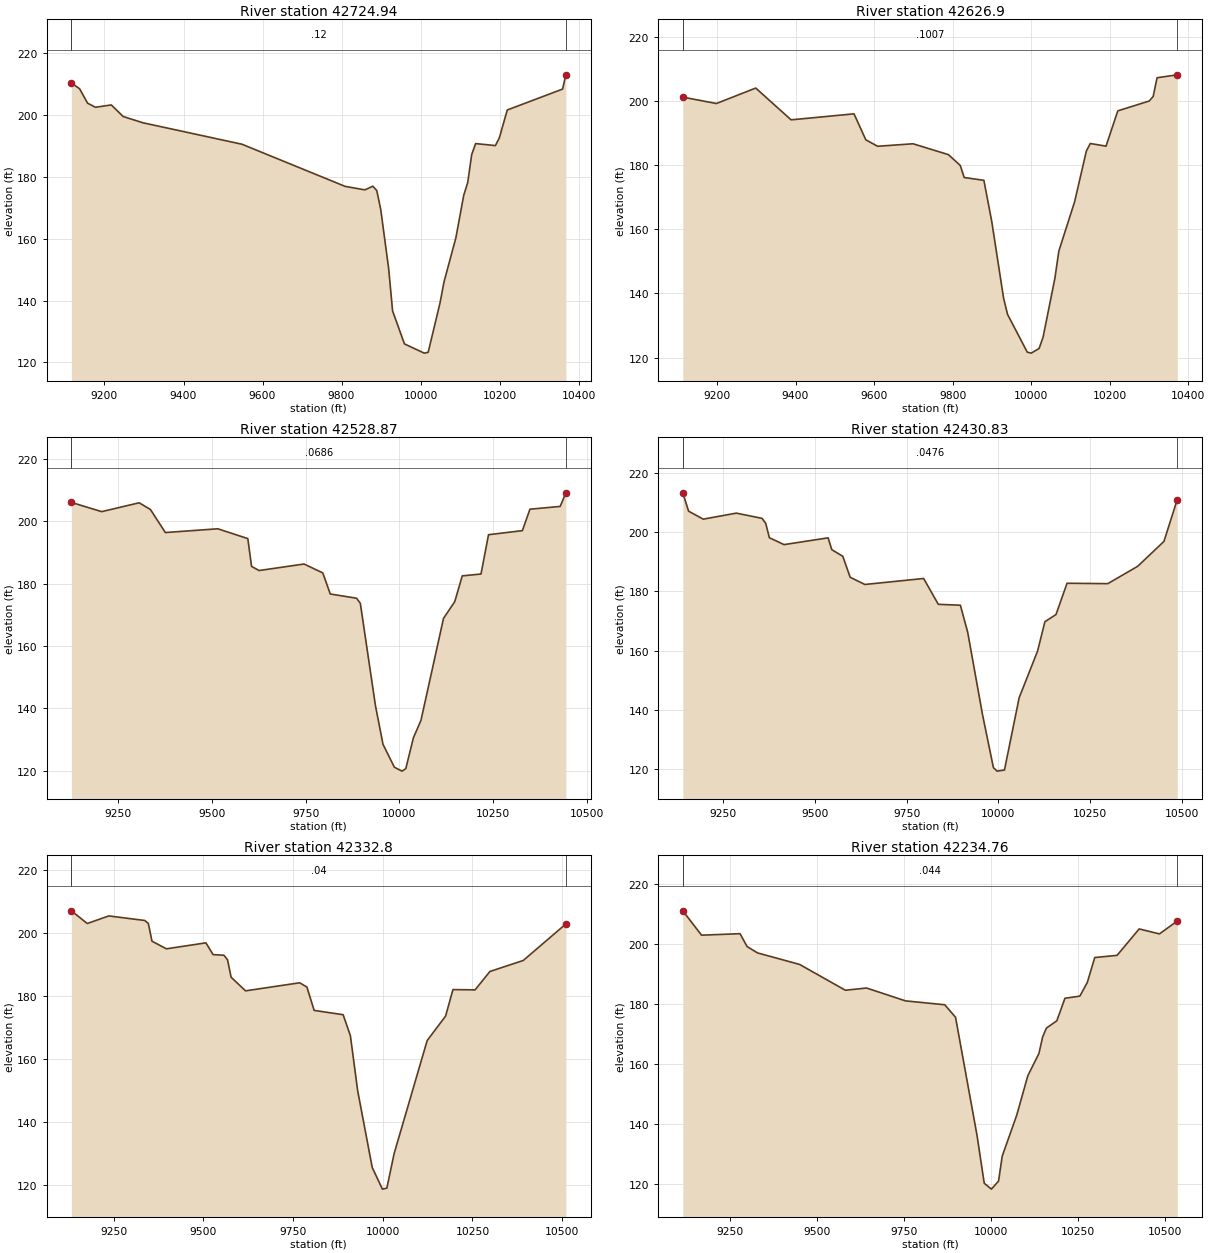
Type RM Length L Ch R = 1 ,42724.94,98.035800,98.035800,98.035800
XS GIS Cut Line= 6
782264.138996398844894.668908442782639.520255936844919.699502619
783008.747484135844949.776016994783095.759401711844952.159520971
783242.220987558844946.937609916783513.210943936 844956.26414613
#Sta/Elev= 30
9116.253210.35169137.152208.45989157.188203.81819177.224202.48879217.296203.2486
 9247.35199.49689297.451197.47339548.138190.53599808.999176.92259859.165175.7844
9879.184176.97359889.187175.56529899.191169.47399919.199 150.4139929.202  136.66
9959.219125.998110009.28123.013210019.29123.286110049.33139.288710059.33146.0195
10089.33160.259210109.34174.063110119.35 178.17210129.36187.160610139.36190.7526
 10189.4190.103510199.41192.597210219.42201.607510359.51208.373310367.72212.9773
#Mann= 3 , 0 , 0
9116.253    0.12       09116.253    0.12       010367.72    0.12       0
#XS Ineff= 2 , 0
       0                               0
Bank Sta=9116.253,10367.72
Exp/Cntr=0.3,0.1

Type RM Length L Ch R = 1 , 42626.9,98.035800,98.035800,98.035800
XS GIS Cut Line= 6
782259.424695503844994.413590513  782795.0075267845019.945702721
783072.480626404 845040.07251417 783240.83688505845056.570968415
783417.836222713845059.613383861  783516.2944996845054.740633084
#Sta/Elev= 30
 9112.97201.24239198.626199.25529298.721204.07569388.806194.15759549.008196.0302
9579.054187.9311  9609.1185.90959699.273186.69329789.474183.29899819.541179.9293
9829.571 176.1659879.739175.28399899.806162.42099929.912138.51919939.968133.4677
9990.247121.667510000.31121.367210020.43122.833410030.49126.3473 10060.6144.7608
10070.64153.217210110.73168.562110140.75184.441310150.76186.780610190.79185.9489
10220.79196.959810300.82 200.03610310.83201.447810320.85207.2932 10372.2208.2044
#Mann= 3 , 0 , 0
 9112.97  0.1007       0 9112.97  0.1007       0 10372.2  0.1007       0
#XS Ineff= 2 , 0
       0                               0
Bank Sta=9112.97,10372.2
Exp/Cntr=0.3,0.1

Type RM Length L Ch R = 1 ,42528.87,98.035900,98.035900,98.035900
XS GIS Cut Line= 6
782254.101871215845107.033346486782967.571286353845124.698921951
783215.110772436845156.785453096783268.075952205845159.350435502
783427.759083795845151.017105281783569.994878722845132.069179008
#Sta/Elev= 30
9124.363206.01219205.275203.05219305.292205.88949335.297203.74599375.304196.3555
9515.327197.56129595.345194.4182 9605.35185.52729625.358 184.1889745.407186.2765
9795.466183.4359 9815.49176.67849885.679175.31649895.714173.69269936.002140.9607
 9956.17128.53199986.619121.184210006.93119.930910017.08120.718510037.38130.6057
10057.55136.179110117.79168.872410147.81174.222210167.82182.478410217.86183.0699
10237.92195.663910328.34196.974110348.52203.834710429.21204.732410444.36209.0814
#Mann= 3 , 0 , 0
9124.363  0.0686       09124.363  0.0686       010444.36  0.0686       0
#XS Ineff= 2 , 0
       0                               0
Bank Sta=9124.363,10444.36
Exp/Cntr=0.3,0.1

Type RM Length L Ch R = 1 ,42430.83,98.035800,98.035800,98.035800
XS GIS Cut Line= 6
782259.244396195845267.011779647783081.010815608845243.269866532
783246.602894294 845234.35059534783344.175432876845223.993140668
783447.408889706845207.363084026783600.504533872845176.003082417
#Sta/Elev= 30
9140.234213.15139155.994206.96859196.005 204.2749286.029206.30839356.048 204.551
 9366.05202.90359376.053198.01759416.064 195.694 9536.12197.97719546.125193.9913
9576.141191.75759596.151184.69549636.172182.26089796.255 184.2799836.276175.5743
9896.307175.27159916.317 166.1549956.338138.60229986.365 120.5229996.376119.3519
10016.41119.717210056.47144.084510106.55159.783410126.58169.706510156.74172.1191
10186.91182.670810298.04182.540410379.45188.3956 10450.9196.783210487.15210.8962
#Mann= 3 , 0 , 0
9140.234  0.0476       09140.234  0.0476       010487.15  0.0476       0
#XS Ineff= 2 , 0
       0                               0
Bank Sta=9140.234,10487.15
Exp/Cntr=0.3,0.1

Type RM Length L Ch R = 1 , 42332.8,98.035900,98.035900,98.035900
XS GIS Cut Line= 6
782270.831685006 845426.33700072782686.052690165845397.287482535
782870.091809601845378.227808681783063.912692691845351.253056357
 783248.02459334845314.414664735783629.934676669845218.382488039
#Sta/Elev= 30
9131.875207.0956 9176.12203.06829236.224 205.4749336.443204.02589346.473203.0711
9356.503197.46289396.623195.02719506.953196.92279527.013193.17939557.124192.9917
9567.177191.56099577.231185.99499617.445181.67829768.348184.24059788.513182.8891
9808.678175.47189889.492 174.0979909.723167.4526 9929.96150.00149970.643 125.564
    9999118.694210011.38119.008510031.81130.039310123.79165.883210175.16173.6536
 10195.7182.071810257.39181.991710298.72187.8255 10391.7191.326610510.45202.9153
#Mann= 3 , 0 , 0
9131.875    0.04       09131.875    0.04       010510.45    0.04       0
#XS Ineff= 2 , 0
       0                               0
Bank Sta=9131.875,10510.45
Exp/Cntr=0.3,0.1

Type RM Length L Ch R = 1 ,42234.76,98.035800,98.035800,98.035800
XS GIS Cut Line= 6
782281.416578948845571.879292352782701.736543061845526.333304983
782837.082835631845505.125216763783011.951428582845468.892646867
783186.920599658845425.930596336783659.087612464845260.362715577
#Sta/Elev= 30
  9115.9211.01349169.727202.89499280.227203.39989300.318 199.1189330.454196.9878
9451.323193.14329582.513184.55139643.245185.29459755.062181.00959867.757179.7145
9898.639175.55469960.404136.13689980.992 120.24410001.59118.2867 10022.2 120.984
10032.51129.237610074.52143.023110106.06156.060910137.94163.474310148.62168.9792
10159.31171.924310189.35174.382210212.73181.886310255.47182.599310276.84187.1568
10298.21195.449410362.32196.179110425.61204.982310483.85 203.32910534.98 207.603
#Mann= 3 , 0 , 0
  9115.9   0.044       0  9115.9   0.044       010534.98   0.044       0
#XS Ineff= 2 , 0
       0                               0
Bank Sta=9115.9,10534.98
Exp/Cntr=0.3,0.1