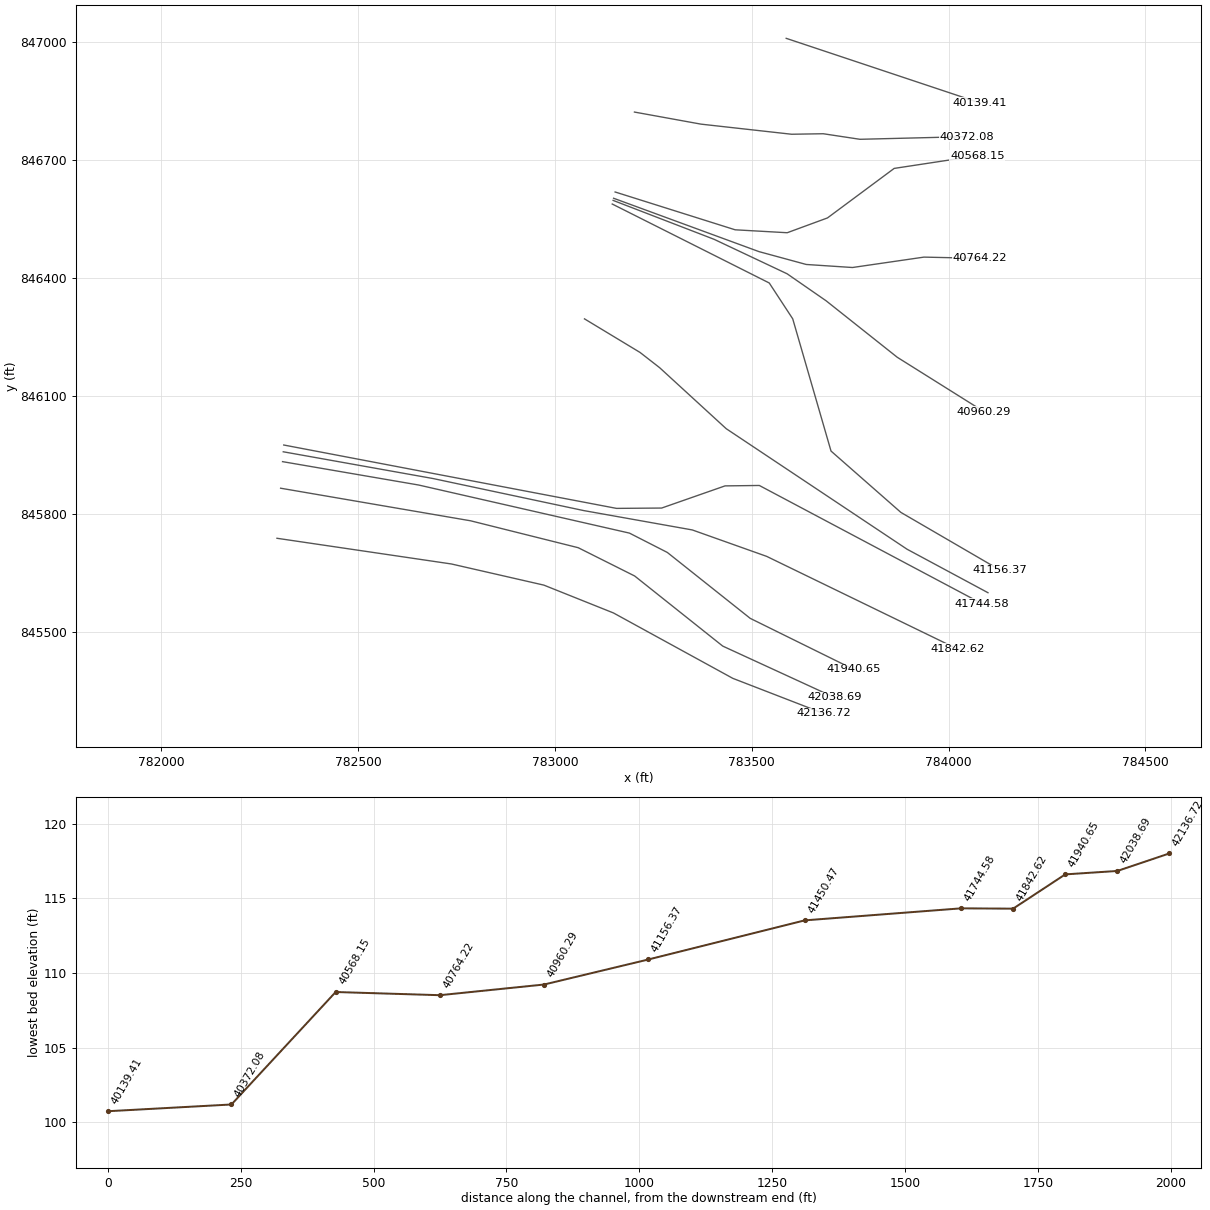
HEC-RAS study 15937_ras.prj: 15937

--- 15937_ras.g01 (geometry) --- (continued)

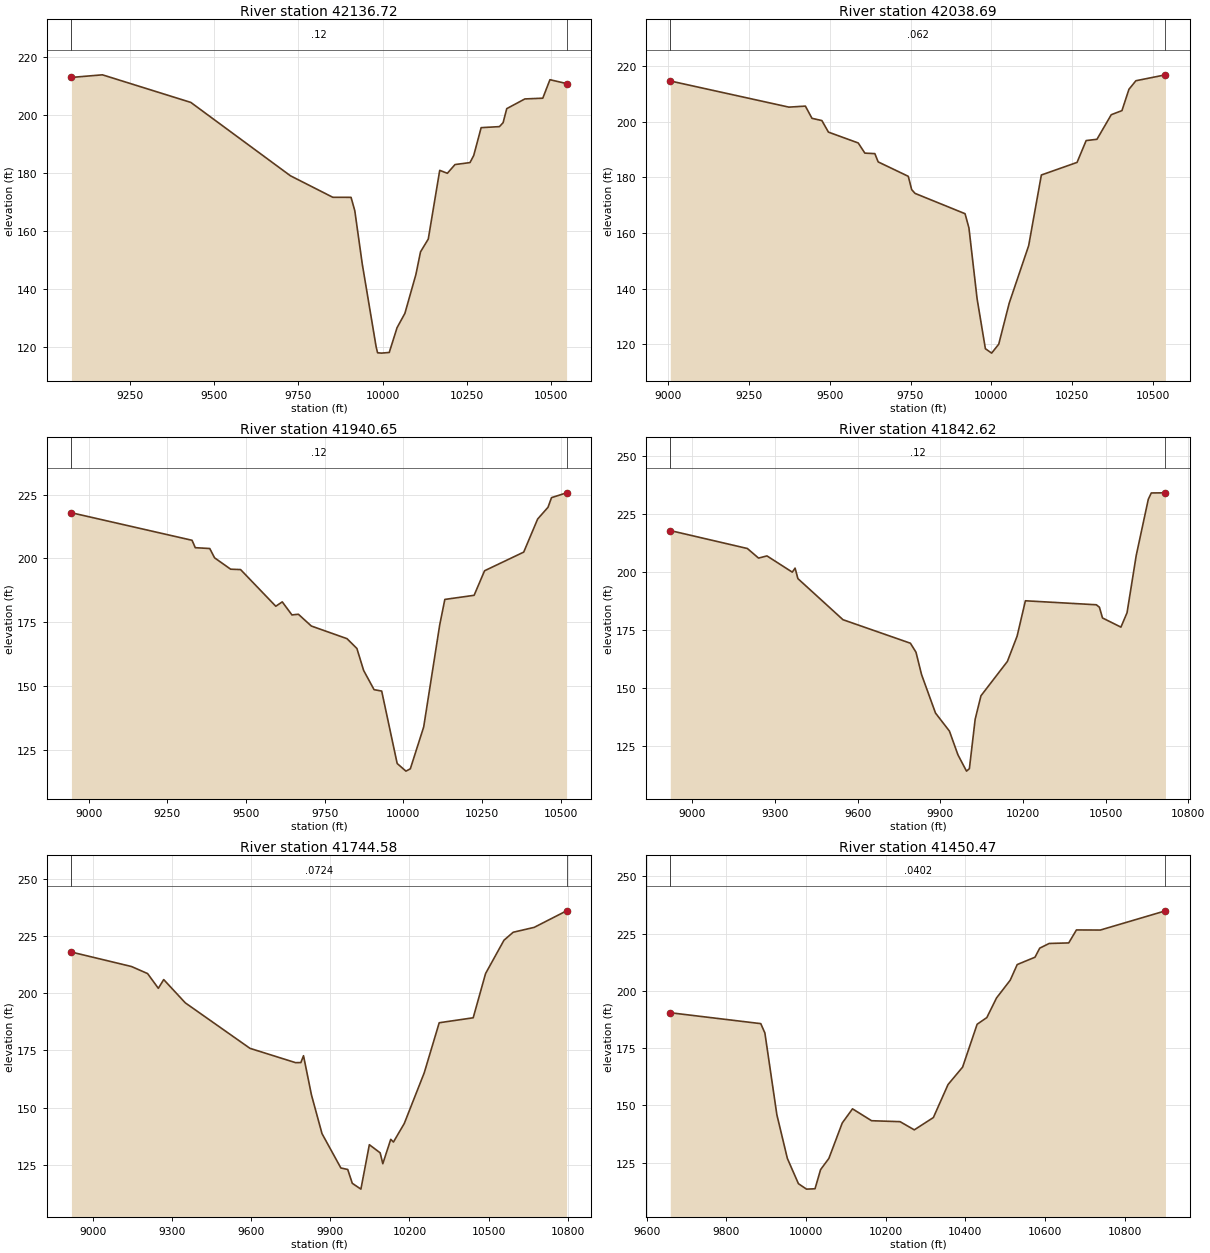
Type RM Length L Ch R = 1 ,42136.72,98.035900,98.035900,98.035900
XS GIS Cut Line= 6
782293.480961567845737.764553285782736.644558106845672.479665819
782971.707433881845618.711650424 783148.45779087845548.008068169
783451.843284273845381.784043651783681.650862925845292.853796236
#Sta/Elev= 30
 9074.84 212.9849167.074213.88089429.953204.37549726.063179.11289852.147171.6975
9906.388  171.689917.515167.09049939.768148.71359981.066120.16619985.273118.1482
9996.775118.019110020.02118.249810043.27126.803610066.52131.714110099.24145.0954
10113.01152.909210136.07157.316610170.12180.978710192.82179.967210215.52 182.969
10260.08183.650610271.16186.077810293.31195.688510347.73196.038610358.58197.3975
10369.43202.232310423.28205.575310476.59205.831110497.91212.203310547.39210.8668
#Mann= 3 , 0 , 0
 9074.84    0.12       0 9074.84    0.12       010547.39    0.12       0
#XS Ineff= 2 , 0
       0                               0
Bank Sta=9074.84,10547.39
Exp/Cntr=0.3,0.1

Type RM Length L Ch R = 1 ,42038.69,98.035800,98.035800,98.035800
XS GIS Cut Line= 6
782302.732267276845864.970006726 782785.31816581845782.199199904
783058.946069679845713.774115673 783202.38656461 845641.90086294
783426.103860384845463.801628685783709.756648522 845333.32612749
#Sta/Elev= 30
9006.656214.62419373.747205.22619424.709205.58949445.094201.20639475.671   200.4
9496.055196.24459588.178  192.359608.689188.70329639.615188.51959649.923185.5466
9743.092180.3667 9753.54175.59829763.988174.2337 9918.73166.93569930.777  161.81
9956.048 136.3299981.659118.4296   10001116.841810022.98120.058610055.43134.8267
10115.55155.447310154.86180.840110265.32185.370410293.46193.210810326.88193.6721
10371.13202.505410404.22203.975410425.82211.623710447.42 214.70910538.84216.8329
#Mann= 3 , 0 , 0
9006.656   0.062       09006.656   0.062       010538.84   0.062       0
#XS Ineff= 2 , 0
       0                               0
Bank Sta=9006.656,10538.84
Exp/Cntr=0.3,0.1

Type RM Length L Ch R = 1 ,41940.65,98.035900,98.035900,98.035900
XS GIS Cut Line= 6
782307.641113988845932.466648983 782653.47588197845873.071090912
783189.092232154845750.887613388783285.308986635845701.753789001
783495.918038303845534.284574529783759.160823634 845404.46813964
#Sta/Elev= 30
8945.448217.90059328.582207.10339338.798204.20499384.837203.87629400.091200.2355
9451.168195.77249482.736195.62219594.555181.24819615.077182.9649 9645.86177.8462
9666.381178.11019707.425173.49669820.818168.53699852.206164.68269873.586156.0769
9906.716 148.5429930.931147.99749980.097119.601910007.89116.611910021.83117.5114
10064.29133.9134 10115.3173.997610131.49183.921510224.46185.532910257.66195.1616
10382.01202.472510426.23215.433210459.25220.057210470.25223.817310518.19225.7109
#Mann= 3 , 0 , 0
8945.448    0.12       08945.448    0.12       010518.19    0.12       0
#XS Ineff= 2 , 0
       0                               0
Bank Sta=8945.448,10518.19
Exp/Cntr=0.3,0.1

Type RM Length L Ch R = 1 ,41842.62,98.035800,98.035800,98.035800
XS GIS Cut Line= 6
782309.463194754845957.520259496782690.460654406845889.471145595
783072.187727559845808.271539492 783348.75728069845758.939140178
783537.638277501 845691.81642827784022.006766759845456.647465911
#Sta/Elev= 30
8919.808218.01169199.518210.28379240.237206.14959270.776207.08369362.633200.0891
9372.857201.81589383.081197.29469546.661179.58719791.442 169.4539811.685165.5912
9831.929 155.9399882.538139.35659933.147131.56859964.034121.33869995.135114.3139
10005.58115.378410026.59136.7044 10047.6146.799510143.58161.612310178.78172.4828
10208.93187.744410466.34186.024310477.58184.960810488.81180.340210555.69176.3861
10577.92182.600810611.25207.296210655.03231.478910665.97234.223210717.35234.2788
#Mann= 3 , 0 , 0
8919.808    0.12       08919.808    0.12       010717.35    0.12       0
#XS Ineff= 2 , 0
       0                               0
Bank Sta=8919.808,10717.35
Exp/Cntr=0.3,0.1

Type RM Length L Ch R = 1 ,41744.58,294.107500,294.107500,294.107500
XS GIS Cut Line= 6
782310.715771502845974.743189778783156.222604154845813.701177319
783270.861534312845814.554527492783431.951506812845870.875562781
783519.074679702845871.927416688784084.815549061845571.599388251
#Sta/Elev= 30
8918.544218.02179146.155211.70269207.269  208.619248.012202.16719268.384205.9805
9350.134195.81369595.512175.90219768.167169.65069788.273169.69419798.288172.6857
9828.334 155.5729868.391138.60289939.873 123.5839965.881122.92689983.183116.8803
10015.83114.334510047.82133.770510088.81130.204610098.89125.453210128.96136.1261
10139.05134.923910180.22143.0373 10255.9165.217510312.65187.105110441.46189.2725
10488.41208.630610558.18223.204810592.91226.679510672.69228.824610795.47236.0573
#Mann= 3 , 0 , 0
8918.544  0.0724       08918.544  0.0724       010795.47  0.0724       0
#XS Ineff= 2 , 0
       0                               0
Bank Sta=8918.544,10795.47
Exp/Cntr=0.3,0.1

Type RM Length L Ch R = 1 ,41450.47,294.107600,294.107600,294.107600
XS GIS Cut Line= 6
783074.814641887846295.264725436783216.035924087846209.914650218
783265.716139813846171.261789385783434.847802155846016.271308812
783894.313753298 845710.03501549784100.036886309845599.457307369
#Sta/Elev= 30
9658.972190.44449886.176 185.6969896.513181.64519926.631145.95249953.021126.8983
9980.733115.9126   10001113.527710022.44113.6832 10036.4122.030610057.27126.9354
10090.86142.3897 10116.6148.542210164.47143.3566   10236142.943810271.77139.3755
10319.66144.739510356.55159.146710393.06  166.7310429.57185.421810453.91 188.343
10478.25196.893510512.66204.643410530.21211.456110574.86214.656410586.71 218.608
10610.41220.6526 10659.6220.892210678.93226.552810738.98226.506410902.51234.8874
#Mann= 3 , 0 , 0
9658.972  0.0402       09658.972  0.0402       010902.51  0.0402       0
#XS Ineff= 2 , 0
       0                               0
Bank Sta=9658.972,10902.51
Exp/Cntr=0.3,0.1

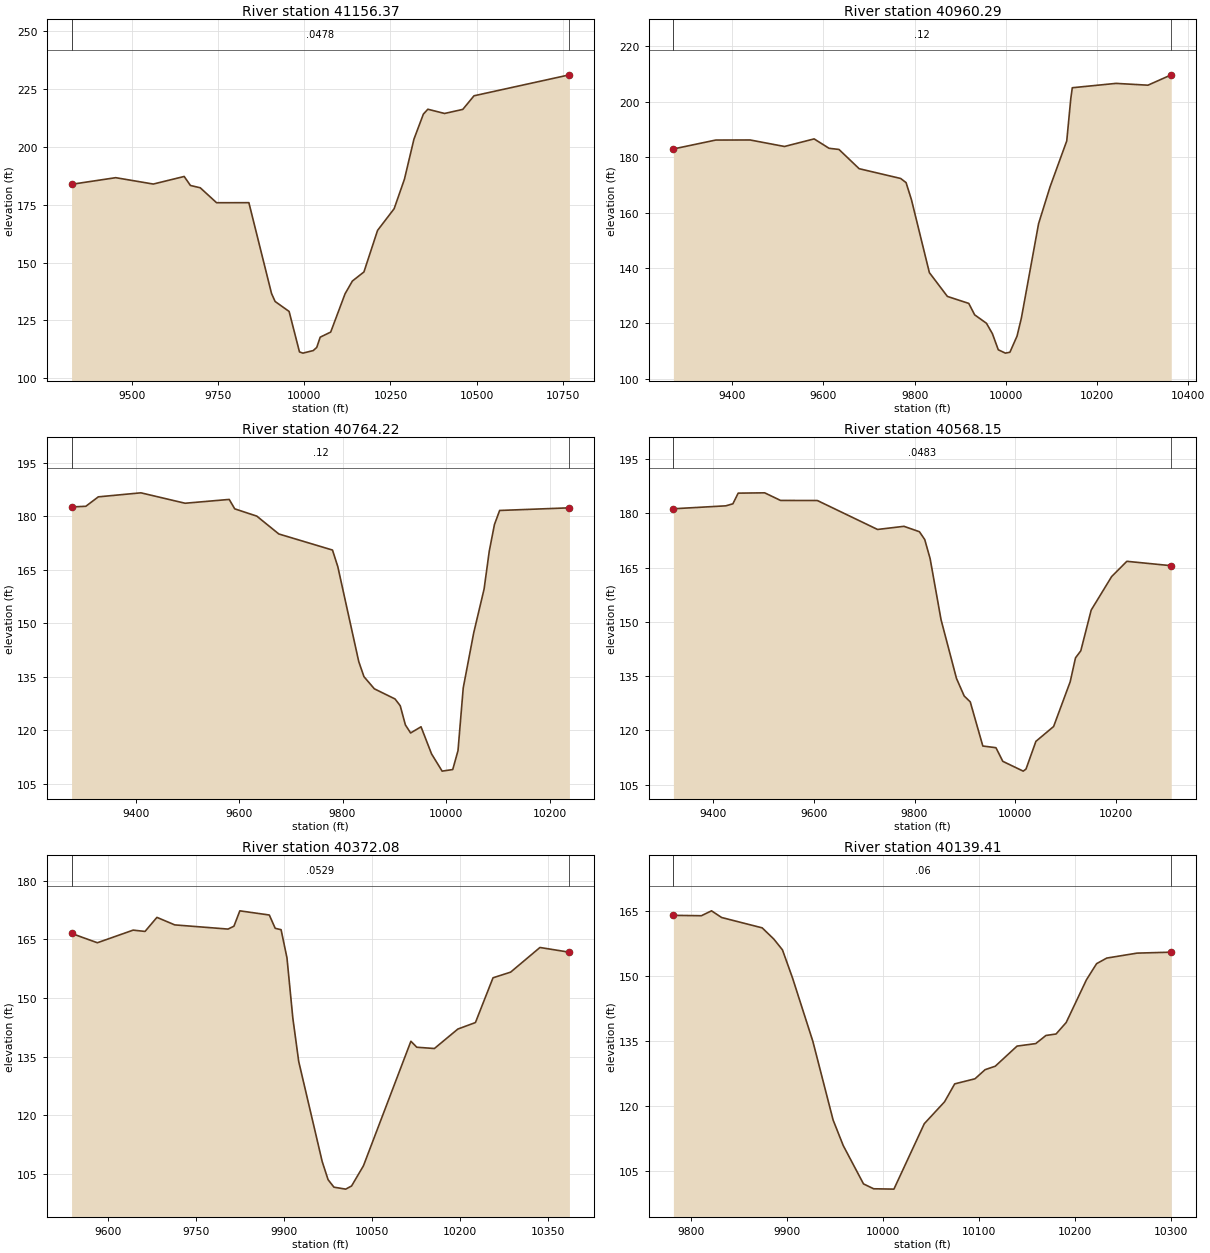
Type RM Length L Ch R = 1 ,41156.37,196.071700,196.071700,196.071700
XS GIS Cut Line= 6
783145.329992869846587.052384661783544.304622233846386.413709879
783603.958050311846295.317516074783701.236221761845959.375731006
783878.750890404845803.501868367784131.245967956845656.575815297
#Sta/Elev= 30
9324.443183.80059452.622186.66339561.614183.91269651.298187.1864 9669.52183.2938
9697.787 182.3139745.295175.85259839.055175.87099904.765136.66799915.181133.2098
9955.825128.8985 9985.91111.42779995.911110.904510025.94112.013110035.97113.3599
10046.05117.7939 10076.5119.992610118.14  136.5110139.46142.037710172.93145.9538
10212.49163.893910260.71173.284410290.51 186.01410318.11203.299810345.49214.1283
10358.48216.217910406.96214.391610459.86216.149510492.39 222.02610769.33 231.078
#Mann= 3 , 0 , 0
9324.443  0.0478       09324.443  0.0478       010769.33  0.0478       0
#XS Ineff= 2 , 0
       0                               0
Bank Sta=9324.443,10769.33
Exp/Cntr=0.3,0.1

Type RM Length L Ch R = 1 ,40960.29,196.071600,196.071600,196.071600
XS GIS Cut Line= 6
783147.560977588846596.284045566783404.091196358846497.407224625
783589.696832985 846409.77688922   783688.793219 846341.15445219
783869.526888788 846197.67652607784089.789462954846059.529247195
#Sta/Elev= 30
9270.842182.9658 9363.75186.18179439.089186.21189514.477183.86039579.509186.5988
9612.221183.20929634.028182.78729678.245175.83829769.302172.30549781.146170.8154
9792.991164.63059832.283138.30629871.814129.70449918.697127.18299931.646123.0473
9957.544119.99969970.492116.25959983.441110.4368    9999109.226210008.91109.5438
10024.54115.373310034.06121.874210071.78155.956610096.92169.267910133.59185.8709
10142.46201.149710145.75 205.075 10241.7206.648810311.68205.996710362.83209.7401
#Mann= 3 , 0 , 0
9270.842    0.12       09270.842    0.12       010362.83    0.12       0
#XS Ineff= 2 , 0
       0                               0
Bank Sta=9270.842,10362.83
Exp/Cntr=0.3,0.1

Type RM Length L Ch R = 1 ,40764.22,196.071700,196.071700,196.071700
XS GIS Cut Line= 6
783148.866647584846601.686817964783518.081807911846466.154909194
783638.306106538846433.461408362783755.736861199846425.744218141
783937.314503282846452.151498929784079.759188414846449.038242877
#Sta/Elev= 30
9276.243 182.5899303.828182.77939327.962185.42439410.287186.55239495.617183.6316
9580.948 184.7029591.614182.06159634.279 180.0199676.814175.0141 9780.55170.5039
 9790.83165.85189831.324139.2208 9841.36135.00349861.424131.59639901.425128.7445
9911.425126.86199921.483121.45729931.545119.21089951.671120.94439972.008113.3412
9992.453108.510410012.93108.952810023.13114.260710033.24131.848410053.46147.2686
10073.52159.552710083.56 170.21410093.59177.6694 10103.6181.604710238.48182.3445
#Mann= 3 , 0 , 0
9276.243    0.12       09276.243    0.12       010238.48    0.12       0
#XS Ineff= 2 , 0
       0                               0
Bank Sta=9276.243,10238.48
Exp/Cntr=0.3,0.1

Type RM Length L Ch R = 1 ,40568.15,196.071700,196.071700,196.071700
XS GIS Cut Line= 6
 783152.71565751846617.613755589783457.630617201846521.565689802
783589.922152847846514.115678668783692.254942864846551.737181544
783861.705964029846677.538893998784073.048018932846709.655322418
#Sta/Elev= 30
9320.805181.26789425.142182.08289439.013182.6403 9449.54185.58899502.178185.6768
 9533.76183.57039606.891183.55069726.486175.54759778.974176.41399809.756174.9184
9820.308172.75089830.984167.47619852.726150.5707  9883.4134.34019898.706129.4958
9910.715127.87539935.731115.66549961.805115.19679975.412111.430810015.97108.7236
10021.54 109.29610041.22116.9606 10076.4121.063510109.33133.429310119.87140.0349
10130.41141.995210151.05153.254710191.73 162.52710221.94166.740310310.19165.5259
#Mann= 3 , 0 , 0
9320.805  0.0483       09320.805  0.0483       010310.19  0.0483       0
#XS Ineff= 2 , 0
       0                               0
Bank Sta=9320.805,10310.19
Exp/Cntr=0.3,0.1

Type RM Length L Ch R = 1 ,40372.08,232.667800,232.667800,232.667800
XS GIS Cut Line= 6
783201.797674567846820.711757228783370.999514431846790.002995029
783601.014619052 846764.34956345783681.471710742846765.642129257
783774.771613896846751.515563712784045.271618605846758.260477439
#Sta/Elev= 30
9537.724166.49589581.735164.1214 9642.74167.34249663.031167.01069683.322170.6039
 9713.74168.68249804.615167.61229814.673168.3522 9824.73172.27529875.016 171.203
9885.048167.81019895.077 167.4529905.105160.27559915.133144.84919925.162 133.776
9965.216108.21379975.219 103.5999985.233101.677710005.28101.181210015.28101.9823
10035.54107.139910116.49138.963510126.49137.429910156.51137.099810196.53142.0711
10226.54143.733910256.55155.170910286.57156.612310336.58162.911610386.85161.6991
#Mann= 3 , 0 , 0
9537.724  0.0529       09537.724  0.0529       010386.85  0.0529       0
#XS Ineff= 2 , 0
       0                               0
Bank Sta=9537.724,10386.85
Exp/Cntr=0.3,0.1

Type RM Length L Ch R = 1 ,40139.41,158.536300,158.536300,158.536300
XS GIS Cut Line= 2
783587.380311668847008.044288322784078.711896777846844.267093286
#Sta/Elev= 30
9781.986163.97229811.099163.8845 9821.64165.01689832.181163.47289874.345161.0826
9886.481158.48769895.427156.00019905.968149.4719 9927.05134.87319948.131116.6895
9958.672110.78679979.754101.93439990.295100.809610011.38100.7281   10043115.8498
10064.08120.907510074.62125.0439 10095.7126.216110106.25128.324110116.79129.1207
10139.46133.768610158.95134.351310169.49 136.22210180.03136.561910190.57139.2132
10211.65149.0871 10222.2152.809110232.74154.100710264.36155.246710299.89155.4655
#Mann= 3 , 0 , 0
9781.986    0.06       09781.986    0.06       010299.89    0.06       0
#XS Ineff= 2 , 0
       0                               0
Bank Sta=9781.986,10299.89
Exp/Cntr=0.3,0.1