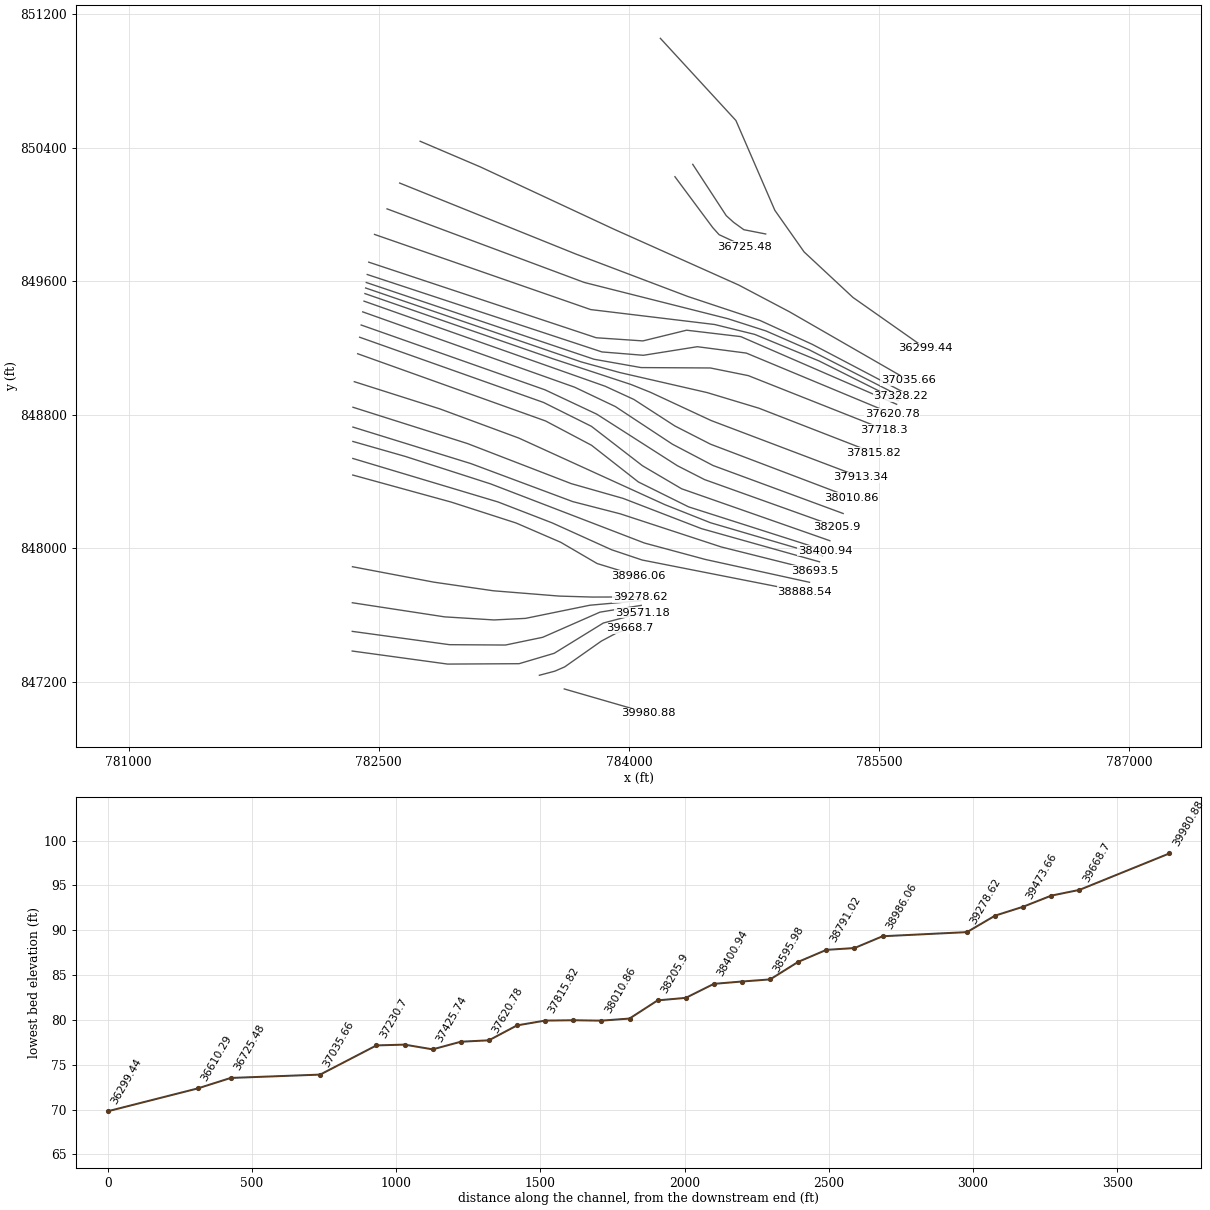
HEC-RAS study 15937_ras.prj: 15937

--- 15937_ras.g01 (geometry) --- (continued)

Type RM Length L Ch R = 3 ,40055.81,,,
BEGIN DESCRIPTION:
END DESCRIPTION:
Bridge Culvert--1,0,-1,-1, 0
Deck Dist Width WeirC Skew NumUp NumDn MinLoCord MaxHiCord MaxSubmerge Is_Ogee
57.468150,43.600000,2.6,0, 20, 20, , , 0.95, 0, 0,0,,
 9773.93 9782.78 9793.24 9793.34 9803.90 9814.46 9824.29 9825.03 9835.59 9844.66
 9888.97 9888.9710217.9710217.9710232.3710236.9810247.5410258.1010258.9910261.28
  163.35  163.23  162.94  162.94  162.70  162.53  162.37  162.35  162.10  161.93
  161.00  161.00  154.12  154.12  153.82  153.74  153.60  153.50  153.48  153.43
 -836.65 -836.77 -837.06 -837.06 -837.30 -837.47 -837.63 -837.65 -837.90 -838.07
 -839.00  156.00  149.12 -845.88 -846.18 -846.26 -846.40 -846.50 -846.52 -846.57
 9773.93 9782.78 9793.24 9793.34 9803.90 9814.46 9824.29 9825.03 9835.59 9844.66
 9876.83 9876.8310205.8310205.8310232.3710236.9810247.5410258.1010258.9910261.28
  163.35  163.23  162.94  162.94  162.70  162.53  162.37  162.35  162.10  161.93
  161.25  161.25  154.37  154.37  153.82  153.74  153.60  153.50  153.48  153.43
 -836.65 -836.77 -837.06 -837.06 -837.30 -837.47 -837.63 -837.65 -837.90 -838.07
 -838.75  156.25  149.37 -845.63 -846.18 -846.26 -846.40 -846.50 -846.52 -846.57
Pier Skew, UpSta & Num, DnSta & Num=  ,9970.22, 2 ,9958.08, 2 , 0 , 0 , 0 ,,
    4.00    4.00
 -840.70  159.30
    4.00    4.00
 -840.45  159.55
Pier Skew, UpSta & Num, DnSta & Num=  ,10053.47, 2 ,10041.33, 2 , 0 , 0 , 0 ,,
    4.00    4.00
 -842.44  157.56
    4.00    4.00
 -842.19  157.81
Pier Skew, UpSta & Num, DnSta & Num=  ,10136.72, 2 ,10124.58, 2 , 0 , 0 , 0 ,,
    4.00    4.00
 -844.18  155.82
    4.00    4.00
 -843.93  156.07
BR Coef=-1 , 0 , 0 ,, 0 ,,,0.8,0,1,0,
WSPro=,,,, 1 ,,,, 0 ,,,, 0 ,,,,-1 ,-1 ,-1 , 0 , 0 , 0 , 0 , 0
BC Design=,, 0 ,, 0 ,,,,,,

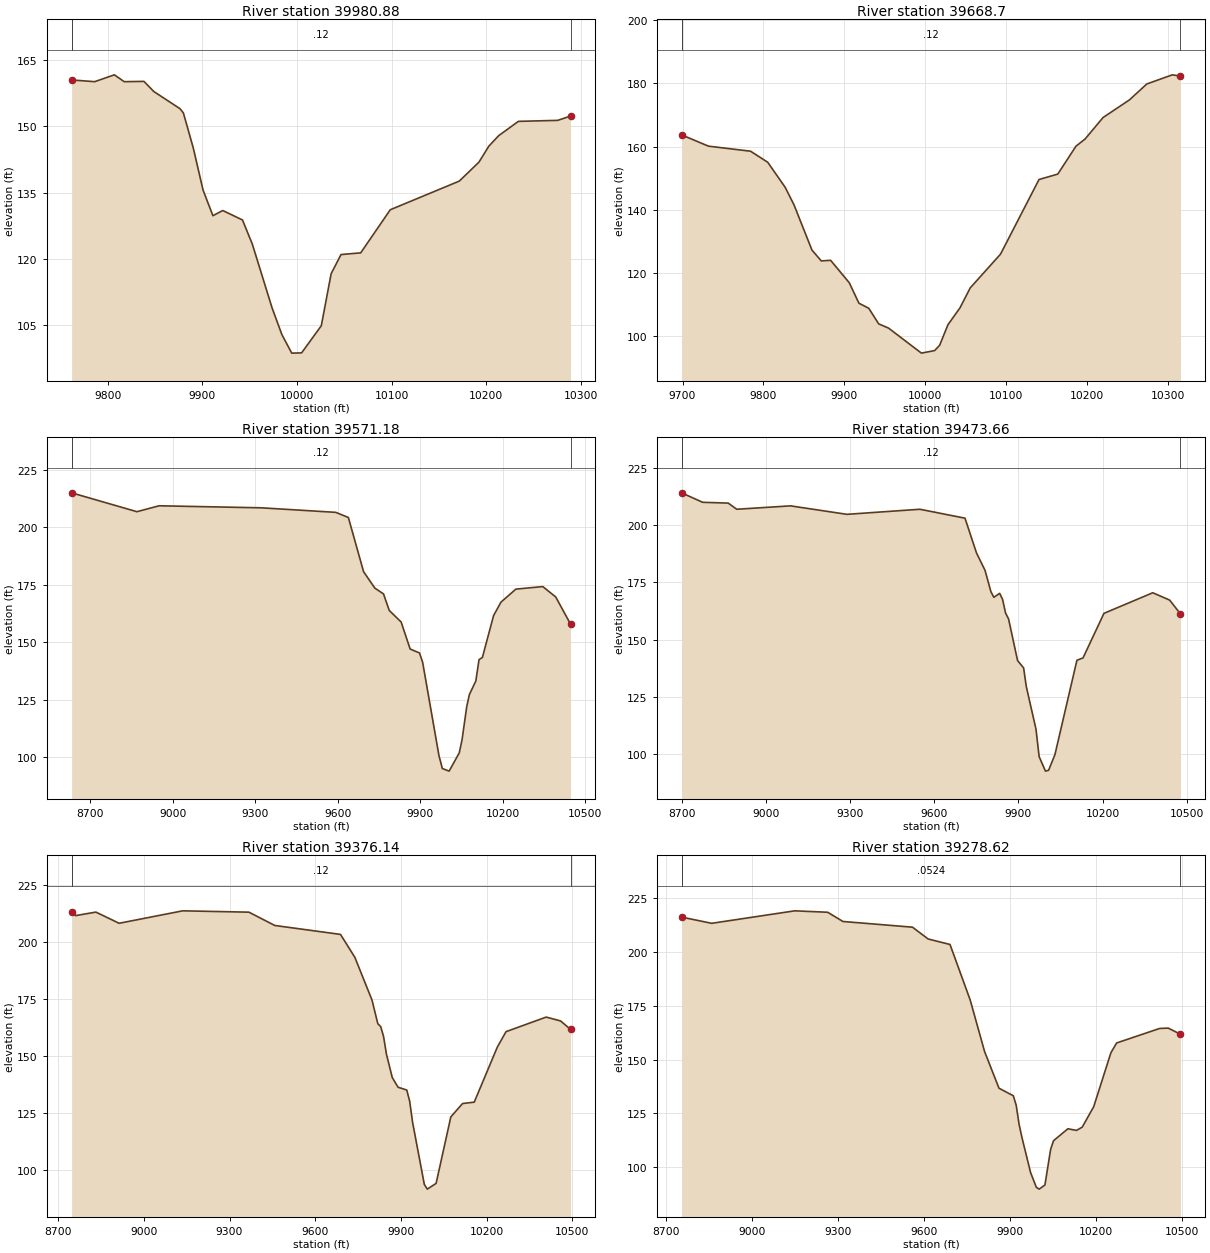
Type RM Length L Ch R = 1 ,39980.88,312.170900,312.170900,312.170900
XS GIS Cut Line= 2
783611.600882739847156.827796459784117.926154703847010.351009354
#Sta/Elev= 30
9761.951 160.529 9786.31 160.141 9807.13161.6928 9817.54160.1375 9838.36160.2083
 9848.77157.91129876.481 154.009    9880153.0706 9890.41145.1769 9900.82135.5542
 9911.23 129.746 9921.64130.9171 9942.46128.7787 9952.87123.30699973.691108.8668
9984.101102.77989994.51198.5777810004.9298.6303610025.74104.789110036.15116.5926
10046.56120.931710067.38121.317110098.61131.094310171.48137.5852 10192.3141.8915
10202.71 145.50910213.12 147.88810233.94151.138610275.58151.365510289.04152.3498
#Mann= 3 , 0 , 0
9761.951    0.12       09761.951    0.12       010289.04    0.12       0
#XS Ineff= 2 , 0
       0                               0
Bank Sta=9761.951,10289.04
Exp/Cntr=0.3,0.1

Type RM Length L Ch R = 1 , 39668.7,97.520100,97.520100,97.520100
XS GIS Cut Line= 6
783462.455083296847238.857178152783554.565094969847263.250959962
783614.128711177847289.000940999783833.884524162847443.611262283
783920.385599163847489.782250555  784004.6201109847520.613103333
#Sta/Elev= 30
9698.805163.70029732.047160.12039784.221158.51199805.436155.00639826.968147.0898
9837.956141.49259860.131127.18129871.682123.73419883.234123.93019906.336116.8059
9918.219110.33749930.439108.72129942.658103.78869954.877102.44289995.56794.50671
 10011.995.3147510018.0996.9927510028.34103.4934 10043.3108.8702 10055.9115.1693
10093.44125.894210141.06149.545910164.26151.261510186.81160.117510197.96162.3575
10220.28169.194810252.83 174.76510274.39179.825910305.93182.728410316.04182.3363
#Mann= 3 , 0 , 0
9698.805    0.12       09698.805    0.12       010316.04    0.12       0
#XS Ineff= 2 , 0
       0                               0
Bank Sta=9698.805,10316.04
Exp/Cntr=0.3,0.1

Type RM Length L Ch R = 1 ,39571.18,97.520000,97.520000,97.520000
XS GIS Cut Line= 6
782340.322402954847384.117614567782911.993279815847305.873938531
783340.671351939847308.172329009783551.344329447 847370.55956544
783845.953102648847552.082498595 784078.19726786847613.064022869
#Sta/Elev= 30
8631.884214.88128869.428 206.6788950.244209.24679322.279208.36019592.621206.3903
9638.589204.16149693.884180.60229735.007173.42899766.396170.93219787.322163.7309
9830.505 158.7149863.273146.96219897.365145.24859908.729141.20529968.101100.6223
9980.423 94.998110005.0893.8679110041.93101.806510052.03107.451510069.25122.0208
10078.78127.160510102.18133.065110113.85142.341810126.08143.286910166.68161.4637
10193.61167.343110247.86173.008910345.75174.108310392.79169.608510446.66157.8088
#Mann= 3 , 0 , 0
8631.884    0.12       08631.884    0.12       010446.66    0.12       0
#XS Ineff= 2 , 0
       0                               0
Bank Sta=8631.884,10446.66
Exp/Cntr=0.3,0.1

Type RM Length L Ch R = 1 ,39473.66,97.520000,97.520000,97.520000
XS GIS Cut Line= 6
782340.700255066847502.007463738 782923.42470786847422.191056162
783259.090903163847420.040180594783482.563232362847466.465751573
783825.295280159847617.054323062784073.148046434 847657.87586309
#Sta/Elev= 30
8698.162214.15698773.464210.02068864.678209.66958895.082206.98479086.965208.4662
9288.089204.76479548.319206.98159709.257203.08459750.117187.9585 9780.82 180.278
9801.633 171.0069812.075168.5404 9832.96170.25799843.403 167.5999853.914161.6736
9864.639159.09729896.816140.90429918.384137.6961 9927.88129.56599962.549110.9099
9973.69898.963719996.25492.6289410007.55 93.0008 10030.1 99.851610108.48141.0228
10130.42142.087110204.95161.527510379.14 170.521 10439.5167.302310477.87 161.276
#Mann= 3 , 0 , 0
8698.162    0.12       08698.162    0.12       010477.87    0.12       0
#XS Ineff= 2 , 0
       0                               0
Bank Sta=8698.162,10477.87
Exp/Cntr=0.3,0.1

Type RM Length L Ch R = 1 ,39376.14,97.520100,97.520100,97.520100
XS GIS Cut Line= 6
782341.249900788847673.496940508782893.871114999847588.954530895
783190.534750998847570.425104648 783379.69659403847579.899217755
783765.353932887847658.707066596784069.978991181847686.001228705
#Sta/Elev= 30
8747.293213.35458761.253211.70858832.323213.25178913.517208.34499136.144213.8096
9367.833213.21929458.136207.38489688.288 203.4559738.409193.42539798.626174.6171
  9818.8164.27149828.887162.98689838.975158.65549849.062150.87719869.329  140.65
9889.649136.36429920.129135.14199930.361130.22499940.626120.91219981.683 93.6796
9991.94891.6322410022.8594.1508610074.37123.338310115.49129.211710156.26129.8071
 10237.3 154.02710267.57160.763810408.18167.156110458.27165.476710493.27161.7855
#Mann= 3 , 0 , 0
8747.293    0.12       08747.293    0.12       010493.27    0.12       0
#XS Ineff= 2 , 0
       0                               0
Bank Sta=8747.293,10493.27
Exp/Cntr=0.3,0.1

Type RM Length L Ch R = 1 ,39278.62,292.560100,292.560100,292.560100
XS GIS Cut Line= 6
782341.942207247847889.496540576 782829.18059057  847797.0773146
783186.485743761847745.274426132783581.637601107847713.454653814
783778.365014523847707.650404513 784067.46560517847708.307529181
#Sta/Elev= 30
8755.501216.14648860.576213.25379150.357219.05419265.046218.38949318.048214.1077
9560.618  211.469615.147205.98259691.463203.42359761.785177.6625 9811.95153.7222
9862.115136.67949912.214  133.169922.231128.75879932.248119.92429942.265113.7634
9972.31697.51617 9992.3590.6549910002.3789.7939410022.3991.7121510042.39108.3413
 10052.4112.280210102.42117.828310132.43117.070310152.44118.586710192.46128.0866
10252.47153.158410272.47157.681710422.47164.427210452.47164.577310494.93161.7373
#Mann= 3 , 0 , 0
8755.501  0.0524       08755.501  0.0524       010494.93  0.0524       0
#XS Ineff= 2 , 0
       0                               0
Bank Sta=8755.501,10494.93
Exp/Cntr=0.3,0.1

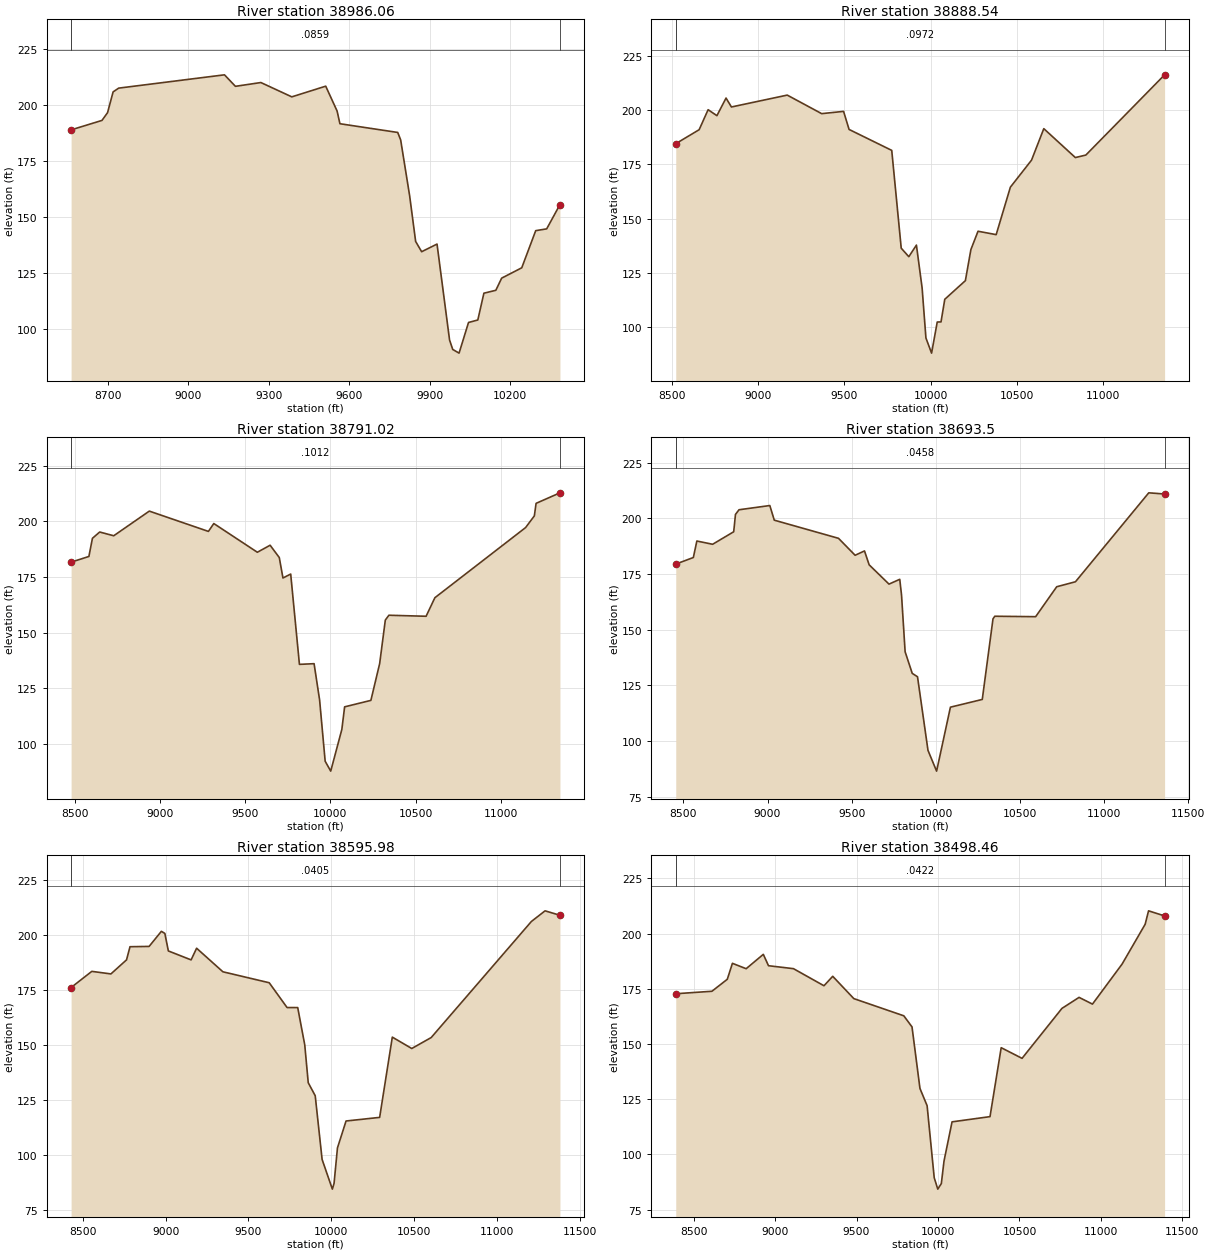
Type RM Length L Ch R = 1 ,38986.06,97.520000,97.520000,97.520000
XS GIS Cut Line= 6
782343.703999609848439.175757915 782934.19585821848276.872567624
783322.496735722848151.710929304783590.395464957848035.963127688
783808.681546867847908.561303332784053.334403217847833.721946627
#Sta/Elev= 30
8562.822188.86428677.937193.08668698.649196.53458719.362205.79968740.075207.4748
9134.473213.40829175.236208.28179270.083 209.9699385.402203.58429511.811 208.349
9554.156197.27959564.742191.60349780.161187.71759791.108 184.4089824.617159.4648
9846.956139.12479869.295134.54469926.655137.95339973.39795.17154  9985.290.97885
10008.7989.3343610044.06 103.00110078.65104.102810101.32 116.04810145.87117.3473
10167.57122.763810242.46127.380410294.44143.9289 10335.4144.736210384.79155.5561
#Mann= 3 , 0 , 0
8562.822  0.0859       08562.822  0.0859       010384.79  0.0859       0
#XS Ineff= 2 , 0
       0                               0
Bank Sta=8562.822,10384.79
Exp/Cntr=0.3,0.1

Type RM Length L Ch R = 1 ,38888.54,97.520100,97.520100,97.520100
XS GIS Cut Line= 6
782344.022502481848538.548665046783215.031510912 848277.53924155
783539.073359271848152.278464302783895.282528205847991.184443704
784078.711890377847929.653270344785053.258965992847737.841491195
#Sta/Elev= 30
8522.382184.51868658.041190.97748710.029200.19098761.025197.44258814.012205.5519
8845.207201.44589168.854206.91869368.509198.37769495.584199.41799527.474191.0937
9774.901181.44539829.917136.37689873.985132.45449918.052137.79899951.103 118.007
9973.137 94.999510005.9488.0172710038.75102.356710060.62102.398710082.49112.8299
10201.94121.406910233.91135.725710275.32144.1817 10380.6 142.61810462.92164.4913
10585.59176.944310656.75191.458410839.73178.131110900.73179.300411357.25 216.263
#Mann= 3 , 0 , 0
8522.382  0.0972       08522.382  0.0972       011357.25  0.0972       0
#XS Ineff= 2 , 0
       0                               0
Bank Sta=8522.382,11357.25
Exp/Cntr=0.3,0.1

Type RM Length L Ch R = 1 ,38791.02,97.520000,97.520000,97.520000
XS GIS Cut Line= 6
 782344.34919809 848640.47769497782659.178832477 848550.51008508
783169.961432472848386.088609789784092.784741231848031.374018815
784456.930015789847933.196941252785081.825796035847796.229304792
#Sta/Elev= 30
8477.916 181.6188582.342184.18368603.166 192.3328645.701195.15718728.116 193.475
 8937.02204.53939284.012195.42789315.659198.96159571.331186.07469646.348189.2223
9700.116183.69449721.623174.51849767.135176.28569818.405135.74079904.433136.0497
9936.881119.73569969.50492.2609110002.1687.8145310067.38106.523710083.72116.6723
10237.91119.572910289.46136.106810322.63155.617410343.62 157.79510562.04157.3363
10613.58165.655411146.36197.159411197.54202.391511207.78 208.02311347.86  212.75
#Mann= 3 , 0 , 0
8477.916  0.1012       08477.916  0.1012       011347.86  0.1012       0
#XS Ineff= 2 , 0
       0                               0
Bank Sta=8477.916,11347.86
Exp/Cntr=0.3,0.1

Type RM Length L Ch R = 1 , 38693.5,97.520000,97.520000,97.520000
XS GIS Cut Line= 6
782344.625316639  848726.6266819783052.360873137848507.538512129
783662.602668042848279.813408223 783947.02987632848206.642583573
784553.030025192848007.918277819 785116.36305647847866.820095628
#Sta/Elev= 30
8454.666179.39048559.222 182.3628580.056189.75858673.805188.29968799.043193.9135
8809.528201.69098830.496 203.7899013.594205.68869040.181199.1188 9421.81190.9732
9520.529183.36129576.187 185.3139603.977179.0722 9721.85170.41859785.773  172.57
9796.405165.4689 9817.67140.04789859.962130.34779891.288128.8369 9953.5595.79439
10004.7486.47681 10086.9115.181710276.14118.652610339.83154.806310350.45 155.993
 10593.3155.798710718.51169.238710829.88171.467711265.49211.391711359.59210.8622
#Mann= 3 , 0 , 0
8454.666  0.0458       08454.666  0.0458       011359.59  0.0458       0
#XS Ineff= 2 , 0
       0                               0
Bank Sta=8454.666,11359.59
Exp/Cntr=0.3,0.1

Type RM Length L Ch R = 1 ,38595.98,97.520100,97.520100,97.520100
XS GIS Cut Line= 6
782345.006128723848845.440051863783030.946366274848627.994800556
783653.647544416848387.518949401 783964.74228391848298.939406805
 784433.48306189848118.020706186785141.836964573847918.886278528
#Sta/Elev= 30
8429.988176.18098554.983183.52938670.178182.3657 8764.44188.76318785.387194.7386
8900.662194.87188974.531201.72848995.636200.77349016.742192.81799153.969188.7467
9187.241194.04449345.795183.3383 9625.28178.35149733.021167.07519797.269167.0629
9839.692150.10169860.731132.90099902.809126.97319944.385   98.0110006.1984.51732
10016.4887.1336710037.04103.269210088.84115.490410291.58 117.137   10368153.6312
 10485.4148.4567 10602.6153.438111206.87206.195211289.59 211.05611379.38209.0316
#Mann= 3 , 0 , 0
8429.988  0.0405       08429.988  0.0405       011379.38  0.0405       0
#XS Ineff= 2 , 0
       0                               0
Bank Sta=8429.988,11379.38
Exp/Cntr=0.3,0.1

Type RM Length L Ch R = 1 ,38498.46,97.520000,97.520000,97.520000
XS GIS Cut Line= 6
 782352.93122803848998.720093059782866.649831639848835.348602179
783339.505252089848660.584597884784214.805472836848261.499578525
 784488.00838441848153.189780492 785159.97575191847955.960190204
#Sta/Elev= 30
8390.714172.74948612.744 173.8768706.972179.29858738.483186.52188822.743184.0895
8928.069190.58848959.826185.44269112.977184.10799300.234176.36839353.951180.6477
9483.451170.54669790.149162.76429840.541157.73679889.265 129.8819933.139122.0618
 9976.7989.444089998.61684.2834310020.4586.80959   1003797.0324710086.25 114.745
 10319.2117.106710387.78148.325710515.81143.500210760.66166.120710865.72171.1093
10947.92168.059611129.58186.168911271.36204.227211292.09210.296411390.53207.9898
#Mann= 3 , 0 , 0
8390.714  0.0422       08390.714  0.0422       011390.53  0.0422       0
#XS Ineff= 2 , 0
       0                               0
Bank Sta=8390.714,11390.53
Exp/Cntr=0.3,0.1

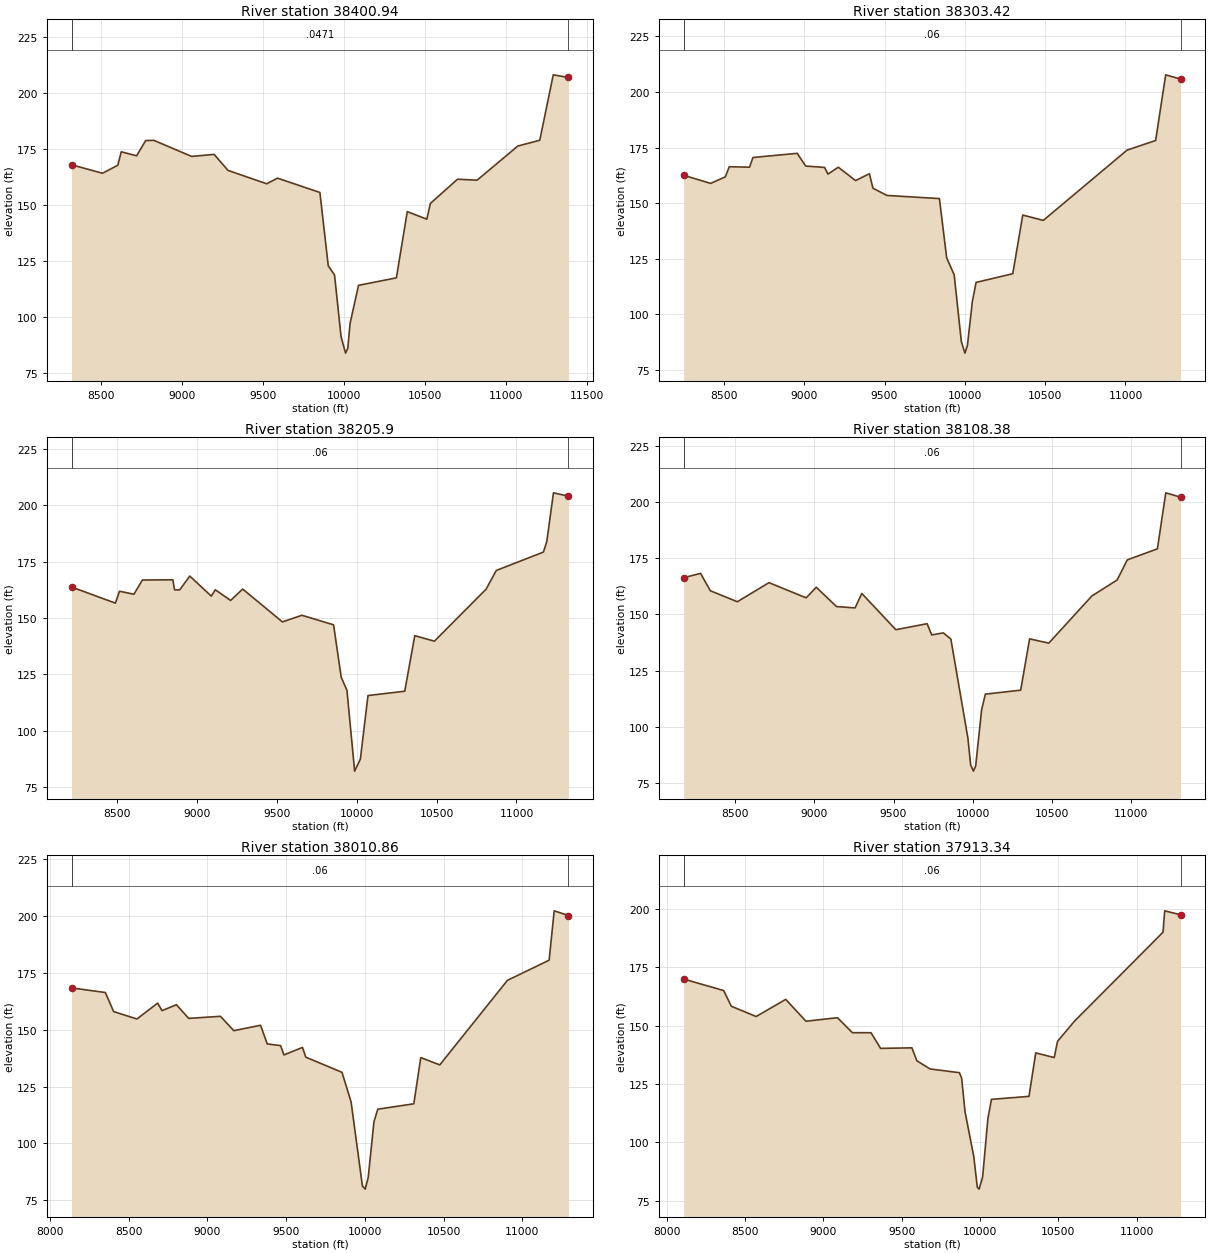
Type RM Length L Ch R = 1 ,38400.94,97.520000,97.520000,97.520000
XS GIS Cut Line= 6
782373.148653353849166.235902877783499.555309486848763.272728691
783775.145675446848617.521948043784055.712905344848397.692859172
784357.019396079848248.309548029785175.033502144847986.736762633
#Sta/Elev= 30
8320.903168.14478511.589164.35998606.274167.93348627.315173.93388722.083172.1512
8778.046178.94098827.866179.06339061.025171.8637 9199.63172.78099285.337165.6214
9523.848 159.6459590.258162.16069851.562155.76979903.069123.00489941.669118.9367
9981.91491.3209810009.5984.0216510023.6286.2613610037.4497.2963210089.52114.2927
10322.82117.644810389.95147.211110510.51143.834410532.27 150.87410699.75161.6991
10820.02161.249611071.28176.509811206.44179.091611289.54 208.31111383.07207.1345
#Mann= 3 , 0 , 0
8320.903  0.0471       08320.903  0.0471       011383.07  0.0471       0
#XS Ineff= 2 , 0
       0                               0
Bank Sta=8320.903,11383.07
Exp/Cntr=0.3,0.1

Type RM Length L Ch R = 1 ,38303.42,97.520100,97.520100,97.520100
XS GIS Cut Line= 6
782385.092303624849265.197576551783487.609324005848874.141342357
783774.453634979 848731.07033879784080.853764894848494.500000834
784315.007074312848356.770470214785203.769413545848045.470162031
#Sta/Elev= 30
 8249.63162.51648417.512158.84058509.248161.79958533.495166.34148660.021166.1451
8681.109170.49878956.471172.37599009.501166.64999126.728166.03169148.061163.0204
9212.252166.12629319.632160.11479406.162 163.2069427.905156.67859515.184153.4276
9841.783152.01079886.891125.38119933.761117.68259978.20787.6851610000.6982.45732
10016.0885.8750410046.82105.648110070.04114.2832 10298.6118.201210360.64144.5985
10488.45142.195211010.29173.8368 11187.8178.152311250.39207.710111342.99205.7903
#Mann= 3 , 0 , 0
 8249.63    0.06       0 8249.63    0.06       011342.99    0.06       0
#XS Ineff= 2 , 0
       0                               0
Bank Sta=8249.63,11342.99
Exp/Cntr=0.3,0.1

Type RM Length L Ch R = 1 , 38205.9,97.520000,97.520000,97.520000
XS GIS Cut Line= 6
782393.944492341849338.544283061783496.288804463848949.879345711
783806.287376925848804.096949113784289.684519873848495.046267019
784452.698021547848411.780730389785244.381898706848128.478119501
#Sta/Elev= 30
8215.175163.72568489.873156.58658515.433161.84588605.922160.52538658.802166.8265
8849.402166.9028 8860.02 162.4778891.872162.42918955.576168.56969089.978159.6938
9115.093162.50329211.126157.7742 9286.26162.82339535.127148.27089657.423151.2028
9855.402146.97049903.305123.73939939.232117.96049987.13582.1780910023.0287.49914
10070.88115.649610300.88117.5727 10363.6142.171310486.47139.736510810.12162.7745
10873.73171.052511168.75179.199211189.72183.814611231.66205.440211325.37203.9621
#Mann= 3 , 0 , 0
8215.175    0.06       08215.175    0.06       011325.37    0.06       0
#XS Ineff= 2 , 0
       0                               0
Bank Sta=8215.175,11325.37
Exp/Cntr=0.3,0.1

Type RM Length L Ch R = 1 ,38108.38,97.520000,97.520000,97.520000
XS GIS Cut Line= 6
782403.442747573849417.244112127783673.764676378848965.659967068
 783917.79743313848849.743533752784259.964904903848623.999947952
784503.627428076848496.155506204785283.561682161848208.557774461
#Sta/Elev= 30
 8175.44166.39438282.239 168.333 8343.83160.58748514.325155.68388714.021164.1945
8948.645157.42059012.432162.15169140.007153.52879257.184152.93869299.898159.3666
9514.421143.22039711.811145.88479740.937140.88789814.246141.78959861.593139.0861
9969.36294.808939986.675 82.891210003.9580.1501110018.3382.4485210055.71107.4368
10079.27114.484710302.27116.246510358.62 139.12810479.56137.220910751.38158.2456
10911.28165.399610974.87174.336311165.05179.278211217.88204.248211311.21 202.304
#Mann= 3 , 0 , 0
 8175.44    0.06       0 8175.44    0.06       011311.21    0.06       0
#XS Ineff= 2 , 0
       0                               0
Bank Sta=8175.44,11311.21
Exp/Cntr=0.3,0.1

Type RM Length L Ch R = 1 ,38010.86,97.520100,97.520100,97.520100
XS GIS Cut Line= 6
782411.206357115849481.571162612783856.892697196 848971.38876918
   784028.703716848892.371304049784274.936862948848733.121304207
784488.396141357848624.045471729785330.419312504848304.330199398
#Sta/Elev= 30
8136.747168.3445 8351.62166.32858404.375157.93078552.484154.68868683.852161.6588
8711.421158.35648803.254160.94948881.234154.95559082.886155.86319167.792149.5514
9337.604151.93259380.057143.72219464.963142.97939486.192138.89929603.753142.1825
9625.128137.91049854.938131.24119912.772118.19539984.56781.3314910002.3179.91441
10021.5685.1079310057.88109.5136 10082.1115.037810311.02117.415710355.31137.7124
10475.86134.506510905.46171.658711170.62180.5291 11202.7202.225211293.25200.1686
#Mann= 3 , 0 , 0
8136.747    0.06       08136.747    0.06       011293.25    0.06       0
#XS Ineff= 2 , 0
       0                               0
Bank Sta=8136.747,11293.25
Exp/Cntr=0.3,0.1

Type RM Length L Ch R = 1 ,37913.34,97.520000,97.520000,97.520000
XS GIS Cut Line= 6
782416.666713731849526.814117432783545.610871081849135.454928772
784012.011270226848981.804018952784128.744461499848934.867352627
784492.028749441848765.833810307785389.827476064848425.754689789
#Sta/Elev= 30
8108.265 169.9538363.985165.01848412.594158.29648571.347153.9039 8760.24161.2403
8889.235 151.8819090.563153.3979 9185.93146.9747 9304.59146.95559365.665140.2594
9565.709140.48189597.295134.93959681.525131.44419869.245129.83819883.293127.4445
9905.077113.00449960.79893.901539983.27780.797769994.51779.9621110017.1285.08936
10050.99110.179610073.53118.416410313.41119.700910356.36138.3185 10474.3136.3246
10495.74143.292510602.53151.823111169.05190.020811179.73199.176711281.07197.4766
#Mann= 3 , 0 , 0
8108.265    0.06       08108.265    0.06       011281.07    0.06       0
#XS Ineff= 2 , 0
       0                               0
Bank Sta=8108.265,11281.07
Exp/Cntr=0.3,0.1

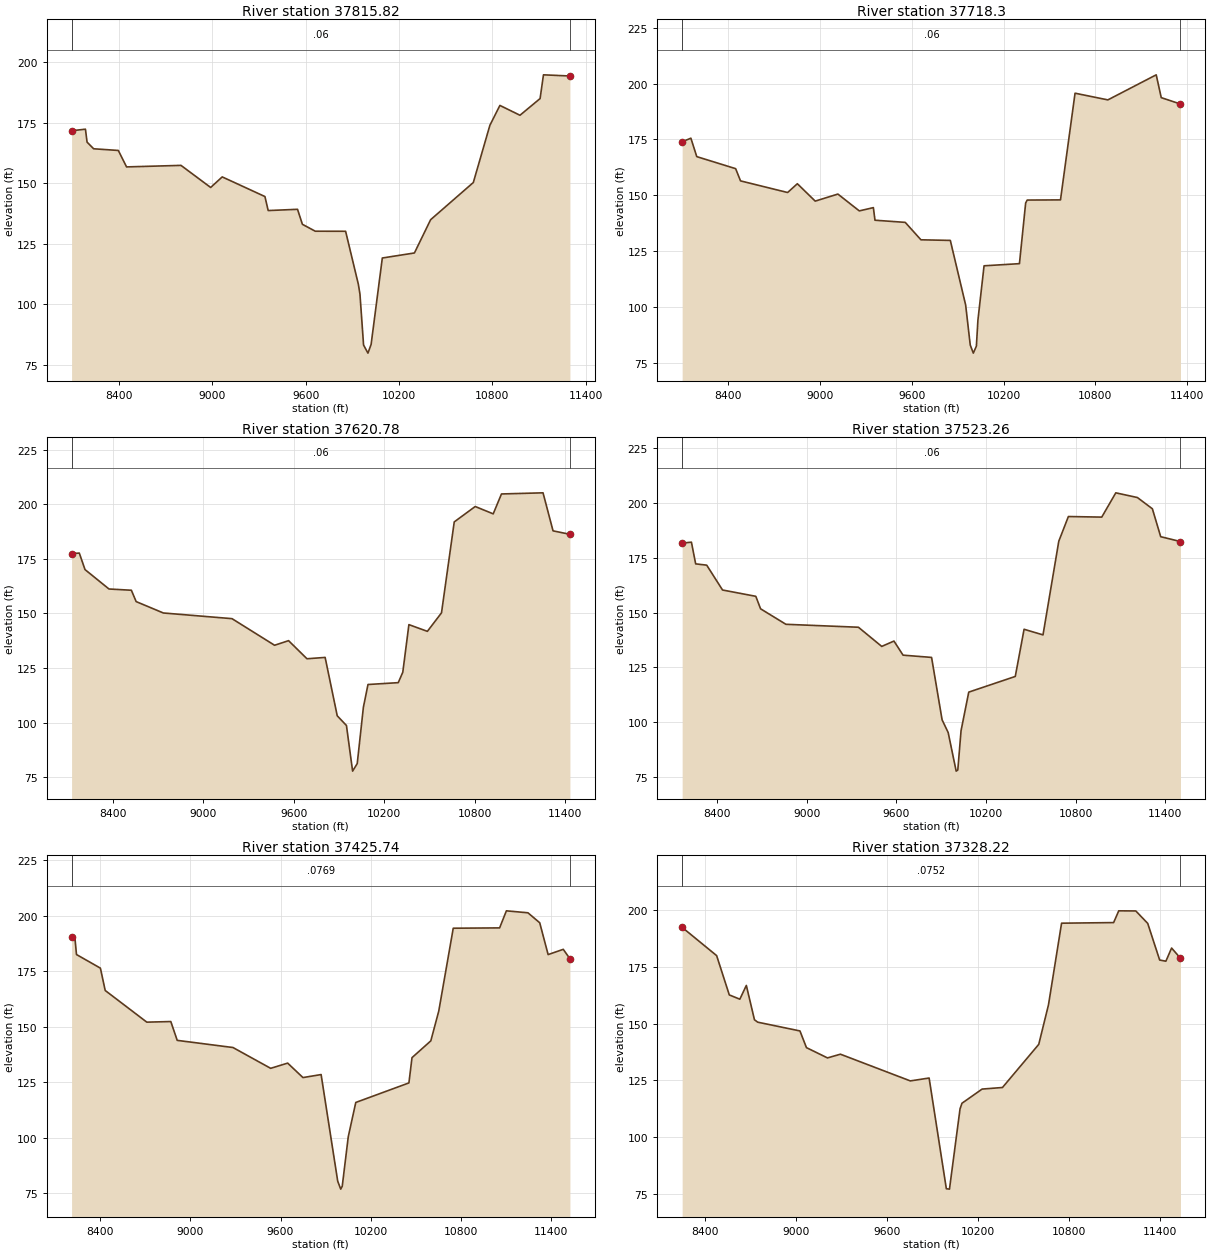
Type RM Length L Ch R = 1 ,37815.82,97.520100,97.520100,97.520100
XS GIS Cut Line= 6
782420.727975602849560.464572932783712.556183142849117.479680394
783944.584549325849053.492592964784468.204016019848933.383793193
784778.689345528848839.664351732785462.363607054 848574.01146483
#Sta/Elev= 30
8096.198  171.648185.187172.29068195.747166.94538237.986164.20568396.465163.5131
8449.441156.72798799.079157.35738989.791148.24639063.957152.6064 9338.34144.5085
9359.366 138.7289547.803139.23899579.053133.06039661.731130.20919856.729130.1745
9938.683108.29969948.928104.2452 9972.0783.2631810000.1479.9220510020.6383.53857
10092.56119.158110298.85121.232710402.87134.951310677.19150.289810783.71173.9017
10847.99182.093710976.93178.033311106.22184.920311127.83194.709411297.83194.2242
#Mann= 3 , 0 , 0
8096.198    0.06       08096.198    0.06       011297.83    0.06       0
#XS Ineff= 2 , 0
       0                               0
Bank Sta=8096.198,11297.83
Exp/Cntr=0.3,0.1

Type RM Length L Ch R = 1 , 37718.3,97.520000,97.520000,97.520000
XS GIS Cut Line= 6
782424.693641759849593.322949658783790.006286986849133.264919817
784072.117826064849083.301680508784487.512989117849080.966754981
784714.946669804849035.010019609785529.904889941848712.059257648
#Sta/Elev= 30
 8101.83173.94658158.828 175.5478197.198167.30128451.054161.91338482.859156.4485
8790.308151.24318853.919155.17298970.537147.39719118.585150.54479258.367143.0169
9350.244144.48359360.753138.84759558.277137.88549660.772130.08619852.635129.8137
9952.707100.91999982.75482.9948210002.7979.3881710022.8382.5285210032.8594.16515
10072.88 118.454 10303.9119.415610344.53146.581910354.73147.865710571.89147.9427
10666.94195.671710881.24192.677211196.88203.8942 11229.7193.688111355.39190.8265
#Mann= 3 , 0 , 0
 8101.83    0.06       0 8101.83    0.06       011355.39    0.06       0
#XS Ineff= 2 , 0
       0                               0
Bank Sta=8101.83,11355.39
Exp/Cntr=0.3,0.1

Type RM Length L Ch R = 1 ,37620.78,97.520000,97.520000,97.520000
XS GIS Cut Line= 6
782430.476349455849641.236813431783837.539709883849177.110264344
784085.865627154849156.977746788784409.338939396849208.431455734
784702.755234889849170.222881715 785576.22745345 848806.73805818
#Sta/Elev= 30
8126.817177.41988177.959177.68718215.952170.11378374.859161.21878523.303160.6445
8555.113155.43698735.366 150.2239190.541147.62119472.936135.42099565.662137.5339
9687.746129.23579808.213129.84939888.476103.07819949.45598.648939990.33677.72167
10021.0581.1991810061.94107.042210092.34 117.43110293.04 118.28210323.17 123.074
10363.64144.881910486.24141.801710579.82150.283510664.33191.972210803.37199.0367
10922.76195.6611 10977.5204.786811253.08205.306911319.44187.8796 11431.4186.2839
#Mann= 3 , 0 , 0
8126.817    0.06       08126.817    0.06       0 11431.4    0.06       0
#XS Ineff= 2 , 0
       0                               0
Bank Sta=8126.817,11431.4
Exp/Cntr=0.3,0.1

Type RM Length L Ch R = 1 ,37523.26,97.520100,97.520100,97.520100
XS GIS Cut Line= 6
782439.410053697849715.258934287 783803.16721127849262.106055398
784083.113310144849243.208079881784345.002847754849307.341135629
784669.603484591849268.961466137785603.927838428848863.354942597
#Sta/Elev= 30
8163.882181.68468226.038182.11488254.416172.2151 8328.46171.61968434.453160.2764
8657.468157.39048689.328151.69678859.244144.61219345.052143.26899501.246134.5118
9583.147 136.9599644.164130.52229835.199129.49259905.681101.00169946.52695.17115
10000.0377.5648110010.9578.0506610032.7396.0352510084.37113.641810396.13120.8039
10455.06142.341210581.94139.781710687.74182.579210751.95193.825610975.59193.5629
11069.67 204.65211214.35202.504311314.75197.366311370.53184.617911503.19 182.402
#Mann= 3 , 0 , 0
8163.882    0.06       08163.882    0.06       011503.19    0.06       0
#XS Ineff= 2 , 0
       0                               0
Bank Sta=8163.882,11503.19
Exp/Cntr=0.3,0.1

Type RM Length L Ch R = 1 ,37425.74,97.520000,97.520000,97.520000
XS GIS Cut Line= 6
782474.168696324849881.529086143783770.003341771849431.043618029
784513.101085212849341.521139023784753.255606284849282.266148788
785139.603776182849122.771006134785614.576482446848885.119732076
#Sta/Elev= 30
8208.603190.55698230.672190.16298241.266182.55618400.597176.41948432.567166.3391
8709.641152.04788869.435152.32138912.118143.83029283.595140.60129534.465131.2155
9647.728133.56849749.527 127.0429870.474128.40139981.042 80.304610001.1576.71188
 10011.2 78.006410051.32100.359810101.37115.816410455.26124.632410475.82136.0352
10601.11 143.60810654.16157.090110750.51194.432211059.26194.5777 11104.5202.2789
   11248201.3889 11326.4 196.89711382.41182.540711483.22184.901611527.55180.6612
#Mann= 3 , 0 , 0
8208.603  0.0769       08208.603  0.0769       011527.55  0.0769       0
#XS Ineff= 2 , 0
       0                               0
Bank Sta=8208.603,11527.55
Exp/Cntr=0.3,0.1

Type RM Length L Ch R = 1 ,37328.22,97.520000,97.520000,97.520000
XS GIS Cut Line= 6
782549.177662647850034.761688784783731.755461597849593.580641372
784592.277481448849376.309685822784821.350567359 849302.71388325
785079.748463137849189.898533334785627.173430531848910.866664988
#Sta/Elev= 30
8249.953192.25858477.517179.84228560.915162.5833 8630.46160.6992 8673.33166.7479
8726.917151.66478748.352150.60299027.005146.75249069.858139.41719208.741 134.896
9293.824136.53389755.097124.79459879.061126.05859992.69577.4101610013.3677.24197
10082.98112.483410095.67114.971610228.61121.2048 10362.9121.897610602.29140.8505
10666.42158.202610752.87194.098111096.25194.360111129.96199.529311242.44199.4742
11321.17194.004911399.91177.908411440.91177.392611478.64183.175611537.32178.6793
#Mann= 3 , 0 , 0
8249.953  0.0752       08249.953  0.0752       011537.32  0.0752       0
#XS Ineff= 2 , 0
       0                               0
Bank Sta=8249.953,11537.32
Exp/Cntr=0.3,0.1

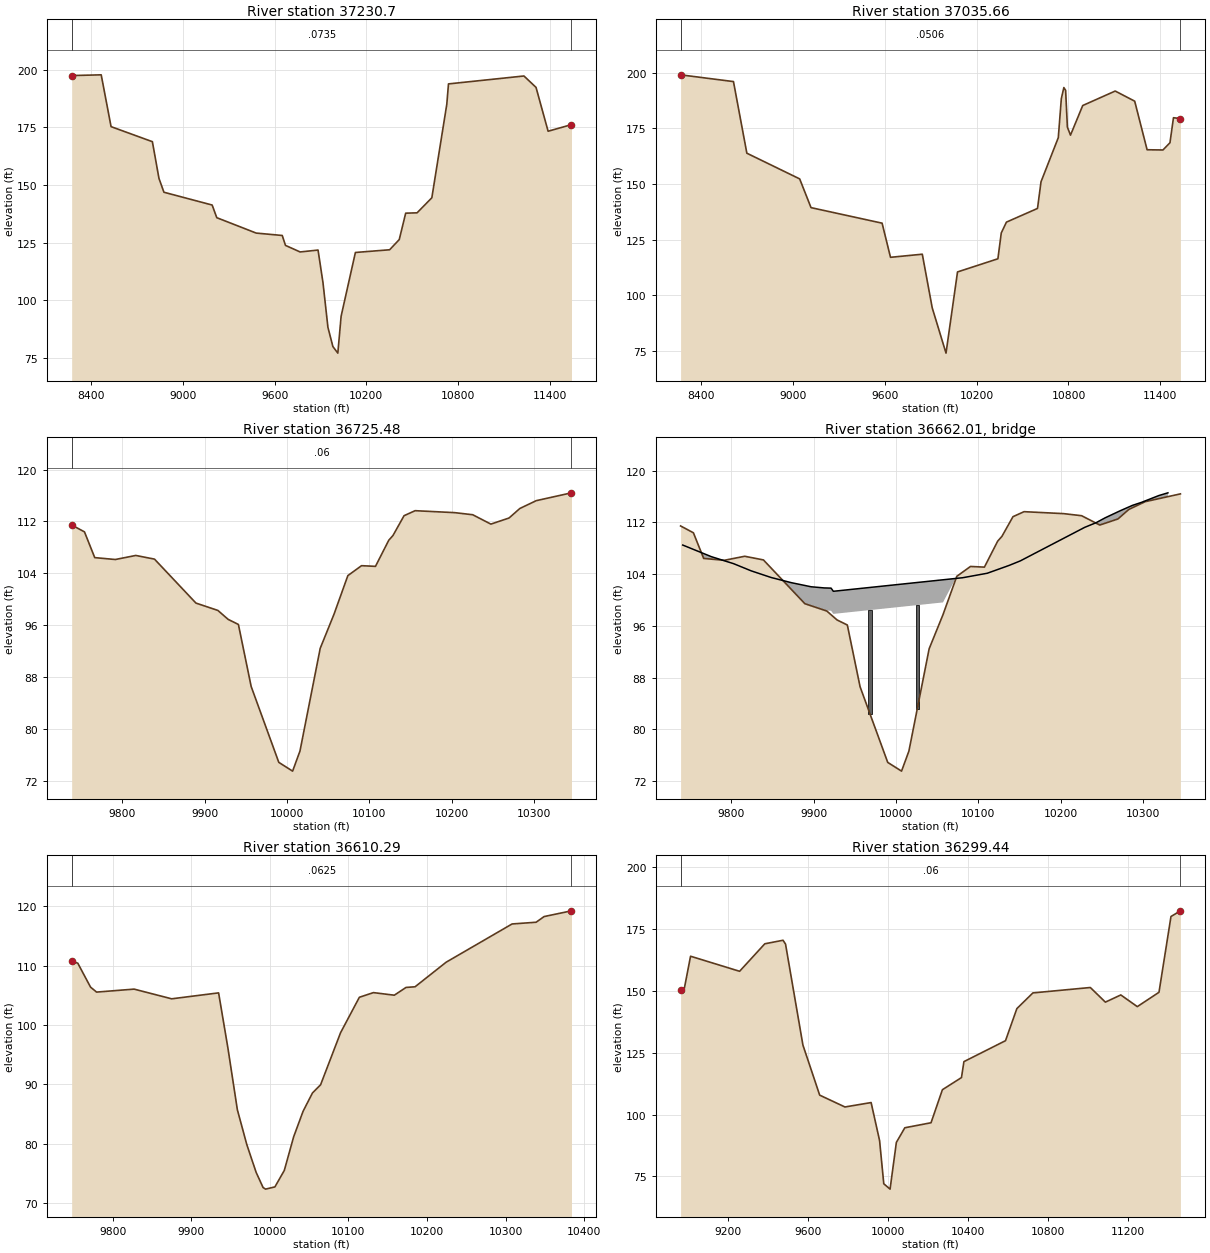
Type RM Length L Ch R = 1 , 37230.7,195.040100,195.040100,195.040100
XS GIS Cut Line= 6
 782624.91325361850189.478681761783682.014984982849763.541356041
784351.723475626849509.743035903784785.494520543849365.534310308
785097.881414971849222.801423713785640.401555408848937.903661687
#Sta/Elev= 30
8272.183197.50148465.448197.82618529.985175.35568800.211168.83878843.448152.8845
8875.875146.91019191.237141.36749221.435135.88289479.172129.20779649.645128.1691
9670.915123.86419766.629121.02099883.891121.84149916.238107.68969948.58588.31304
9980.93280.0048410013.2677.1521910034.7993.1473310128.17120.795310352.18121.9689
10415.01126.393210457.18137.837510531.66137.987810628.23144.514210726.09185.0601
10737.08193.890411230.66197.322111309.72192.387711388.79173.367811541.72 176.235
#Mann= 3 , 0 , 0
8272.183  0.0735       08272.183  0.0735       011541.72  0.0735       0
#XS Ineff= 2 , 0
       0                               0
Bank Sta=8272.183,11541.72
Exp/Cntr=0.3,0.1

Type RM Length L Ch R = 1 ,37035.66,310.182400,310.182400,310.182400
XS GIS Cut Line= 6
782747.583211445850440.075881354783109.655192026850285.755633194
783910.379306098 849912.36099374784657.020684579849578.310592373
784961.519033089849417.789430836785674.523563511849007.645717269
#Sta/Elev= 30
8268.763199.10028613.937196.05818701.211163.8415 9045.95152.28079120.067139.3505
 9583.85132.36359638.683116.99969846.216118.40019910.93994.28399   1000173.89626
10076.01110.421310339.57116.341710361.65127.967310395.24 132.831 10598.1138.9902
 10620.9150.975810733.64170.816610753.57188.420610769.96193.369610781.52192.1126
10793.08 175.55410813.38171.965810893.12185.291511105.19191.801811232.35187.2451
11313.26165.390311416.59165.288511462.46 168.54211485.39179.806311530.71179.3901
#Mann= 3 , 0 , 0
8268.763  0.0506       08268.763  0.0506       011530.71  0.0506       0
#XS Ineff= 2 , 0
       0                               0
Bank Sta=8268.763,11530.71
Exp/Cntr=0.3,0.1

Type RM Length L Ch R = 1 ,36725.48,115.191900,115.191900,115.191900
XS GIS Cut Line= 4
 784275.02212128850227.494253382784501.517847776849922.650948524
 784539.97938624849879.915905803784693.825540066849808.690834582
#Sta/Elev= 30
9738.527111.44739754.093 110.3899766.551106.42099791.467106.13119816.383106.7559
9839.095106.19129889.39799.419139916.04898.284759928.50696.907399940.96496.12199
9956.46786.558669990.00274.8716710006.7773.5226110015.7176.62216 10040.392.45284
10057.0797.7159210073.84103.653410090.46105.179710107.37105.076510123.51 109.101
 10128.6109.826410142.05  112.88 10155.5113.654210203.37113.354110225.41113.0295
10247.45111.586110269.49112.525610282.71113.999210302.55115.199310345.33116.4064
#Mann= 3 , 0 , 0
9738.527    0.06       09738.527    0.06       010345.33    0.06       0
#XS Ineff= 2 , 0
       0                               0
Bank Sta=9738.527,10345.33
Exp/Cntr=0.3,0.1

Type RM Length L Ch R = 3 ,36662.01,,,
BEGIN DESCRIPTION:
END DESCRIPTION:
Bridge Culvert--1,0,-1,-1, 0
Deck Dist Width WeirC Skew NumUp NumDn MinLoCord MaxHiCord MaxSubmerge Is_Ogee
27.595950,60.000000,2.6,0, 24, 26, , , 0.95, 0, 0,0,,
 9741.16 9775.79 9802.92 9824.27 9848.51 9872.75 9896.99 9913.09 9913.09 9921.23
 9923.9410081.0910081.0910110.8210137.5410150.9110229.1410242.7910253.8710272.61
10287.0910298.1710319.1210330.17
  108.49  106.70  105.61  104.50  103.47  102.68  102.04  101.86  101.86  101.83
  101.34  103.44  103.44  104.13  105.35  106.04  111.23  111.94  112.70  113.82
  114.63  115.10  116.15  116.57
 -891.51 -893.30 -894.39 -895.50 -896.53 -897.32 -897.96 -898.14   98.36   98.33
   97.84   99.94 -896.56 -895.87 -894.65 -893.96 -888.77 -888.06 -887.30 -886.18
 -885.37 -884.90 -883.85 -883.43
 9741.16 9775.79 9802.92 9824.27 9848.51 9872.75 9896.99 9909.11 9921.23 9923.94
 9927.60 9927.6010082.8010095.6010095.6010110.8210137.5410150.9110229.1410242.79
10253.8710272.6110287.0910298.1710319.1210330.17
  108.49  106.70  105.61  104.50  103.47  102.68  102.04  101.88  101.83  101.34
  101.39  101.39  103.46  103.73  103.73  104.13  105.35  106.04  111.23  111.94
  112.70  113.82  114.63  115.10  116.15  116.57
 -891.51 -893.30 -894.39 -895.50 -896.53 -897.32 -897.96 -898.12 -898.17 -898.66
 -898.61   97.89   99.96  100.23 -896.27 -895.87 -894.65 -893.96 -888.77 -888.06
 -887.30 -886.18 -885.37 -884.90 -883.85 -883.43
Pier Skew, UpSta & Num, DnSta & Num=  ,9968.43, 2 ,9982.93, 2 , 0 , 0 , 0 ,,
    4.00    4.00
 -898.07  101.93
    4.00    4.00
 -897.87  102.13
Pier Skew, UpSta & Num, DnSta & Num=  ,10025.76, 2 ,10040.27, 2 , 0 , 0 , 0 ,,
    4.00    4.00
 -897.30  102.70
    4.00    4.00
 -897.11  102.89
BR Coef=-1 , 0 , 0 ,, 0 ,,,0.8,0,1,0,
WSPro=,,,, 1 ,,,, 0 ,,,, 0 ,,,,-1 ,-1 ,-1 , 0 , 0 , 0 , 0 , 0
BC Design=,, 0 ,, 0 ,,,,,,

Type RM Length L Ch R = 1 ,36610.29,310.851500,310.851500,310.851500
XS GIS Cut Line= 5
784381.859728128850301.568327457784582.714428991849993.876019776
784626.873973131849953.989979863784688.127534419849909.830435708
 784819.18166545849884.189410076
#Sta/Elev= 30
9747.832110.82149755.676110.40969771.871106.3864 9779.56105.54889827.328106.0492
9875.096104.41519934.807105.41769946.74996.053719958.691  85.7179970.63379.88039
9982.57575.167399991.401  72.6229994.51772.3472110006.4672.72338 10018.475.49625
10030.34 81.174810042.2885.4564510054.2388.5498710064.58 89.929910090.0598.71666
10113.94104.677310131.83105.460810158.36105.023410173.28106.3313 10184.8106.4433
10224.36110.585910308.25117.028210338.82 117.31910349.01118.275810383.84119.2422
#Mann= 3 , 0 , 0
9747.832  0.0625       09747.832  0.0625       010383.84  0.0625       0
#XS Ineff= 2 , 0
       0                               0
Bank Sta=9747.832,10383.84
Exp/Cntr=0.3,0.1

Type RM Length L Ch R = 1 ,36299.44,99.796500,99.796500,99.796500
XS GIS Cut Line= 6
784187.682700195851057.038737092784640.668747336 850564.32777524
784873.949197441 850026.06808421785049.542955786849776.395634979
785342.299261332849503.713758543 785774.99694404849199.666409343
#Sta/Elev= 30
8965.699150.40218984.489151.04919015.516164.04739260.368157.94949386.463169.0824
9477.325170.50349489.808168.95759576.667128.09029660.405107.83699786.486103.0491
9917.211104.83199959.51889.436899980.44471.9796610011.8469.8078610043.2788.71111
10085.5794.63773 10216.496.6607210273.21110.033510368.49114.947110380.66121.3955
10588.43129.873810645.06142.848810725.13149.200411011.98 151.38711087.15145.4672
11164.13148.379211246.51143.653911354.84149.451511414.69180.111111461.87182.4145
#Mann= 3 , 0 , 0
8965.699    0.06       08965.699    0.06       011461.87    0.06       0
#XS Ineff= 2 , 0
       0                10138.18       0
Bank Sta=8965.699,11461.87
Exp/Cntr=0.3,0.1