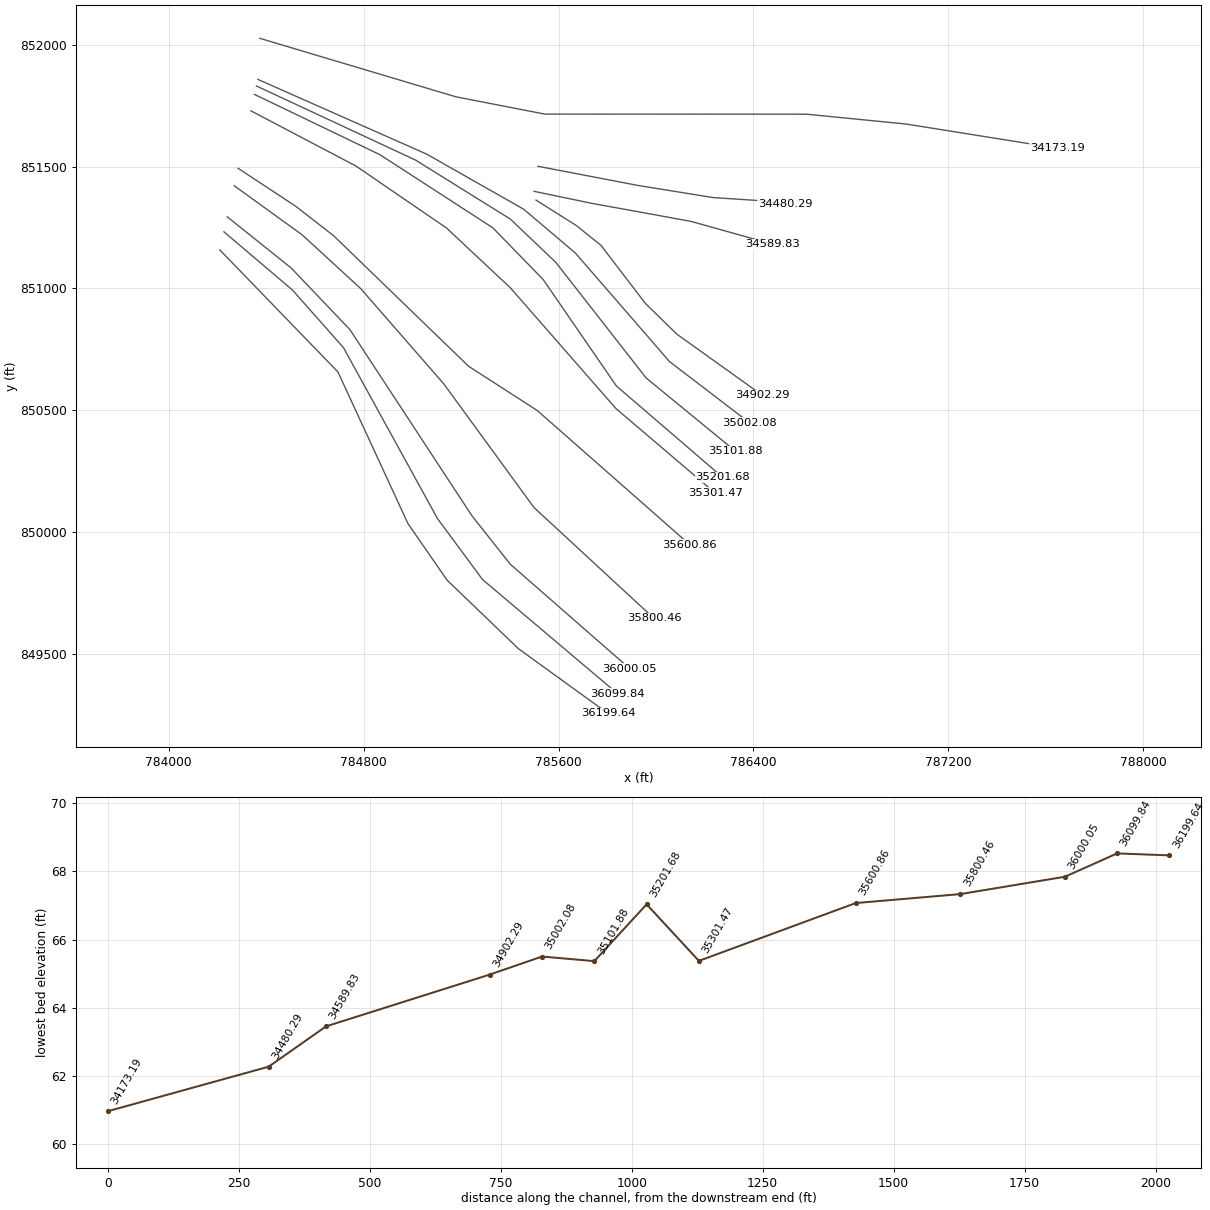
HEC-RAS study 15937_ras.prj: 15937

--- 15937_ras.g01 (geometry) --- (continued)

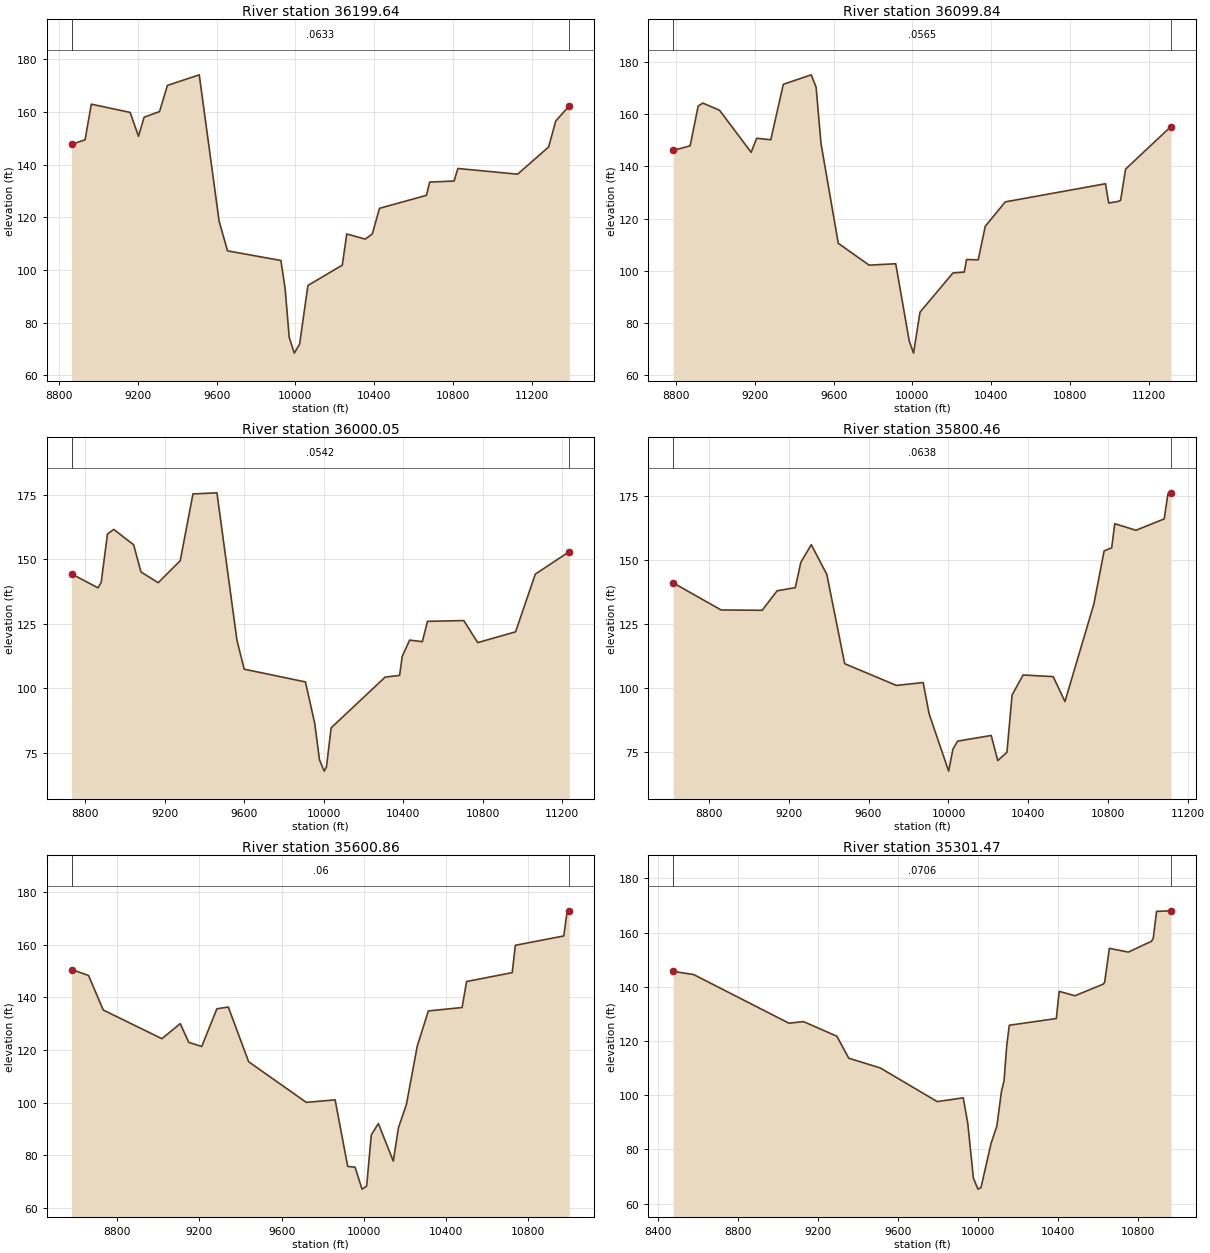
Type RM Length L Ch R = 1 ,36199.64,99.796500,99.796500,99.796500
XS GIS Cut Line= 6
784210.100960513851157.920908508784694.560623497850657.316430092
784981.582969099850035.576152846785142.497552961849802.869097143
785435.493839979849521.357618108785802.414075822849256.058464512
#Sta/Elev= 30
8862.244147.69518930.944149.41788962.806162.93419160.077159.80369202.553150.7473
9231.004157.9853 9309.54160.12759349.486170.0544 9511.25174.06979612.221118.5364
9654.941107.28189926.257 103.617 9947.5693.060759968.65874.407249994.34968.46566
10021.3771.87527 10063.694.1333210238.33101.854210261.06 113.68610354.55111.7265
10390.62113.648110427.47123.416610665.92128.333410682.44133.364710806.63133.7719
10825.59138.533511129.44136.365311287.01146.695411323.31156.564811392.07162.2995
#Mann= 3 , 0 , 0
8862.244  0.0633       08862.244  0.0633       011392.07  0.0633       0
#XS Ineff= 2 , 0
       0                10111.44       0
Bank Sta=8862.244,11392.07
Exp/Cntr=0.3,0.1

Type RM Length L Ch R = 1 ,36099.84,99.796400,99.796400,99.796400
XS GIS Cut Line= 6
784226.667243677851232.469182733784507.793751836850993.779927045
784717.348001301850757.019072711785103.027105927850055.786624193
785288.008104414849805.366262004785841.910348862849337.295116976
#Sta/Elev= 30
8785.944146.11278871.702147.89168912.411163.1023 8936.22164.24319020.802 161.506
9181.377145.40249209.425150.77319281.009150.20249344.557171.42969486.341175.0585
9511.111170.28589535.882148.77499623.588110.56349780.283 102.1989915.263 102.741
9983.62673.2449710005.5868.5236610038.4684.2039210205.8399.2158910263.0799.56352
10274.55104.358110333.87104.240710369.66117.074810471.33126.424610979.96133.3635
10996.18125.967911044.19126.603911056.67127.035911081.85138.963511312.35155.2744
#Mann= 3 , 0 , 0
8785.944  0.0565       08785.944  0.0565       011312.35  0.0565       0
#XS Ineff= 2 , 0
       0                   10090       0
Bank Sta=8785.944,11312.35
Exp/Cntr=0.3,0.1

Type RM Length L Ch R = 1 ,36000.05,199.593000,199.593000,199.593000
XS GIS Cut Line= 6
 784240.35201365851294.050647606784502.427942425 851084.29223749
784743.735492378850831.053965405785244.365563452850067.277482122
785401.849216133849868.294201165785891.841935009849439.995311186
#Sta/Elev= 30
 8730.12144.2824 8863.06138.89178879.293140.97398910.918159.72368942.543161.5449
9042.812155.56419079.571145.04269166.467140.87399277.215 149.3979341.421175.2852
9462.094175.71379562.816118.58639599.227107.35989907.738102.41339954.72186.23314
9978.26372.2592510001.7867.8396510013.5269.4307110037.0184.6049110308.82104.2781
10381.78104.955410394.99112.320310432.23118.617610496.17118.032110522.23 125.898
10705.02126.199710774.94 117.65510965.71121.836411064.97144.197311236.06152.9111
#Mann= 3 , 0 , 0
 8730.12  0.0542       0 8730.12  0.0542       011236.06  0.0542       0
#XS Ineff= 2 , 0
       0                10082.13       0
Bank Sta=8730.12,11236.06
Exp/Cntr=0.3,0.1

Type RM Length L Ch R = 1 ,35800.46,199.592900,199.592900,199.592900
XS GIS Cut Line= 6
784268.750632486851421.844432349784547.453959554851220.419881701
784787.402908772851000.154679209785129.155690104  850608.3034973
785498.853903085  850101.2653822785991.875063926849645.745269477
#Sta/Elev= 30
8622.776 141.0878862.334130.49259067.867130.36839142.539138.0067 9233.42139.2295
9261.378149.18259313.516  156.089391.275144.41419480.713109.42569739.481100.9244
9873.237102.04419903.447  89.70110000.9767.3314410022.1775.9065410045.8779.08388
 10213.981.3120610246.5671.4636210292.4974.70116 10318.3 97.142510373.32105.0127
10523.94104.371810582.9294.5985810727.87 132.89310778.82 153.63510816.84  154.86
10832.01164.314910938.17161.729211079.54166.175511098.35176.069511113.49176.4008
#Mann= 3 , 0 , 0
8622.776  0.0638       08622.776  0.0638       011113.49  0.0638       0
#XS Ineff= 2 , 0
       0                10070.78       0
Bank Sta=8622.776,11113.49
Exp/Cntr=0.3,0.1

Type RM Length L Ch R = 1 ,35600.86,299.389400,299.389400,299.389400
XS GIS Cut Line= 6
784284.618302275851493.248946389784520.702134669851337.979338244
784676.698090196851216.638259634785231.345461667850680.333226353
785512.792193413850499.069356769786138.956913978849948.265892923
#Sta/Elev= 30
8577.493150.59888660.197148.3375 8731.59135.20849017.101124.29389106.426130.0073
9147.933122.88929211.079121.32239284.748135.66279340.222136.33569439.374115.5251
9719.904  100.079860.093101.03079921.45375.706359957.21175.408679991.09667.06865
10013.5568.2132310036.0587.6764910070.58 92.010110143.2677.7154910168.2290.40391
10206.9199.2299510259.81121.476610313.79134.843510477.92136.148710499.92146.0353
10722.04149.421310737.15159.824210972.86163.3634 10988.9172.5029 10999.7172.9289
#Mann= 3 , 0 , 0
8577.493    0.06       08577.493    0.06       0 10999.7    0.06       0
#XS Ineff= 2 , 0
       0                10060.47       0
Bank Sta=8577.493,10999.7
Exp/Cntr=0.3,0.1

Type RM Length L Ch R = 1 ,35301.47,99.796500,99.796500,99.796500
XS GIS Cut Line= 6
784337.075304418851729.305455999784768.796067685851502.448402733
785140.528429627851247.979317263785402.288233191 851002.78719604
785835.076986164850507.731014654786242.338909209 850160.90386048
#Sta/Elev= 30
8476.014145.68398578.105144.51139054.962126.57579127.773127.1529 9295.01121.7649
9354.596113.64629511.763110.08269797.19997.65587 9927.4299.038689950.19689.62997
9978.23469.47118   1000165.3744310016.2865.9391110066.8782.2979910095.7888.62735
10118.75 101.38410131.76 105.33210144.77117.999110157.96125.807510393.42128.2917
10407.57138.312910486.52136.695410628.16140.975210635.44141.713410658.84 154.185
 10754.1152.7972 10869.6156.7739 10878.5157.885810895.18 167.81210967.27168.0109
#Mann= 3 , 0 , 0
8476.014  0.0706       08476.014  0.0706       010967.27  0.0706       0
#XS Ineff= 2 , 0
       0                               0
Bank Sta=8476.014,10967.27
Exp/Cntr=0.3,0.1

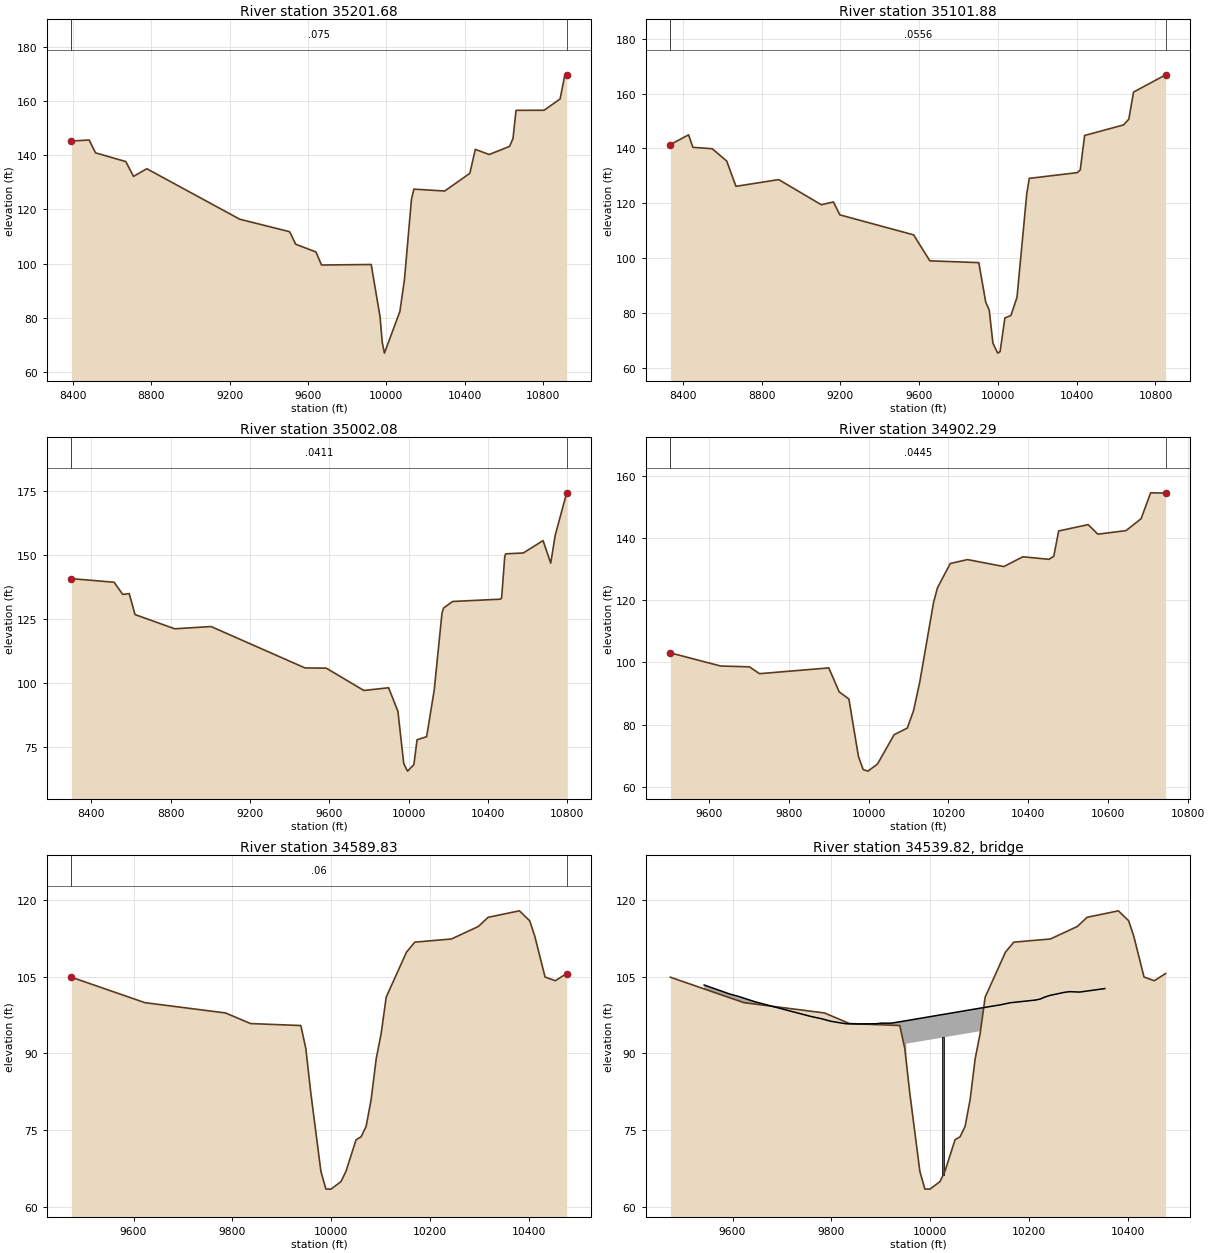
Type RM Length L Ch R = 1 ,35201.68,99.796500,99.796500,99.796500
XS GIS Cut Line= 6
784352.035699273851796.627232833784867.346541971851548.893759713
785330.280097872851249.043030247785536.763561308851036.838548198
785837.320418596850600.038157821786273.485920489850224.967599466
#Sta/Elev= 30
8391.766145.1924 8482.15145.57778515.116140.83428669.489 137.6238708.851132.1601
8776.805134.99069251.295116.38769506.528111.78079537.453107.16189641.007104.3059
9669.35499.500599923.00799.693029968.32680.405089979.41471.046559990.50267.03237
10069.6682.3841210092.9794.1696410128.81123.7731 10141.2 127.46710298.39126.7734
10426.95133.291910454.87 142.12210525.86140.231610629.98143.224210647.33146.0949
10662.96156.500410806.19 156.53710887.87 160.68410911.07169.105810921.61169.5914
#Mann= 3 , 0 , 0
8391.766   0.075       08391.766   0.075       010921.61   0.075       0
#XS Ineff= 2 , 0
       0                               0
Bank Sta=8391.766,10921.61
Exp/Cntr=0.3,0.1

Type RM Length L Ch R = 1 ,35101.88,99.796400,99.796400,99.796400
XS GIS Cut Line= 6
784359.760871406851831.390507428785013.325585514851526.966208115
785401.907919705851285.047007605785588.259721875851107.856820896
785959.436256826 850632.82692486786325.804926544850332.578282416
#Sta/Elev= 30
8336.583141.40638429.022 144.9568450.725140.38928548.834139.90078622.492135.4091
8669.618126.17898886.576128.63499102.976 119.4689164.611 120.4789197.133115.7766
9571.756108.48289654.20599.018499902.77398.359299938.09783.946329955.79381.05486
9974.481 69.03179998.73865.3663210010.9565.8960410035.3678.2003110066.12 79.0916
10096.8885.7551710146.49123.5397 10159.1129.080210403.59 131.18110418.15132.2086
10440.34144.727110637.28148.548410664.59150.658810688.83160.538410851.77166.8312
#Mann= 3 , 0 , 0
8336.583  0.0556       08336.583  0.0556       010851.77  0.0556       0
#XS Ineff= 2 , 0
       0                               0
Bank Sta=8336.583,10851.77
Exp/Cntr=0.3,0.1

Type RM Length L Ch R = 1 ,35002.08,99.796500,99.796500,99.796500
XS GIS Cut Line= 6
784365.760269591851858.387799254785059.225742251851551.334194958
785457.351727158851325.134563938785669.005580932851145.622272626
786055.763070732850699.773663297786382.798038751850449.802751869
#Sta/Elev= 30
8299.213140.85288514.405139.44528558.023134.68038590.735134.98728620.003126.7902
8820.379121.2215 9003.34122.10369477.515105.89269584.492105.81359774.12897.07496
9898.97698.138039945.96888.922429975.33868.471159994.46865.50215 10026.468.06162
10042.5977.7666910090.7178.9827410129.0997.2515410168.03127.262710175.95129.3237
10221.94131.913910463.54132.813110469.06133.373910484.93149.6316 10489.3150.5549
10578.34 150.89910677.97155.742210716.71146.928310739.36157.849810797.14174.4441
#Mann= 3 , 0 , 0
8299.213  0.0411       08299.213  0.0411       010797.14  0.0411       0
#XS Ineff= 2 , 0
       0                               0
Bank Sta=8299.213,10797.14
Exp/Cntr=0.3,0.1

Type RM Length L Ch R = 1 ,34902.29,312.459300,312.459300,312.459300
XS GIS Cut Line= 6
785507.715905815851362.723330826785672.598458111851258.708990142
785774.342339516851176.951916903785956.896786869850938.211878836
 786086.17356801850812.190039709786436.982763678850561.250879288
#Sta/Elev= 30
9504.132103.08789629.595 98.85969702.15998.584659727.05896.381129900.53398.24183
9926.42790.545079950.85888.215299974.71169.705129986.63865.465659998.56564.97287
10022.3467.2521410064.0476.7096810097.0378.86428 10112.684.4537110128.1693.68885
10162.76119.388210172.46124.050910204.52131.9005 10247.7133.156410338.66130.9143
10386.15134.062310451.54133.246410463.47134.222610475.85142.386510549.59144.4281
10573.69141.349410644.26 142.48210682.13146.3466 10705.9 154.67610743.51154.6117
#Mann= 3 , 0 , 0
9504.132  0.0445       09504.132  0.0445       010743.51  0.0445       0
#XS Ineff= 2 , 0
       0                               0
Bank Sta=9504.132,10743.51
Exp/Cntr=0.3,0.1

Type RM Length L Ch R = 1 ,34589.83,109.541100,109.541100,109.541100
XS GIS Cut Line= 5
785499.384142578 851398.83142148785738.605640501851349.060505807
 785916.81762886851316.950237617786144.800532907851275.206888989
 786477.14180851851182.087111294
#Sta/Elev= 30
9474.305104.87349623.03999.899999786.113  97.8889836.91895.813069938.54895.42963
9948.71590.929589958.88182.181169979.21366.916519989.37963.470869999.54663.45534
10019.8864.9267410030.0466.9604410050.3873.1036710060.5473.6854710070.7175.70871
10080.8880.9370410091.0488.8811410101.2193.8872210111.37100.983610152.48109.7796
10169.34111.726710243.46112.347310297.87114.786210317.59116.580510380.95117.8476
10401.72115.909110412.11112.891410432.88104.913110453.65104.186710476.64105.5929
#Mann= 3 , 0 , 0
9474.305    0.06       09474.305    0.06       010476.64    0.06       0
#XS Ineff= 2 , 0
       0                               0
Bank Sta=9474.305,10476.64
Exp/Cntr=0.3,0.1

Type RM Length L Ch R = 3 ,34539.82,,,
BEGIN DESCRIPTION:
END DESCRIPTION:
Bridge Culvert--1,0,-1,-1, 0
Deck Dist Width WeirC Skew NumUp NumDn MinLoCord MaxHiCord MaxSubmerge Is_Ogee
25.770550,58.000000,2.6,0, 27, 27, , , 0.95, 0, 0,0,,
 9542.65 9594.84 9612.66 9645.93 9758.32 9778.76 9799.19 9819.63 9829.84 9856.24
 9891.14 9901.17 9921.24 9951.91 9951.9110100.9110100.9110142.0110162.0810212.25
10222.2810232.3110242.3510272.4510282.4810302.5510353.46
  103.35  101.57  101.11  100.06   97.21   96.79   96.26   95.93   95.78   95.74
   95.78   95.90   95.89   96.38   96.38   98.82   98.82   99.47   99.88  100.40
  100.59  101.00  101.31  101.93  102.05  101.97  102.65
 -896.65 -898.43 -898.89 -899.94 -902.79 -903.21 -903.74 -904.07 -904.22 -904.26
 -904.22 -904.10 -904.11 -903.62   91.88   94.32 -901.18 -900.53 -900.12 -899.60
 -899.41 -899.00 -898.69 -898.07 -897.95 -898.03 -897.35
 9542.65 9594.84 9612.66 9645.93 9758.32 9778.76 9799.19 9819.63 9829.84 9856.24
 9891.14 9901.17 9921.24 9944.25 9944.2510093.2510093.2510142.0110162.0810212.25
10222.2810232.3110242.3510272.4510282.4810302.5510353.46
  103.35  101.57  101.11  100.06   97.21   96.79   96.26   95.93   95.78   95.74
   95.78   95.90   95.89   96.25   96.25   98.70   98.70   99.47   99.88  100.40
  100.59  101.00  101.31  101.93  102.05  101.97  102.65
 -896.65 -898.43 -898.89 -899.94 -902.79 -903.21 -903.74 -904.07 -904.22 -904.26
 -904.22 -904.10 -904.11 -903.75   91.75   94.20 -901.30 -900.53 -900.12 -899.60
 -899.41 -899.00 -898.69 -898.07 -897.95 -898.03 -897.35
Pier Skew, UpSta & Num, DnSta & Num=  ,10026.41, 2 ,10018.75, 2 , 0 , 0 , 0 ,,
    4.00    4.00
 -902.40   97.60
    4.00    4.00
 -902.52   97.48
BR Coef=-1 , 0 , 0 ,, 0 ,,,0.8,0,1,0,
WSPro=,,,, 1 ,,,, 0 ,,,, 0 ,,,,-1 ,-1 ,-1 , 0 , 0 , 0 , 0 , 0
BC Design=,, 0 ,, 0 ,,,,,,

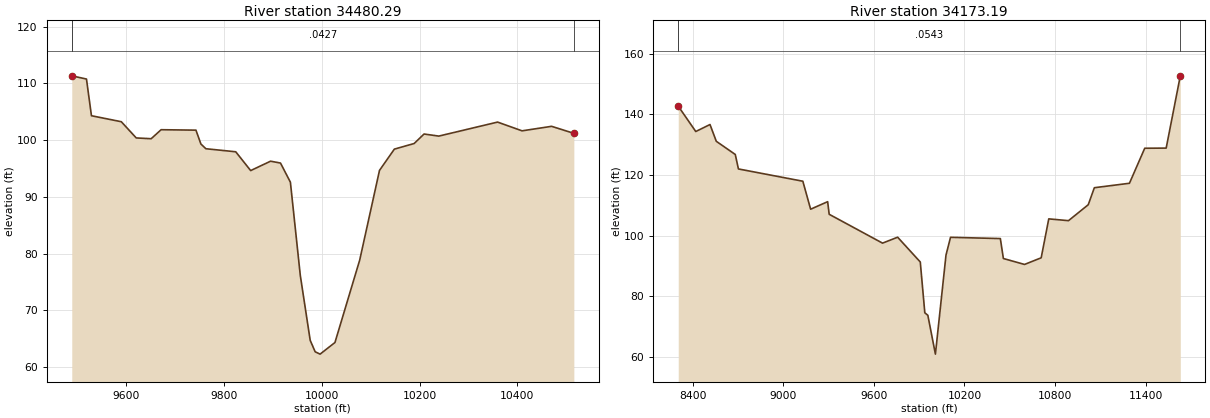
Type RM Length L Ch R = 1 ,34480.29,307.098500,307.098500,307.098500
XS GIS Cut Line= 5
785515.439276665851501.584279627785926.450709343851422.914122596
786234.709283829851373.143206924786432.187433094851360.299099669
786530.123750985851347.454992399
#Sta/Elev= 30
9488.029111.32279518.126110.75479528.308104.28969589.397103.23429619.942 100.376
9650.486100.23789670.849101.8254 9742.12101.74889752.30199.302069762.48398.47314
9823.57297.935279854.11794.622159894.84396.277919915.16295.950019935.42192.57292
 9955.6876.138839975.939 64.70479986.06862.688319996.19862.2741910026.5964.32225
10077.2378.8499810117.7594.6578210148.1498.4040610188.6699.3942110208.92101.0676
10239.09   100.710359.34103.168710409.45101.627410469.91102.422710515.42101.1885
#Mann= 3 , 0 , 0
9488.029  0.0427       09488.029  0.0427       010515.42  0.0427       0
#XS Ineff= 2 , 0
       0                               0
Bank Sta=9488.029,10515.42
Exp/Cntr=0.3,0.1

Type RM Length L Ch R = 1 ,34173.19,98.286600,98.286600,98.286600
XS GIS Cut Line= 6
784374.009251744852026.798869745785178.468335479851786.810731679
785544.032985091851715.781330436786617.056283921851715.519338474
787026.431235403851675.061071992787647.158639044851576.004915833
#Sta/Elev= 30
8303.801142.68668419.993134.32398514.211136.62778556.085 131.0968681.709126.7597
8702.646121.98829129.418117.94089180.981108.72539293.719111.20399303.943107.0518
9657.44397.542889757.49399.497099907.55691.32135 9937.59 74.58519957.61273.77315
10007.7660.9684710077.9493.6172710107.9699.4598610438.0999.0459510458.0992.47568
10598.2690.5201110708.5792.70751 10758.8105.535810889.52104.944911020.48110.2022
11060.87115.8052 11293.4117.268711394.67128.812211536.77128.859611630.38152.6742
#Mann= 3 , 0 , 0
8303.801  0.0543       08303.801  0.0543       011630.38  0.0543       0
#XS Ineff= 2 , 0
       0                               0
Bank Sta=8303.801,11630.38
Exp/Cntr=0.3,0.1