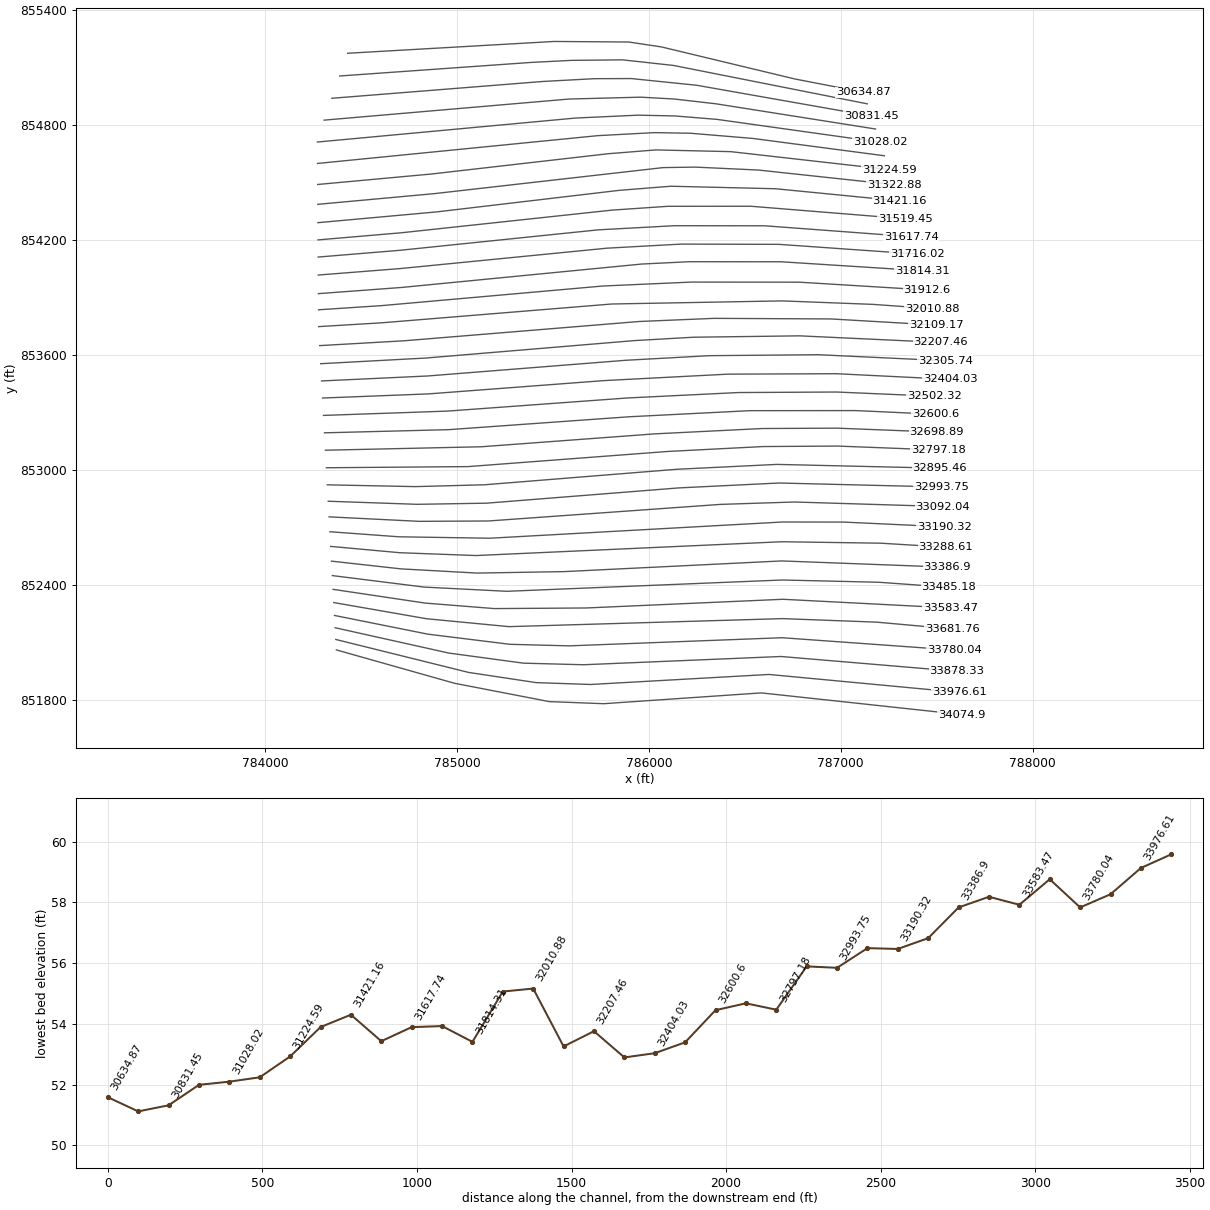
HEC-RAS study 15937_ras.prj: 15937

--- 15937_ras.g01 (geometry) --- (continued)

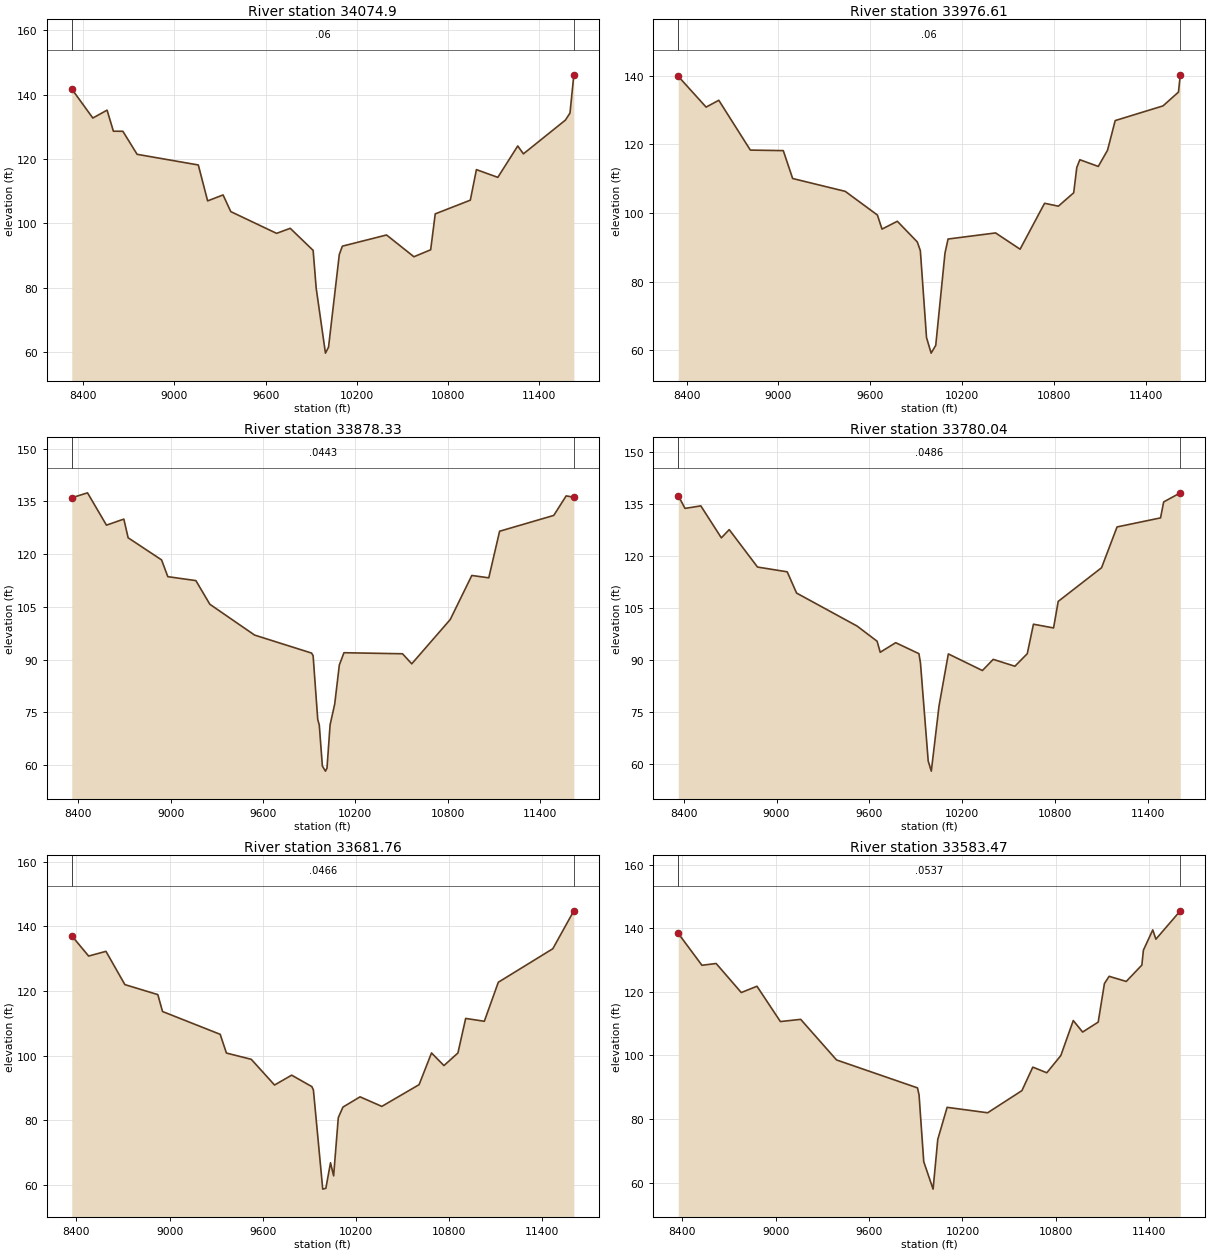
Type RM Length L Ch R = 1 , 34074.9,98.286500,98.286500,98.286500
XS GIS Cut Line= 6
784372.002909839852063.369010843784986.867320657851889.627676696
785481.319826305851793.969988495785764.338947505851783.063774273
 786585.76899913851839.379102767787630.069688588851726.550432071
#Sta/Elev= 30
8324.738141.76858463.241132.73168556.967135.17728598.623128.62838661.002128.6056
8754.484  121.449157.061118.12459218.366  106.959319.933108.80279370.606103.6166
9671.81796.852419761.83598.413649912.32591.554059932.52279.74714 9993.3459.58617
10013.6461.44461 10084.590.2885410104.6392.8673410395.2596.3441410575.2889.57138
10685.3791.7379310715.43 102.91210946.11107.1732 10986.3116.678411127.13114.2721
11258.18124.045211295.38121.587511571.43132.074611601.77134.274111627.13146.1707
#Mann= 3 , 0 , 0
8324.738    0.06       08324.738    0.06       011627.13    0.06       0
#XS Ineff= 2 , 0
       0                               0
Bank Sta=8324.738,11627.13
Exp/Cntr=0.3,0.1

Type RM Length L Ch R = 1 ,33976.61,98.286600,98.286600,98.286600
XS GIS Cut Line= 6
784369.017662582852117.781926771785060.424531132851946.178082362
785413.058617383851892.891173214785697.264102221851883.242262751
786625.999978006 851935.45408079787616.957472682851842.062810361
#Sta/Elev= 30
8345.303139.78428527.484130.80968610.302 132.8028816.478118.28929031.775118.1317
9093.005110.00879436.589 106.2669646.83999.363559676.839 95.27289776.90397.55137
 9907.3491.53031 9927.4488.969639967.64263.688579997.79359.1358910027.9661.39739
10088.2988.27044 10108.492.37891   1041994.1522410579.0289.4170910739.08102.7971
10829.21 101.94810929.42105.854310949.48113.208910969.54115.477611089.98113.5296
11150.29118.229511200.54126.889511512.86131.161111613.92135.1828   11626140.2153
#Mann= 3 , 0 , 0
8345.303    0.06       08345.303    0.06       0   11626    0.06       0
#XS Ineff= 2 , 0
       0                               0
Bank Sta=8345.303,11626
Exp/Cntr=0.3,0.1

Type RM Length L Ch R = 1 ,33878.33,98.286500,98.286500,98.286500
XS GIS Cut Line= 6
784365.666508541852178.864325444784957.590124935 852046.94139643
785346.358970553 851994.30957374785659.090656668851986.038888171
786688.731601834852029.040210158787604.488552958851951.908055574
#Sta/Elev= 30
8357.149136.01698459.432137.42958582.646 128.2388695.515  129.968723.379124.6481
8940.632118.34888981.318113.58049163.618112.46439254.276105.7384 9545.0196.96983
9915.37391.846139925.39191.093379955.44772.958659965.46671.355569985.50359.70965
10005.5458.2712110015.56 59.1217 10035.671.4145210065.6777.3504910095.7388.46911
10125.7991.9503410506.2691.6534210566.2688.7944710816.33101.390610956.52113.9226
 11066.8113.2542   11137 126.50211488.88131.001411569.54136.559811619.48136.1827
#Mann= 3 , 0 , 0
8357.149  0.0443       08357.149  0.0443       011619.48  0.0443       0
#XS Ineff= 2 , 0
       0                               0
Bank Sta=8357.149,11619.48
Exp/Cntr=0.3,0.1

Type RM Length L Ch R = 1 ,33780.04,98.286500,98.286500,98.286500
XS GIS Cut Line= 6
784362.152446777 852242.91608763784848.106589019 852145.50430648
785276.404211372852092.526853397785584.194473177852084.453801244
786694.409465551852126.842644349787591.946745664852062.395405531
#Sta/Elev= 30
8364.475137.45138408.286 133.7538510.535134.48338643.344125.24328694.209127.6209
8877.221 116.806 9069.32115.42849129.751109.28919520.634 99.76879650.65795.36471
9670.66592.180859770.74794.950359920.94691.776189930.95989.106749981.02660.75536
10001.0557.8375110051.1376.7119910111.2291.7063710331.5486.9055810401.5790.13269
10541.6488.1429110621.6491.7733510661.64  100.2910791.6699.2144110821.67106.8805
11102.04116.609811202.27128.397211483.52131.010211503.64135.614511611.34 138.253
#Mann= 3 , 0 , 0
8364.475  0.0486       08364.475  0.0486       011611.34  0.0486       0
#XS Ineff= 2 , 0
       0                               0
Bank Sta=8364.475,11611.34
Exp/Cntr=0.3,0.1

Type RM Length L Ch R = 1 ,33681.76,98.286600,98.286600,98.286600
XS GIS Cut Line= 6
 784358.46686741852310.094147929784841.488560081852225.808410823
785271.092489928852184.601858929786697.027754009852226.391797259
787187.383600056852207.979630485787579.687142044852172.654789448
#Sta/Elev= 30
8369.755137.04678478.371130.7877 8590.06132.2394 8711.88121.96418924.119118.8686
8954.341113.64839325.777 106.5979365.796100.81469525.82398.879829675.88190.93447
9785.97893.98125 9916.1590.440989926.16389.404289986.243 58.765610006.27 59.0242
10036.3166.9147710056.3462.8683210086.3880.8457410116.4284.1159910226.5887.28277
10366.7484.3311410606.8591.0465910686.85100.844910766.8596.9418310856.86100.8252
10906.89111.513111026.97110.634711117.12122.689411468.16133.047211603.57144.7591
#Mann= 3 , 0 , 0
8369.755  0.0466       08369.755  0.0466       011603.57  0.0466       0
#XS Ineff= 2 , 0
       0                               0
Bank Sta=8369.755,11603.57
Exp/Cntr=0.3,0.1

Type RM Length L Ch R = 1 ,33583.47,98.286500,98.286500,98.286500
XS GIS Cut Line= 6
784354.689118652852378.952204854784835.405570596 852307.25432314
785195.210627109852278.667105511785673.016951919852281.861957729
 786698.98842144852327.178487718787571.213826537 852282.07108143
#Sta/Elev= 30
8374.032138.37428526.368128.32838617.581128.89178779.112119.75478879.835121.7337
9030.543110.62679160.824111.32119390.978 98.55999911.40489.767299921.419 87.5282
9951.46566.5592210011.5657.9244810041.6173.57105 10101.783.6523310362.0681.94013
 10582.288.9052610652.2196.2945710742.2194.5246210832.2199.9347610912.23110.9536
10972.25107.333411072.33110.452811112.37122.572811142.41124.857211252.58123.2463
11352.85128.385911362.87133.086211423.03139.459911443.09136.539311599.95145.4553
#Mann= 3 , 0 , 0
8374.032  0.0537       08374.032  0.0537       011599.95  0.0537       0
#XS Ineff= 2 , 0
       0                               0
Bank Sta=8374.032,11599.95
Exp/Cntr=0.3,0.1

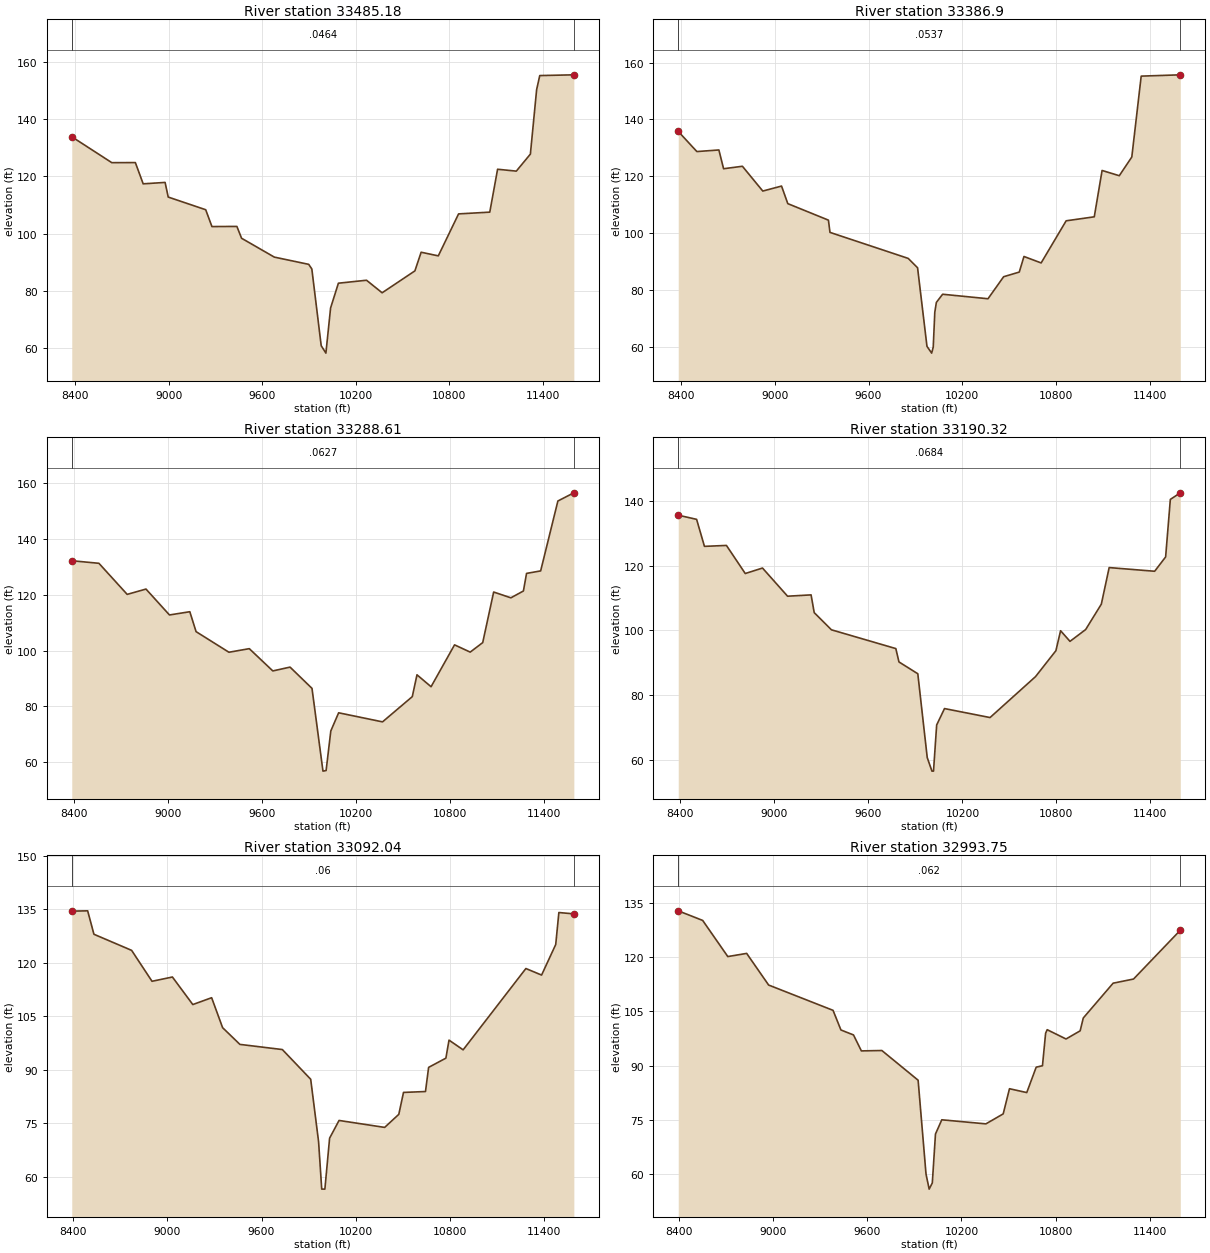
Type RM Length L Ch R = 1 ,33485.18,98.286600,98.286600,98.286600
XS GIS Cut Line= 6
784350.753802752852450.682281074784828.553600639852390.768334657
785259.604397804852368.743331999786695.293213189852427.667097032
787197.384724617852415.908936411787562.887185454852389.593359351
#Sta/Elev= 30
8378.512133.87158635.237124.81038786.203124.83878836.454117.4068 8976.94117.8957
8996.971112.77779237.226108.34719277.237102.45469437.247102.50879467.25498.37134
9677.39891.771569897.77589.241859917.80987.624629977.91260.7864410007.9658.18752
10038.0273.9716210088.11 82.645610268.4383.6839610368.5279.2910210578.6886.95655
10618.6993.4810610728.71 92.207910858.71106.890411058.76107.503611108.81122.5048
11228.91121.8483 11319.1127.806411359.18150.359911379.23155.271911597.76155.5344
#Mann= 3 , 0 , 0
8378.512  0.0464       08378.512  0.0464       011597.76  0.0464       0
#XS Ineff= 2 , 0
       0                10150.08       0
Bank Sta=8378.512,11597.76
Exp/Cntr=0.3,0.1

Type RM Length L Ch R = 1 , 33386.9,98.286500,98.286500,98.286500
XS GIS Cut Line= 6
784346.626301212852525.915377336784708.429210901852485.587273702
785104.872974902 852463.73110646785561.208463103852471.427486509
786691.825259984852526.998934999787554.763502598852494.494829848
#Sta/Elev= 30
8382.174135.80548501.485128.71378642.339129.27588672.478122.67548792.961123.5408
8923.287114.82839043.416116.57949083.443 110.4039343.483 104.5999353.483100.2927
9854.04791.150679914.14987.84733 9974.2560.22537 10004.357.8376110014.3259.93761
10024.3372.2042310034.35 75.670210074.4278.5407410364.8676.9597710464.9584.69939
10565.0486.3379210595.0591.8206110705.08 89.554810865.08104.3644 11045.1105.7675
11095.14122.067411205.21120.222411285.31126.796311345.42155.238111595.77155.6959
#Mann= 3 , 0 , 0
8382.174  0.0537       08382.174  0.0537       011595.77  0.0537       0
#XS Ineff= 2 , 0
       0                10170.13       0
Bank Sta=8382.174,11595.77
Exp/Cntr=0.3,0.1

Type RM Length L Ch R = 1 ,33288.61,98.286600,98.286600,98.286600
XS GIS Cut Line= 6
784342.413091066852602.710707754784702.747633696 852569.77974157
785099.529845625852555.084461764786692.669331282852627.016068876
 787206.21822083852619.510677129787546.681352675 852598.85998255
#Sta/Elev= 30
8384.366 132.1528557.851131.23358738.461120.10558858.681122.00859008.774112.7343
 9138.81113.89379178.811106.7628 9388.8599.385859518.962100.67289669.20792.69664
9779.41494.065749919.67686.449349989.80856.8265810009.8457.03275 10039.971.21309
10089.9877.7121510370.4374.4615610560.6383.4939910590.6491.3106510680.6787.04635
10830.69102.035410930.6999.43532 11010.7102.837211080.72120.948511190.77118.8714
11270.83 121.31811290.87127.6191   11381128.507211491.17153.540211593.12156.4628
#Mann= 3 , 0 , 0
8384.366  0.0627       08384.366  0.0627       011593.12  0.0627       0
#XS Ineff= 2 , 0
       0                10189.47       0
Bank Sta=8384.366,11593.12
Exp/Cntr=0.3,0.1

Type RM Length L Ch R = 1 ,33190.32,98.286500,98.286500,98.286500
XS GIS Cut Line= 6
 784338.22105223852679.120142934784697.336164892852652.782312274
785172.088466257852645.376706868786695.319531769852729.830751032
787013.896540374852729.466357335 787538.45631662852705.070230931
#Sta/Elev= 30
8386.129135.67628503.359134.37658553.499126.02048693.811126.30798813.941117.6179
8924.007119.30969084.038110.59579234.047 111.0089254.055105.50879364.107100.1983
9774.90194.390969794.95290.260339915.26286.598699975.41660.66492 10005.556.47035
10015.5256.4798110035.5770.74641 10085.775.8265410376.3273.0487710666.5885.70965
10796.61 93.733310826.6199.9118110886.6196.6260810986.62100.282911086.63108.1426
11136.65119.454211426.93118.317111497.02 122.74911527.08140.5489 11590.7142.5868
#Mann= 3 , 0 , 0
8386.129  0.0684       08386.129  0.0684       0 11590.7  0.0684       0
#XS Ineff= 2 , 0
       0                10209.39       0
Bank Sta=8386.129,11590.7
Exp/Cntr=0.3,0.1

Type RM Length L Ch R = 1 ,33092.04,98.286600,98.286600,98.286600
XS GIS Cut Line= 6
784333.968059288852756.640605218784803.104078829852733.308690205
785164.078978062852735.189679325786372.831469715852821.616360486
786758.432388753852834.082327783 787530.28672567852810.564514324
#Sta/Elev= 30
8390.344134.44648491.644134.53438531.712127.96418771.988123.44738902.021114.7769
9032.023115.97199162.042108.25399282.104 110.1699352.164101.76269462.30497.08266
9732.96195.633099913.69287.303359963.89669.822749983.97756.5097410004.0656.49655
 10034.270.7843410094.4675.7545410385.23 73.803410475.3677.4650810505.3983.61257
 10645.583.8642410665.5190.6380310775.5393.2179110795.5498.2746510885.5495.55411
11285.66118.355111385.73116.522611475.89 125.08611495.93134.057411591.39133.6805
#Mann= 3 , 0 , 0
8390.344    0.06       08390.344    0.06       011591.39    0.06       0
#XS Ineff= 2 , 0
       0                10235.78       0
Bank Sta=8390.344,11591.39
Exp/Cntr=0.3,0.1

Type RM Length L Ch R = 1 ,32993.75,98.286500,98.286500,98.286500
XS GIS Cut Line= 6
784329.499612677852838.088200308784793.221466184852822.032533079
  785154.1587798852827.940427229786155.310812563852907.477554202
786677.778188199852933.074605331787522.400887638852912.394683748
#Sta/Elev= 30
8396.073132.85228551.765130.19478711.869120.19548831.899121.07168971.903112.3172
9382.165105.31619432.242 99.88859512.41698.509769562.52794.093259692.93594.20294
9923.96385.983759974.19860.036919994.29255.8489810014.3957.5754210034.4971.08825
 10074.7 75.0332 10355.673.9052610465.7876.6651510505.8383.6298610615.9382.56539
10675.9589.5914210715.9789.9917410735.9898.9728710745.9999.9634110865.9997.39352
10955.9999.6442810975.99103.203511166.01112.8284 11296.1113.9813 11593.9127.4822
#Mann= 3 , 0 , 0
8396.073   0.062       08396.073   0.062       0 11593.9   0.062       0
#XS Ineff= 2 , 0
       0                10266.31       0
Bank Sta=8396.073,11593.9
Exp/Cntr=0.3,0.1

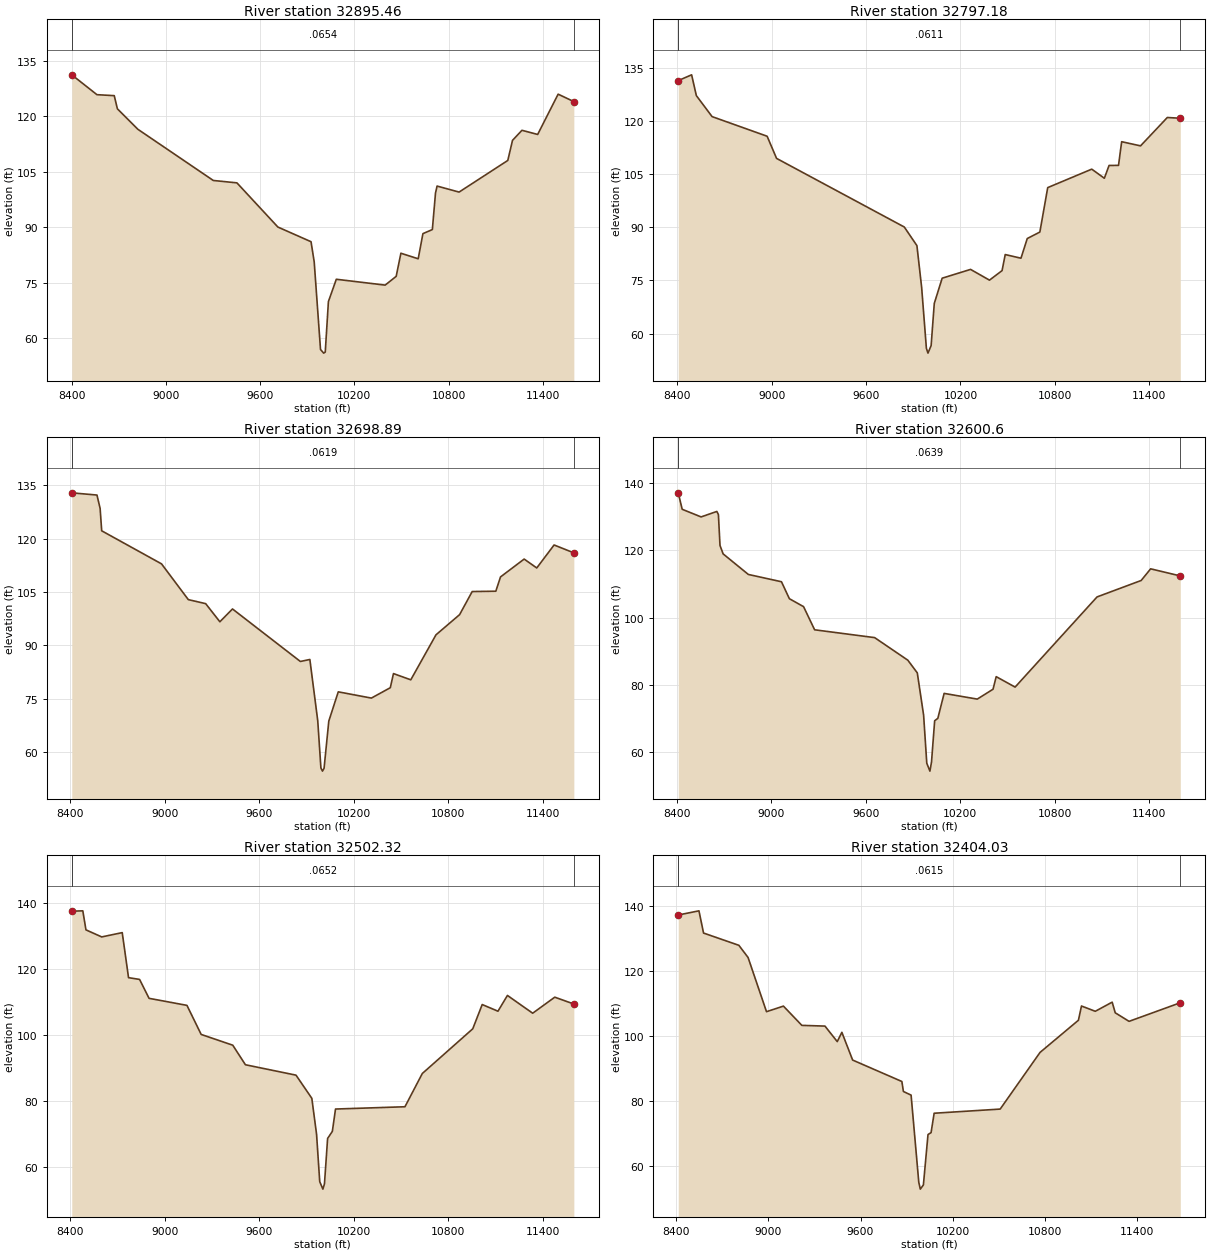
Type RM Length L Ch R = 1 ,32895.46,98.286500,98.286500,98.286500
XS GIS Cut Line= 6
784324.809962495852923.567733195784783.116670132852914.233000234
785143.980462343  852923.8147576786145.177556813853004.609466627
786667.748631626853030.042199597 787514.81866312853010.304278508
#Sta/Elev= 30
8401.673131.17268561.958125.80138671.984125.53928691.989121.98318822.002116.4546
 9302.26102.59489452.546101.95159713.31889.997369924.25786.029179944.346 80.5748
9984.525 56.881510004.6255.8961610014.6756.1761910034.7669.8445110085.0175.87367
 10395.974.2938410465.99 76.663410496.02 82.914110606.1381.4155210636.1488.21194
10696.1789.3201410716.1899.1904110726.18101.0831 10866.299.4570111176.22108.0109
11206.24113.448311266.28116.167811366.33115.044811496.52125.940411596.49123.9336
#Mann= 3 , 0 , 0
8401.673  0.0654       08401.673  0.0654       011596.49  0.0654       0
#XS Ineff= 2 , 0
       0                10296.24       0
Bank Sta=8401.673,11596.49
Exp/Cntr=0.3,0.1

Type RM Length L Ch R = 1 ,32797.18,98.286600,98.286600,98.286600
XS GIS Cut Line= 6
784319.925104725853012.605368033785057.060150832853018.525944769
786097.705890924853097.418007508786595.659817189853123.038771987
786982.283124357853125.588129148787507.466364741853105.244827062
#Sta/Elev= 30
    8406131.45978491.109133.09358521.112 127.2278621.123121.29038971.159115.7421
9031.201109.48279843.135 90.10049923.42984.840839953.53973.017619983.64955.83757
9993.68654.4699810013.7656.5937510033.8268.5053310083.9975.6397810264.5178.12488
10384.7575.0873610464.8677.7857310484.8882.3187110584.9781.28386   10625 86.8471
10705.04 88.672110755.04101.230811035.06106.446711115.07103.873911145.08107.4928
 11205.1107.5068 11225.1114.199211345.18113.022311515.35121.036911597.97120.8272
#Mann= 3 , 0 , 0
    8406  0.0611       0    8406  0.0611       011597.97  0.0611       0
#XS Ineff= 2 , 0
       0                10324.49       0
Bank Sta=8406,11597.97
Exp/Cntr=0.3,0.1

Type RM Length L Ch R = 1 ,32698.89,98.286500,98.286500,98.286500
XS GIS Cut Line= 6
784314.913569894853103.951980216785127.046748847 853121.90008153
786031.601358175 853189.20111303786591.173657119853216.959163398
786980.458304465853218.886264697787500.245735914853198.485120773
#Sta/Elev= 30
8408.584132.87288568.677 132.2468588.678128.49468598.678122.20398978.786112.9134
 9148.99102.86659259.163101.7379 9349.37 96.64369429.553100.24259860.86785.48589
9921.05286.05111 9971.1968.832159991.24555.5701310001.2754.67997 10011.355.46934
10041.3768.7363310101.5276.9552110311.9675.2028710432.1278.1169310452.1582.08678
10562.2580.3353810722.3292.9770410872.3498.6469210952.34105.136911102.35105.2283
11132.36109.250211282.41114.259811362.49111.7638 11472.6118.218211598.03116.0044
#Mann= 3 , 0 , 0
8408.584  0.0619       08408.584  0.0619       011598.03  0.0619       0
#XS Ineff= 2 , 0
       0                10350.99       0
Bank Sta=8408.584,11598.03
Exp/Cntr=0.3,0.1

Type RM Length L Ch R = 1 , 32600.6,98.286600,98.286600,98.286600
XS GIS Cut Line= 6
784309.941034388853194.587741056784957.057787418853211.058586091
785895.874255747853278.152155951 786526.23380506 853310.02450715
787078.025611937853310.440906763787493.051826954853291.380379796
#Sta/Elev= 30
8410.367137.12388435.426132.23678555.434129.96618655.446131.59178665.447130.6521
8675.448121.49478695.451118.98148855.547112.87569065.732110.71079115.833105.6736
9206.016103.31069276.15996.434729657.18594.113249867.78987.409369927.96183.63519
9968.06471.078739988.10456.8096210008.1454.4540810018.1657.17077 10038.269.42357
10058.23 70.128110098.3177.5427810308.6775.8497310408.7978.7853510428.8182.51523
10548.9179.4211411069.01106.201311349.13111.087411409.18114.545411597.53112.4404
#Mann= 3 , 0 , 0
8410.367  0.0639       08410.367  0.0639       011597.53  0.0639       0
#XS Ineff= 2 , 0
       0                10376.88       0
Bank Sta=8410.367,11597.53
Exp/Cntr=0.3,0.1

Type RM Length L Ch R = 1 ,32502.32,98.286500,98.286500,98.286500
XS GIS Cut Line= 6
784304.965168347 853285.28420848 784951.25905934853307.768578887
 785889.98075968853376.261847228786467.332462549853404.493468359
786978.389417201853407.149283692787485.775782555853385.336257756
#Sta/Elev= 30
8411.017137.49618481.054137.6082 8501.06131.84628601.092129.71058731.134131.0129
8771.169117.38588841.253116.85228901.324111.12889141.701108.99939231.905100.2065
9432.45596.944559512.69191.031299833.63787.881749933.88780.871069963.94870.02192
9983.98955.6677710004.0353.3955610014.04 54.982510034.0768.7292210064.1270.87357
10084.1577.6286510524.69 78.320210634.74 88.377810954.77101.905411014.78109.2517
11114.79107.228411174.82112.003911334.91106.626411475.08111.477111596.07109.4104
#Mann= 3 , 0 , 0
8411.017  0.0652       08411.017  0.0652       011596.07  0.0652       0
#XS Ineff= 2 , 0
       0                10402.16       0
Bank Sta=8411.017,11596.07
Exp/Cntr=0.3,0.1

Type RM Length L Ch R = 1 ,32404.03,98.286600,98.286600,98.286600
XS GIS Cut Line= 6
784299.993134621853375.910823253784851.617228335853397.382630537
785768.704122481853466.876479445786411.773813204853500.292083409
 786977.69840418853502.590796397787568.543460995853473.334572227
#Sta/Elev= 30
 8411.56137.09728546.604 138.3828576.613131.5666 8806.81127.81058866.895124.0725
8987.084107.45059097.339109.16319217.617103.25259368.079103.03659448.32798.27796
 9478.42101.12119548.63692.615839869.62786.046699879.65882.978839929.76781.86094
9979.87355.154769989.89453.0372810009.93 54.324710039.9869.7760810060.0170.36785
10080.0476.3088210510.5577.5846510770.6194.9666611020.62104.824311040.63109.1928
11130.65107.573411240.71110.374711260.72107.109511350.81 104.48911684.96110.1936
#Mann= 3 , 0 , 0
 8411.56  0.0615       0 8411.56  0.0615       011684.96  0.0615       0
#XS Ineff= 2 , 0
       0                10427.61       0
Bank Sta=8411.56,11684.96
Exp/Cntr=0.3,0.1

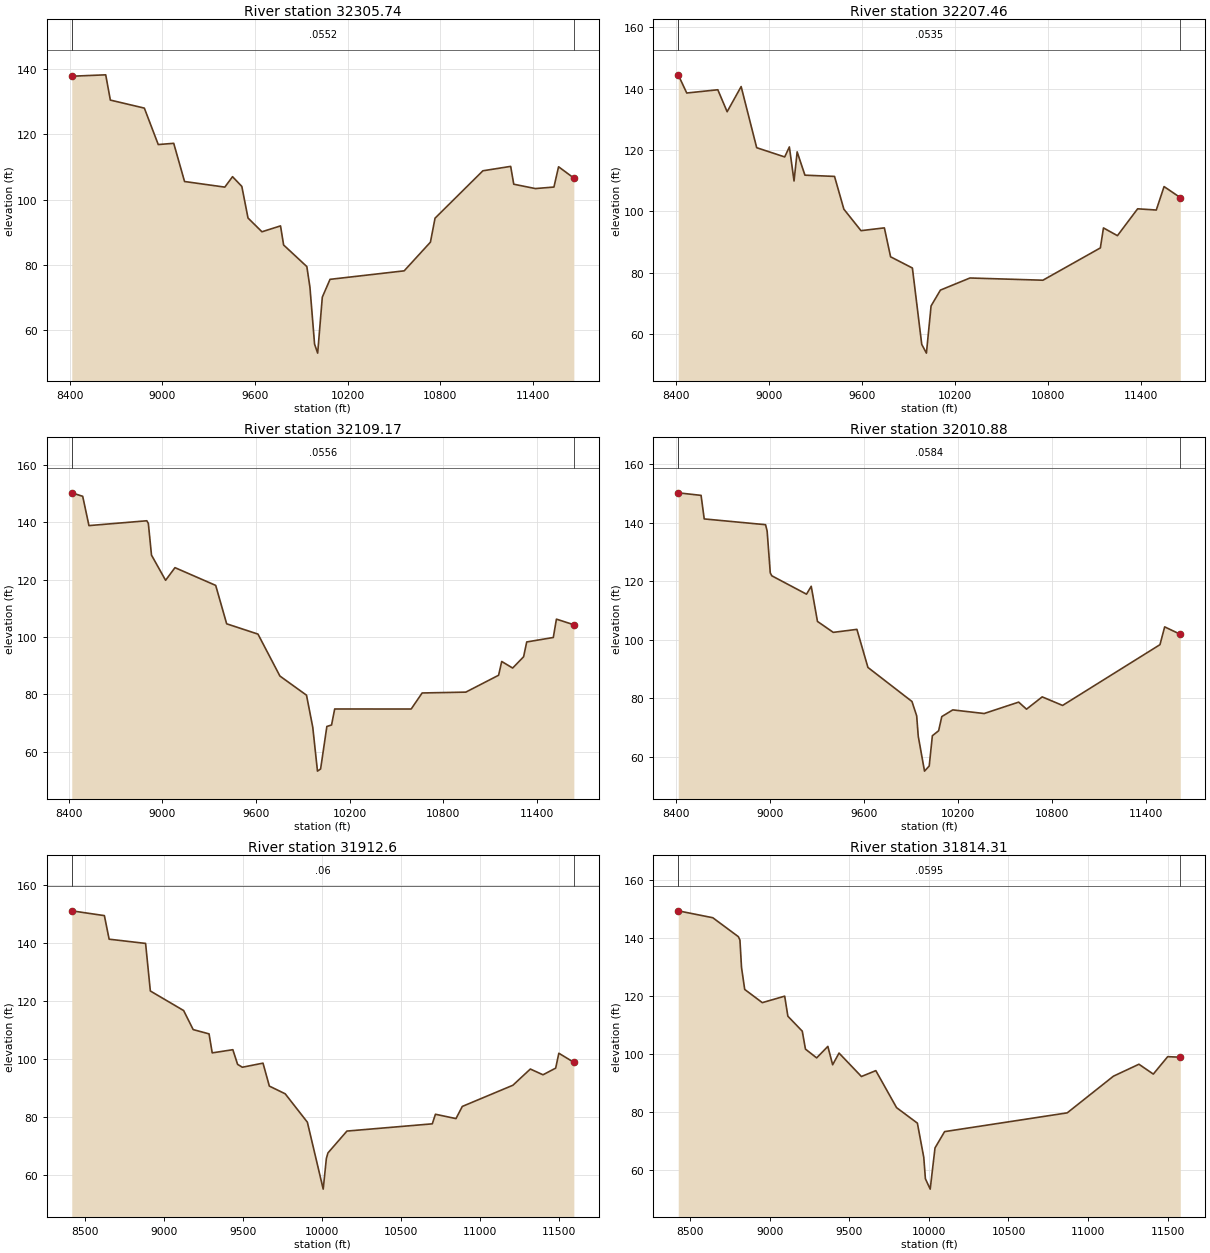
Type RM Length L Ch R = 1 ,32305.74,98.286500,98.286500,98.286500
XS GIS Cut Line= 6
784295.111326744853464.892866851784846.083091548853490.670516712
785878.193767473853572.481229765786317.394200796853596.649198129
786883.285740209853601.601641614787543.771029732853570.316005237
#Sta/Elev= 30
8412.037137.87368632.053 138.3038662.099130.55328882.437128.08618972.586116.9074
9072.855117.28369143.043105.56389403.857103.84159454.023107.04319514.223104.0643
9554.35694.360259644.65590.137979765.05391.94592 9785.1286.082179935.618 79.4577
9955.68473.14686 9985.7755.6454910005.8252.8980710035.8870.0771310085.9875.54013
10566.5478.1513710736.5686.9479510766.5694.31053 11076.6108.852211256.71110.2065
11276.73104.732711416.88103.398711537.12103.860311567.18110.090911666.16 106.621
#Mann= 3 , 0 , 0
8412.037  0.0552       08412.037  0.0552       011666.16  0.0552       0
#XS Ineff= 2 , 0
       0                10447.24       0
Bank Sta=8412.037,11666.16
Exp/Cntr=0.3,0.1

Type RM Length L Ch R = 1 ,32207.46,98.286600,98.286600,98.286600
XS GIS Cut Line= 6
 784290.18203087853554.740487145 784837.68769691 853584.23889821
 785925.18363411853675.169282801786232.633691308853692.737176175
786785.112614624853699.917551247787519.405508492853665.704428798
#Sta/Elev= 30
8415.316144.50658470.178 138.5758670.396139.63638730.511132.47358820.684140.6815
8920.875120.74349101.376117.73189131.468120.99649161.559109.8916 9181.62119.3832
9231.779111.78599422.467111.38259482.685100.69879593.08393.689799743.62794.60332
9783.77285.169899924.27981.513349984.49656.6130610014.61 53.762110044.72 69.1611
10104.8874.31392 10295.278.2617110765.3877.5365711135.4688.0667911155.4794.58513
11245.5492.06266 11375.7100.821111495.93100.419811546.04 108.06411650.69104.4784
#Mann= 3 , 0 , 0
8415.316  0.0535       08415.316  0.0535       011650.69  0.0535       0
#XS Ineff= 2 , 0
       0                 10443.2       0
Bank Sta=8415.316,11650.69
Exp/Cntr=0.3,0.1

Type RM Length L Ch R = 1 ,32109.17,98.286500,98.286500,98.286500
XS GIS Cut Line= 6
784285.012929702853648.959103924 784725.67703532853674.190998755
785949.296771567853774.705796087786339.331997186853791.025616233
786948.873814635853787.980793903787496.289560188853756.200907248
#Sta/Elev= 30
8418.709150.20268488.777148.99348528.823138.78598899.557140.47048909.589139.5268
8929.651128.50569019.933119.73199080.121124.13769341.071 117.9599411.339104.5794
9612.104100.98639752.59686.382739923.10879.707999963.22968.527329993.31953.25947
10013.3854.0118410053.4868.8160210083.5669.3360210103.5974.9025210593.9474.89738
10663.9580.4853310943.9880.7759911154.0886.65921 11174.191.4566111244.1789.16716
11314.25  93.09511334.2998.2578111504.6199.8095911524.65106.201111636.27  104.25
#Mann= 3 , 0 , 0
8418.709  0.0556       08418.709  0.0556       011636.27  0.0556       0
#XS Ineff= 2 , 0
       0                10439.41       0
Bank Sta=8418.709,11636.27
Exp/Cntr=0.3,0.1

Type RM Length L Ch R = 1 ,32010.88,98.286500,98.286500,98.286500
XS GIS Cut Line= 6
784279.577359742853747.995798806784607.965927347853767.809447046
785807.594726281853865.904549166786693.986956364853882.017254756
787164.768877575853864.032850298787474.342578105  853842.1210073
#Sta/Elev= 30
8417.238150.30248562.892149.43218582.933 141.3798973.991139.40668984.022 137.216
9004.086122.90739014.118121.93079234.984115.65579265.108118.35499304.875106.3428
9405.685102.60139556.304103.62739626.59290.614669907.33478.970539937.35974.06298
9947.36767.106699987.37255.1655210017.37 56.926510037.38 67.258710077.3868.97568
10097.3873.7983110167.4276.0970210367.5474.8606610587.6178.7570910637.6276.34234
10737.6280.5478310867.6377.62039 11488.498.3927611518.47104.481611618.11101.9318
#Mann= 3 , 0 , 0
8417.238  0.0584       08417.238  0.0584       011618.11  0.0584       0
#XS Ineff= 2 , 0
       0                10431.36       0
Bank Sta=8417.238,11618.11
Exp/Cntr=0.3,0.1

Type RM Length L Ch R = 1 , 31912.6,98.286600,98.286600,98.286600
XS GIS Cut Line= 6
784278.981026639853835.656764612784608.013031491853857.406342162
 785760.31039741853959.596652339786220.292109876853980.016703055
786784.615117111853979.515481075787449.638083554853938.836475312
#Sta/Elev= 30
8416.839151.09948623.286149.44528653.358141.31188884.073139.85368914.181123.4402
9124.992116.6879 9185.26110.11859285.708108.63729305.798102.0812 9436.38103.1779
9466.51498.105539496.64897.13219 9627.2398.540499667.40990.623649767.718 87.9609
9908.13978.1541410008.2855.06771 10028.365.6746310038.3167.5598210158.4475.09955
10698.6377.5986910718.6380.9032110848.66  79.40310888.6783.6063811208.9790.91376
11319.2196.5071311399.3894.52452 11479.696.8187711499.67101.961711594.6398.82233
#Mann= 3 , 0 , 0
8416.839    0.06       08416.839    0.06       011594.63    0.06       0
#XS Ineff= 2 , 0
       0                10419.04       0
Bank Sta=8416.839,11594.63
Exp/Cntr=0.3,0.1

Type RM Length L Ch R = 1 ,31814.31,98.286500,98.286500,98.286500
XS GIS Cut Line= 6
784278.408315078853919.845363678784712.425174797853952.078129519
785962.966593239854074.084175502786209.676360806854086.145345869
786690.059339345854085.894056858787424.060139072854038.971406883
#Sta/Elev= 30
8424.898149.38268642.053147.00268802.525140.47718812.555 139.3258822.584 129.832
8842.643122.26568953.119117.7204 9093.76119.95189113.851113.03689204.263 107.878
9224.355101.69089294.67698.672759364.996102.62919395.13496.294479435.317100.3306
9575.95892.24653 9666.3794.272849796.96681.501079927.61676.167429967.86664.31378
9977.928 56.995610008.1253.4109410038.3367.6160510098.5973.2432110869.05 79.7082
11159.4192.35547 11319.896.4805911410.0193.0821811500.3299.0864511579.6998.90608
#Mann= 3 , 0 , 0
8424.898  0.0595       08424.898  0.0595       011579.69  0.0595       0
#XS Ineff= 2 , 0
       0                10415.52       0
Bank Sta=8424.898,11579.69
Exp/Cntr=0.3,0.1

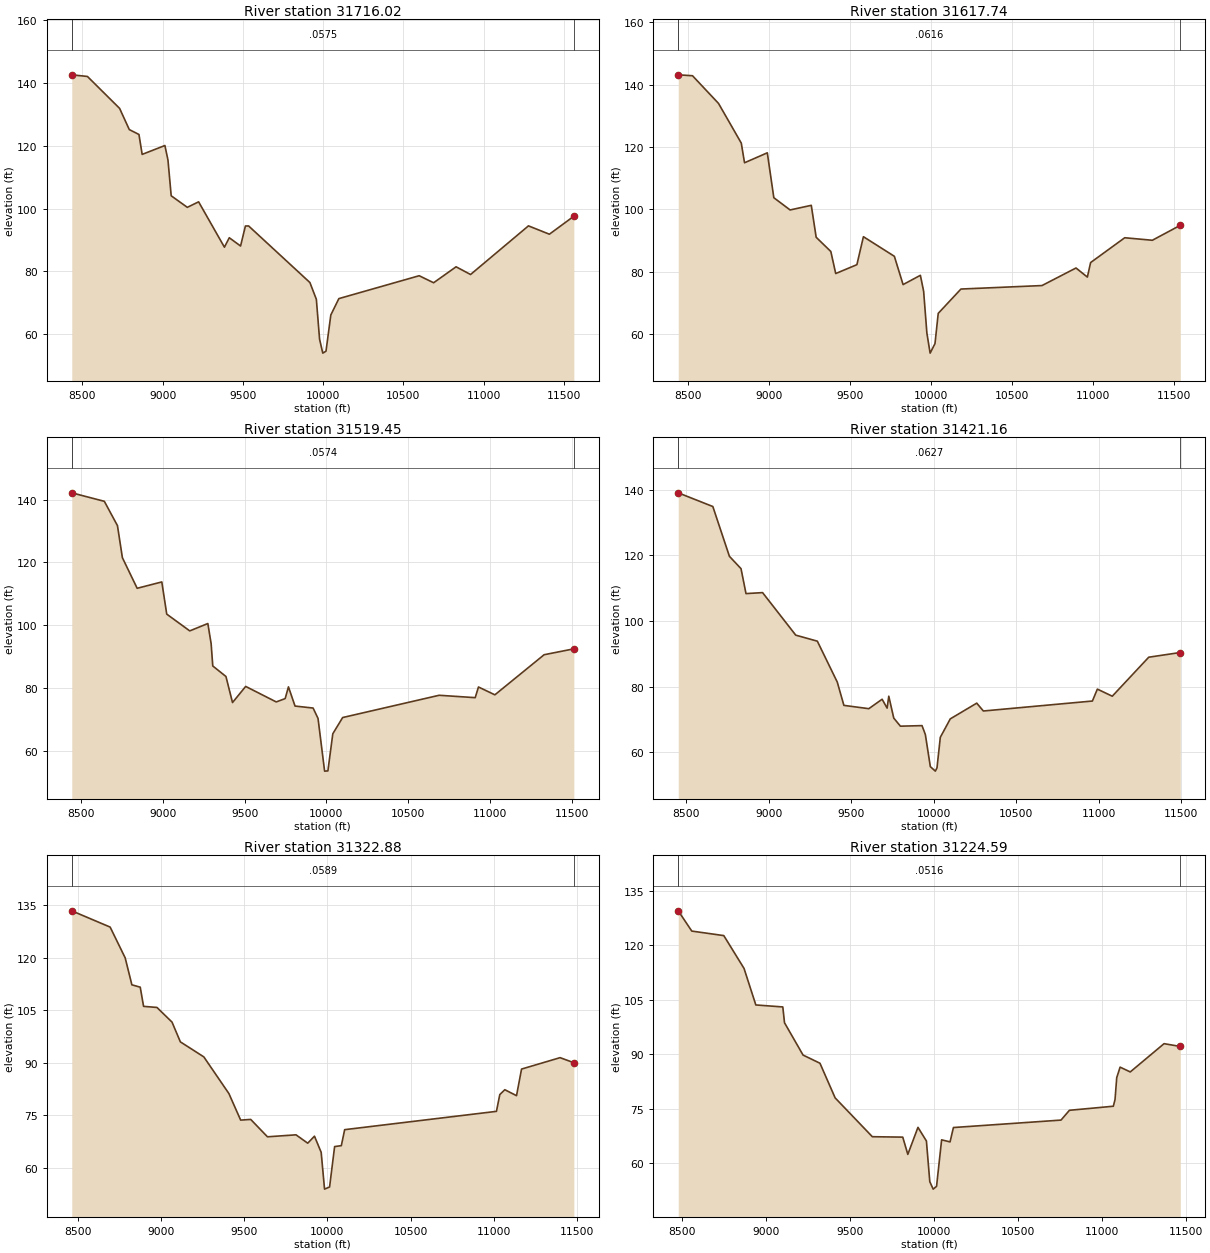
Type RM Length L Ch R = 1 ,31716.02,98.286600,98.286600,98.286600
XS GIS Cut Line= 6
784277.748944219854016.772879507 784703.35641306854050.345396933
785782.698677378854156.812116669786167.128290174854177.890803624
786677.430447881854176.686085691787396.743474943854126.202698488
#Sta/Elev= 30
8433.525 142.6558531.029142.13538731.685131.95158791.881125.20058852.078123.6415
8872.159117.28619013.819120.11989032.895115.48529052.987 104.0969153.454 100.407
9223.828102.16529384.68387.707669414.84490.719219485.21888.080339515.37994.45903
9535.485 94.46939917.25276.434599957.38671.082479977.42758.381139997.46753.93076
 10017.554.5463110047.5666.0987810097.6571.3129110597.9978.6064810688.0176.36598
10828.0581.4543410918.1578.9946711278.9194.5029811409.2891.8408711561.6597.57374
#Mann= 3 , 0 , 0
8433.525  0.0575       08433.525  0.0575       011561.65  0.0575       0
#XS Ineff= 2 , 0
       0                10412.41       0
Bank Sta=8433.525,11561.65
Exp/Cntr=0.3,0.1

Type RM Length L Ch R = 1 ,31617.74,98.286500,98.286500,98.286500
XS GIS Cut Line= 6
784277.111505851854110.476319055 784702.76525469854145.675790072
785735.957897158854252.225806957786132.825562088854273.791028086
786604.171425498854273.361815402787366.842754695854216.515078015
#Sta/Elev= 30
 8437.64143.19928525.776142.9058 8686.35134.02658826.853121.29528846.925114.9791
8987.587 118.1729027.782103.76999128.27299.838479259.013101.32159289.18791.07361
9379.71186.509129409.88679.436199540.64282.279259580.87591.256899771.91584.96551
9825.79875.891429932.54678.866619952.58773.771329972.62960.361259992.67153.89543
10022.7156.9462310042.7466.6504610182.9274.4594810683.1675.5745210893.3581.21242
10963.4478.2968110983.4782.9558211194.0690.9158911364.6390.1087511537.2494.91813
#Mann= 3 , 0 , 0
 8437.64  0.0616       0 8437.64  0.0616       011537.24  0.0616       0
#XS Ineff= 2 , 0
       09903.443        10401.55       0
Bank Sta=8437.64,11537.24
Exp/Cntr=0.3,0.1

Type RM Length L Ch R = 1 ,31519.45,98.286600,98.286600,98.286600
XS GIS Cut Line= 6
784276.503512735854199.851306714 784709.91230184854236.982074379
785807.803280629854355.016280582786098.934019011854374.917540167
 786530.83656752854375.231218006787335.855778118854310.108395024
#Sta/Elev= 30
8442.576 142.2018641.757139.49278722.067 131.7348752.183121.51528842.531111.7495
8993.258113.77889023.412103.51689164.14298.163759274.832100.50949294.95794.11218
 9305.0286.972119385.52283.625919425.77375.307679506.27480.451289693.29775.50428
9747.77976.570219767.90480.309229808.13874.186489918.69373.553099948.844 70.2308
9989.03453.43265 10009.153.5007110039.1965.3522410099.3670.5218410689.81  77.627
10910.1276.8663910930.1680.2681411030.4877.7722711331.6590.5600411513.4492.43569
#Mann= 3 , 0 , 0
8442.576  0.0574       08442.576  0.0574       011513.44  0.0574       0
#XS Ineff= 2 , 0
       09869.486        10388.45       0
Bank Sta=8442.576,11513.44
Exp/Cntr=0.3,0.1

Type RM Length L Ch R = 1 ,31421.16,98.286500,98.286500,98.286500
XS GIS Cut Line= 6
784275.892745749854289.634053243784895.842430059854345.898537413
785846.479391461 854458.16473489 786115.01284433854479.509385468
786660.495776375854466.401037964787305.076893168854403.073190384
#Sta/Elev= 30
8451.667139.04528661.433134.87288761.898119.71128832.224115.94758862.364108.3608
8962.829108.65999163.89895.706879294.70493.878199415.44881.423829455.69674.32433
9606.74873.319029687.35676.194119717.58473.49539 9727.6677.121369757.88970.45195
9798.19367.993499929.18168.159249949.333 65.45519979.56155.67094 10009.854.30478
10019.8855.2981210040.0264.6059910100.3770.2125410260.8375.0042910300.8972.61393
10961.7375.6482310991.8479.2780611082.1677.1180811303.2888.9935211494.5390.42351
#Mann= 3 , 0 , 0
8451.667  0.0627       08451.667  0.0627       011494.53  0.0627       0
#XS Ineff= 2 , 0
       09839.966         10385.1       0
Bank Sta=8451.667,11494.53
Exp/Cntr=0.3,0.1

Type RM Length L Ch R = 1 ,31322.88,98.286600,98.286600,98.286600
XS GIS Cut Line= 6
784275.242554879854385.212110643784881.665635686854440.890812981
 786074.26409372854576.577072706786240.677224029854579.184217763
786570.436239515854563.868611981787277.011326339 854487.84265754
#Sta/Elev= 30
8464.116133.34158694.678 128.7018785.099119.91388825.287112.21598875.521 111.547
8895.614106.07138975.989105.7578 9066.41101.58219116.69895.933399257.52991.65037
9408.45981.166029478.93673.598349539.34673.796339640.06368.833979811.38269.39701
9882.03167.012069922.40369.011729962.77564.399149982.961 53.896710013.2354.51138
10043.4966.0416110083.7566.3052510103.8770.8708411015.8876.0983611035.9980.88486
11066.1582.2749811136.5480.5752411166.7188.1687711398.33 91.427311480.94 89.9822
#Mann= 3 , 0 , 0
8464.116  0.0589       08464.116  0.0589       011480.94  0.0589       0
#XS Ineff= 2 , 0
       09812.888        10390.25       0
Bank Sta=8464.116,11480.94
Exp/Cntr=0.3,0.1

Type RM Length L Ch R = 1 ,31224.59,98.286500,98.286500,98.286500
XS GIS Cut Line= 6
784274.538825435854488.660338474784866.652865538854543.121150559
785787.563951754854648.841109209 786036.54967048854668.771997767
786426.553902078854659.733359776787250.970246228854566.497348491
#Sta/Elev= 30
8477.401129.4979 8558.13123.92588748.891122.68268869.444113.65438939.767103.5993
9100.541103.05319110.59998.703439221.24589.810549321.83387.567279412.36178.02941
9633.85467.353569815.13667.23572 9845.3562.490959905.77769.928679956.13366.17092
9976.275 54.98059996.41852.9309210016.5453.6915310046.7166.4949410096.9765.92619
10117.0369.8756210758.04 71.923210808.2374.6192911069.8475.7377211079.9277.58424
11089.99  83.58911110.15 86.493411170.6185.1748611372.1492.9521111468.89 92.1781
#Mann= 3 , 0 , 0
8477.401  0.0516       08477.401  0.0516       011468.89  0.0516       0
#XS Ineff= 2 , 0
       09783.975        10395.36       0
Bank Sta=8477.401,11468.89
Exp/Cntr=0.3,0.1

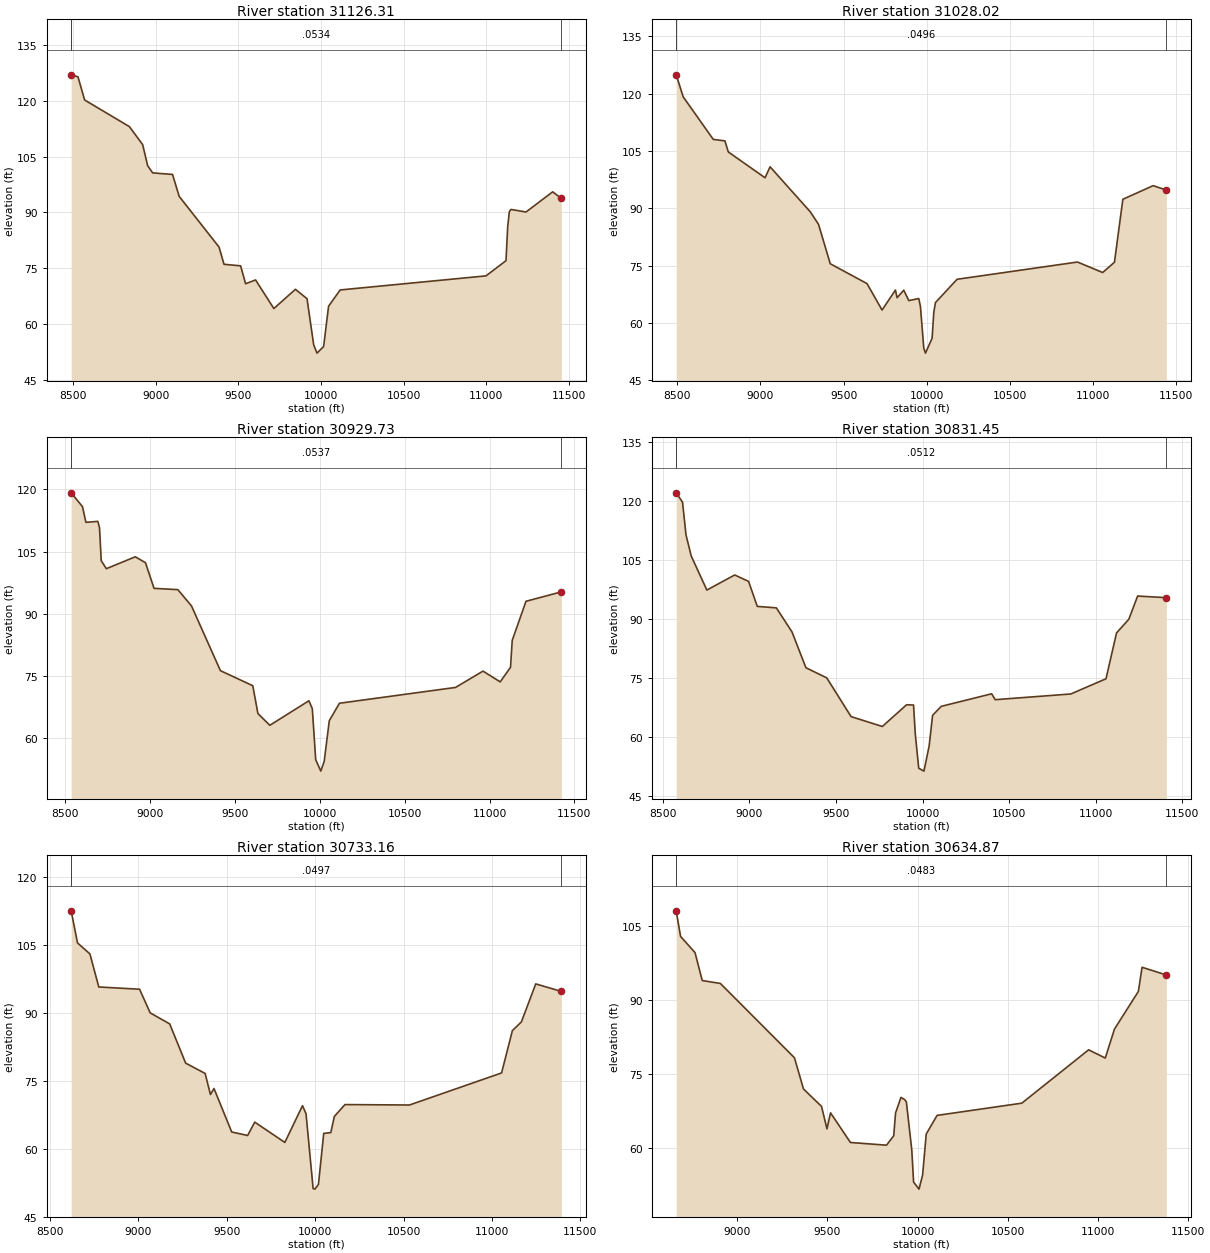
Type RM Length L Ch R = 1 ,31126.31,98.286500,98.286500,98.286500
XS GIS Cut Line= 6
784273.793417129854598.235358907 785733.81953776854743.053128566
786027.766073765854758.836397217786218.867367638854755.511920223
786542.297763192854728.491783034787227.198616596854638.297372686
#Sta/Elev= 30
 8487.19126.92478528.524126.37868568.684120.16938839.787113.02498920.137108.1951
8950.286 102.5378980.434100.61269101.026100.19049141.22494.30509 9382.5280.71082
9412.69176.085219513.26275.661979543.43370.861749603.77571.887929714.40364.20785
9845.09369.37264 9915.4266.846499955.60554.488069975.673 52.2439 10015.8 54.0137
10045.8764.8276910115.9969.1960510999.1372.9759511120.2277.0516311130.3186.09042
 11140.490.2150111150.4990.7938911241.3190.1155511402.7695.5249711455.4393.75952
#Mann= 3 , 0 , 0
 8487.19  0.0534       0 8487.19  0.0534       011455.43  0.0534       0
#XS Ineff= 2 , 0
       09750.131        10396.78       0
Bank Sta=8487.19,11455.43
Exp/Cntr=0.3,0.1

Type RM Length L Ch R = 1 ,31028.02,98.286600,98.286600,98.286600
XS GIS Cut Line= 6
784273.034239025 854709.83453972785619.148062562854834.910391017
 785943.40299715  854849.8395845786136.927200995854845.702066854
786354.529132445 854827.90748453787203.832092209854708.873813691
#Sta/Elev= 30
8493.696124.88918535.808119.12688716.458 108.0028786.749107.61348806.832104.7252
9027.75797.963179057.899100.83519299.03789.089359349.27485.778749419.60675.48144
9640.64870.283629731.02963.360319811.34268.595049821.38266.599339861.51468.56456
9891.58665.841489951.72966.381849961.74664.273829981.77553.41777 9991.7952.10044
10031.8355.9982410041.8462.7289910051.8565.3178610181.8871.4122210905.3975.92466
11056.9973.1874211127.7475.8645211178.2792.33567 11360.295.8991311439.8794.74614
#Mann= 3 , 0 , 0
8493.696  0.0496       08493.696  0.0496       011439.87  0.0496       0
#XS Ineff= 2 , 0
       09712.672        10396.27       0
Bank Sta=8493.696,11439.87
Exp/Cntr=0.3,0.1

Type RM Length L Ch R = 1 ,30929.73,98.286500,98.286500,98.286500
XS GIS Cut Line= 6
784308.470141389854823.948420739785584.298847261854933.869980745
785956.848100482854943.634545714786133.220618171854933.877986938
786349.511047766854909.096209782787181.049958466854777.685156426
#Sta/Elev= 30
8533.853119.17838600.602115.8446 8620.68112.04788690.951 112.287 8700.99110.7408
8711.029102.79828741.145100.86678911.804 103.7348972.036 102.306 9022.2396.11939
9162.77395.806369243.083 91.87819413.74276.244859604.45672.610579634.55165.91211
9704.77263.055669935.27268.978529955.29867.067889975.32354.7666210005.3551.99576
10025.3554.3472510055.3664.1638410115.3668.3826810799.5772.1977810961.63 76.1397
11062.9373.53939 11123.777.0606811133.8383.5634211214.86 92.995211423.4795.26681
#Mann= 3 , 0 , 0
8533.853  0.0537       08533.853  0.0537       011423.47  0.0537       0
#XS Ineff= 2 , 0
       0 9672.91        10406.77       0
Bank Sta=8533.853,11423.47
Exp/Cntr=0.3,0.1

Type RM Length L Ch R = 1 ,30831.45,98.286600,98.286600,98.286600
XS GIS Cut Line= 6
784348.483899526854937.833732342785447.383809609855025.432414001
785717.436663817855039.971241252785908.341471815855040.583587437
786248.504216469855005.751965109787158.715881658 854845.14318434
#Sta/Elev= 30
8577.118122.12858613.755119.74848633.822111.41458663.921106.05198754.22197.38747
8914.753101.22778995.01999.598399045.18593.234459155.55192.85822 9245.8586.73292
9326.11677.628489446.46375.046529586.86165.192189767.29262.680179907.48668.21377
9947.52468.131589957.52960.768569977.53752.0575910007.5551.3220810037.5557.71855
10057.5565.5188210107.5667.8045810398.6570.9974210418.8669.4986310855.3470.94931
11058.68 74.815111119.5786.4823211190.6189.9734611241.3595.8649511407.3595.45727
#Mann= 3 , 0 , 0
8577.118  0.0512       08577.118  0.0512       011407.35  0.0512       0
#XS Ineff= 2 , 0
       09631.874        10416.37       0
Bank Sta=8577.118,11407.35
Exp/Cntr=0.3,0.1

Type RM Length L Ch R = 1 ,30733.16,98.286500,98.286500,98.286500
XS GIS Cut Line= 6
784389.302948583855054.011025792 785385.78503188855124.628812944
785598.401522152855135.427738989785862.756372985855138.080998301
786128.297432641855108.969858077787137.602967947854908.912801262
#Sta/Elev= 30
8620.241112.61778656.047105.52578726.262103.09558776.41595.792819007.05295.29242
9067.20590.067569177.487  87.6379267.71778.96853 9377.9876.679279408.03972.02835
9428.07873.354429528.27563.743119618.451 62.97579658.50465.926339828.723  61.441
9928.75969.565289948.76567.754829988.778 51.2448 9998.7851.1211710018.78 52.1474
10048.7963.4398910088.7963.6048710108.8167.1806610168.9469.8045510533.7769.70889
11054.7276.7965911115.8986.1507311166.7188.07507   1124896.4710611392.8994.80843
#Mann= 3 , 0 , 0
8620.241  0.0497       08620.241  0.0497       011392.89  0.0497       0
#XS Ineff= 2 , 0
       09589.181        10425.52       0
Bank Sta=8620.241,11392.89
Exp/Cntr=0.3,0.1

Type RM Length L Ch R = 1 ,30634.87,98.286600,98.286600,98.286600
XS GIS Cut Line= 6
784430.914885869855172.445001127 785505.80394628855233.932020554
785895.344265472855230.987215201786066.058068736 855205.32557656
786760.613237411855038.450850893787117.645812241854969.191557272
#Sta/Elev= 30
8661.663108.09938685.807102.90838766.00399.620988806.10193.941518906.34793.35631
9317.13578.264839367.21171.930639467.33168.388139497.35863.831399517.37667.07541
9627.47661.06134  9827.6 60.51089867.61162.433879877.61467.050229907.622 70.2104
9927.62769.794619937.62869.301579967.62859.548349977.62853.0244110007.6351.58832
10027.6554.4530110047.6662.7705210107.79 66.559310577.5769.0415410947.9879.87779
11040.1278.2053811091.1184.0781411223.6991.7266911244.0996.6389511378.9595.06765
#Mann= 3 , 0 , 0
8661.663  0.0483       08661.663  0.0483       011378.95  0.0483       0
#XS Ineff= 2 , 0
       09543.216         10433.1       0
Bank Sta=8661.663,11378.95
Exp/Cntr=0.3,0.1