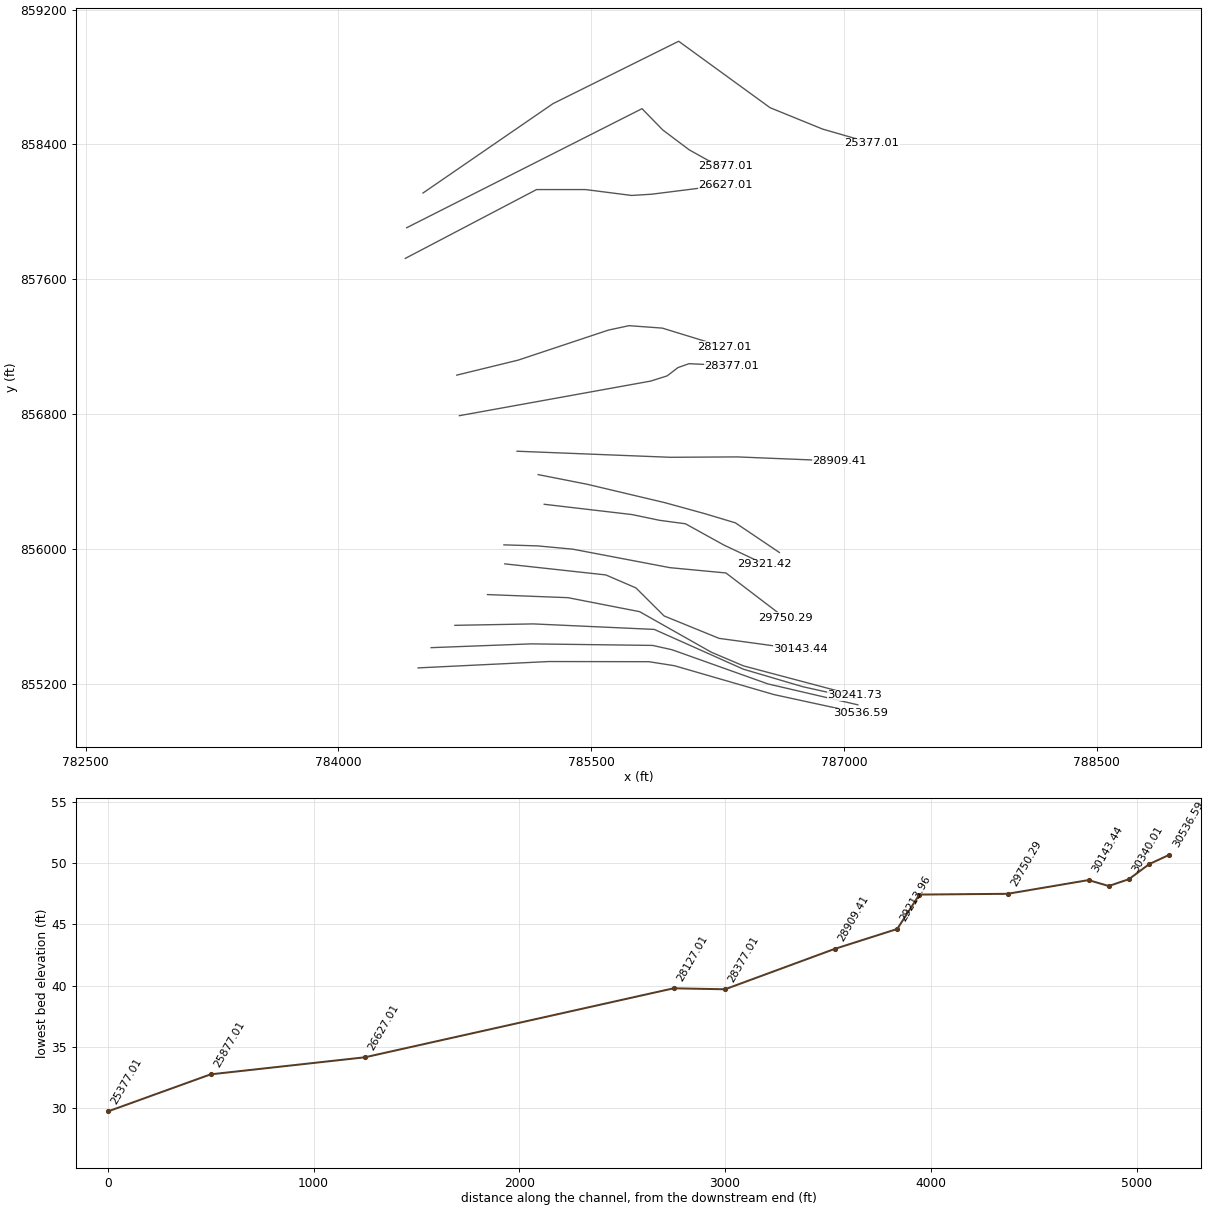
HEC-RAS study 15937_ras.prj: 15937

--- 15937_ras.g01 (geometry) --- (continued)

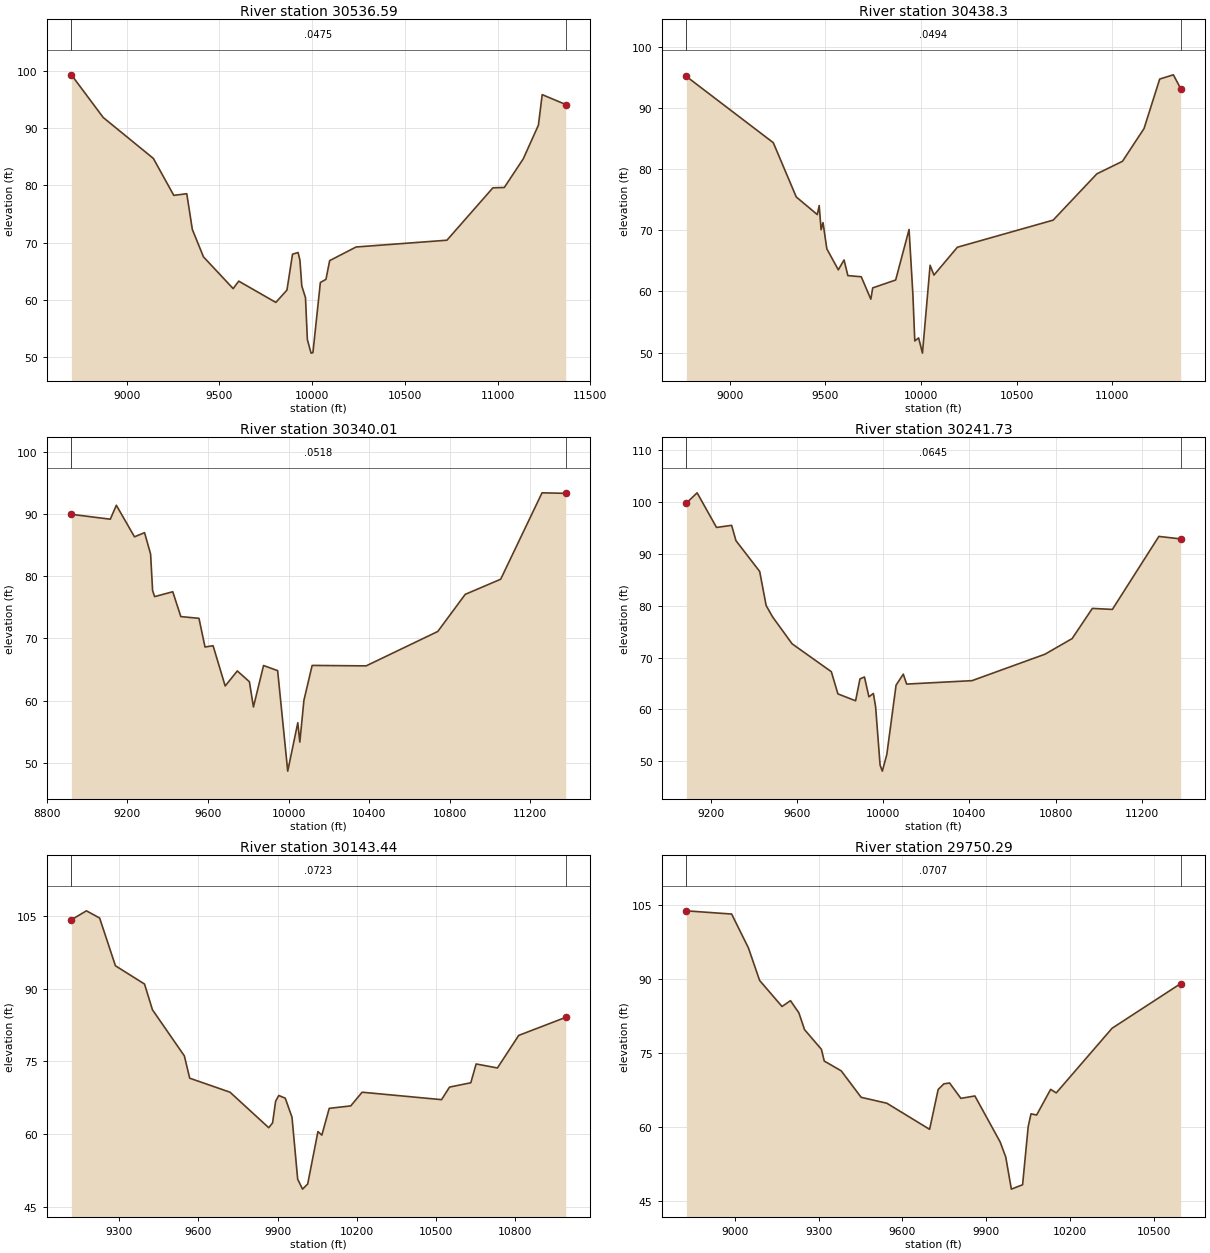
Type RM Length L Ch R = 1 ,30536.59,98.286500,98.286500,98.286500
XS GIS Cut Line= 6
784473.654336712855294.088053507785248.925922603855331.798492883
785843.042336803855330.842118939785994.582735057855306.924765788
786586.739690816855135.293414453787099.443137178855024.171065628
#Sta/Elev= 30
8702.13599.344838873.83391.880999144.22684.720439254.32178.262659324.363 78.5485
9354.38172.293479414.416 67.5019 9574.4761.952819604.47463.258879804.50659.53928
9864.51561.694139894.51667.974629924.51668.258789934.51766.919559944.51762.41465
 9964.5360.360959974.53753.042669994.55150.6667610004.5650.7502710044.6763.02846
10074.7663.5718710094.8966.8469510237.0869.2291610727.1170.4162310974.9679.58017
11036.4679.6388811138.88 84.661811220.4490.5473311240.8295.8813211367.6394.15271
#Mann= 3 , 0 , 0
8702.135  0.0475       08702.135  0.0475       011367.63  0.0475       0
#XS Ineff= 2 , 0
       0 9493.76        10440.54       0
Bank Sta=8702.135,11367.63
Exp/Cntr=0.3,0.1

Type RM Length L Ch R = 1 , 30438.3,98.286600,98.286600,98.286600
XS GIS Cut Line= 6
784550.798414978855414.140249982785143.914504543855436.655186023
785864.819006897855427.460611265785979.796677802855401.838952609
 786549.05072748 855199.03932931787082.628224084855074.958966401
#Sta/Elev= 30
8773.07695.124329227.71584.29545 9347.7575.428899457.75672.548099467.75674.02477
9477.75670.068979487.75671.231139507.75666.950999567.75763.516349597.75765.12797
9617.75762.573279687.75762.384289737.75758.722619747.75760.568139867.75761.85727
9937.75770.109769957.75759.516299967.75951.89645 9987.7752.39071 10007.849.90384
10047.8764.2566510067.9662.6589710190.41 67.208510691.2771.6374310919.9479.20233
11053.9881.2555811166.6586.61117 11248.694.6954311320.0495.3846511358.3793.12567
#Mann= 3 , 0 , 0
8773.076  0.0494       08773.076  0.0494       011358.37  0.0494       0
#XS Ineff= 2 , 0
       09441.422         10447.8       0
Bank Sta=8773.076,11358.37
Exp/Cntr=0.3,0.1

Type RM Length L Ch R = 1 ,30340.01,98.286500,98.286500,98.286500
XS GIS Cut Line= 6
 784691.96686714855546.594600154785157.063511608855555.075877729
785874.604636948855522.450477486786403.245840784 855286.44174748
786758.582005259855181.698775067787070.106411937855112.779950029
#Sta/Elev= 30
8921.93589.918679115.09789.132729145.10291.374869235.10986.307599285.11286.97472
9315.11383.537969325.11377.665089335.11376.701619425.132 77.48449465.15173.49646
9555.194 73.21469585.20868.610919625.24468.81299 9685.3462.350549745.43564.76658
9805.53163.037859825.563 58.98449875.64365.637799945.68864.811759995.70148.67766
10045.7356.4476510055.7553.3441810076.0360.0334610116.9165.6521210384.9865.57992
10740.4371.1043410876.62  77.06211052.7379.4963411257.9393.3695111375.5193.28765
#Mann= 3 , 0 , 0
8921.935  0.0518       08921.935  0.0518       011375.51  0.0518       0
#XS Ineff= 2 , 0
       09397.094         10476.8       0
Bank Sta=8921.935,11375.51
Exp/Cntr=0.3,0.1

Type RM Length L Ch R = 1 ,30241.73,98.286500,98.286500,98.286500
XS GIS Cut Line= 6
784885.064358957855729.092226037785362.921347376855710.672210317
785787.617265139855627.747964214786213.388185686855387.071815598
786404.661707831855305.857902785787064.114894158 855130.87677924
#Sta/Elev= 30
 9087.2199.770029137.147101.74959227.164 95.07859297.18995.487639317.19692.53942
9427.31186.602459457.36780.034939487.43877.829589577.83272.653779759.75567.28264
9790.23763.005949872.27561.680439892.54265.889459913.38866.264699934.076 62.4471
9954.81363.089229965.18160.524489985.91849.303889996.28648.1209310017.2251.34707
10060.0164.6832410093.4866.8117210109.1664.89571 10412.365.5557110750.7770.64918
10876.8273.6645410970.5579.4744511063.4979.2858411279.17 93.348311380.4292.87263
#Mann= 3 , 0 , 0
 9087.21  0.0645       0 9087.21  0.0645       011380.42  0.0645       0
#XS Ineff= 2 , 0
       0                10487.33       0
Bank Sta=9087.21,11380.42
Exp/Cntr=0.3,0.1

Type RM Length L Ch R = 1 ,30143.44,393.146300,393.146300,393.146300
XS GIS Cut Line= 6
784987.979964226855911.298078507785587.234610349855845.664116874
785765.790049851 855768.74168238785933.142399251855602.237389162
786259.056873709855469.368351221786741.695762604855403.396129012
#Sta/Elev= 30
9117.985104.18469175.021106.02659225.059104.54819285.14494.687849395.44890.92184
9425.56385.60803 9546.5276.097749566.79771.493649719.82968.602839866.613 61.2786
9881.22162.267889892.719 66.73659904.65567.925099929.31967.367559954.90963.43494
  9976.450.659719994.87848.60417 10014.449.6686810053.2760.4825110068.0759.74323
10096.0965.2719710177.7165.77741 10220.968.6004210522.1567.0672210552.4369.65362
10633.1870.5529110653.36 74.430610734.1173.6057910814.8580.3225510993.1984.05044
#Mann= 3 , 0 , 0
9117.985  0.0723       09117.985  0.0723       010993.19  0.0723       0
#XS Ineff= 2 , 0
       09579.508        10462.67       0
Bank Sta=9117.985,10993.19
Exp/Cntr=0.3,0.1

Type RM Length L Ch R = 1 ,29750.29,428.875600,428.875600,428.875600
XS GIS Cut Line= 6
784982.792445895856024.126601306785182.068398088856017.967581972
785392.002023667 855998.37957035 785967.79384324855888.763338938
786299.886187017 855857.35443899786650.580631435855589.993327901
#Sta/Elev= 30
 8825.61  103.788987.906103.12889048.00896.281159088.12989.695439168.46384.42791
 9198.6585.609729228.83783.144859249.01379.757689309.62175.76207 9319.7373.39695
9380.63771.409049451.91966.057789543.91764.864329697.24759.581749727.91367.63756
9748.35768.783499768.79468.956179809.27465.845839859.52266.330259949.96657.03454
9970.07653.980499990.18647.4860410030.4148.3688710050.5160.1333410060.5762.71879
10080.6862.4768910130.9567.6636310151.0666.9519410351.0380.0259410596.9689.06417
#Mann= 3 , 0 , 0
 8825.61  0.0707       0 8825.61  0.0707       010596.96  0.0707       0
#XS Ineff= 2 , 0
       09486.767        10132.51       0
Bank Sta=8825.61,10596.96
Exp/Cntr=0.3,0.1

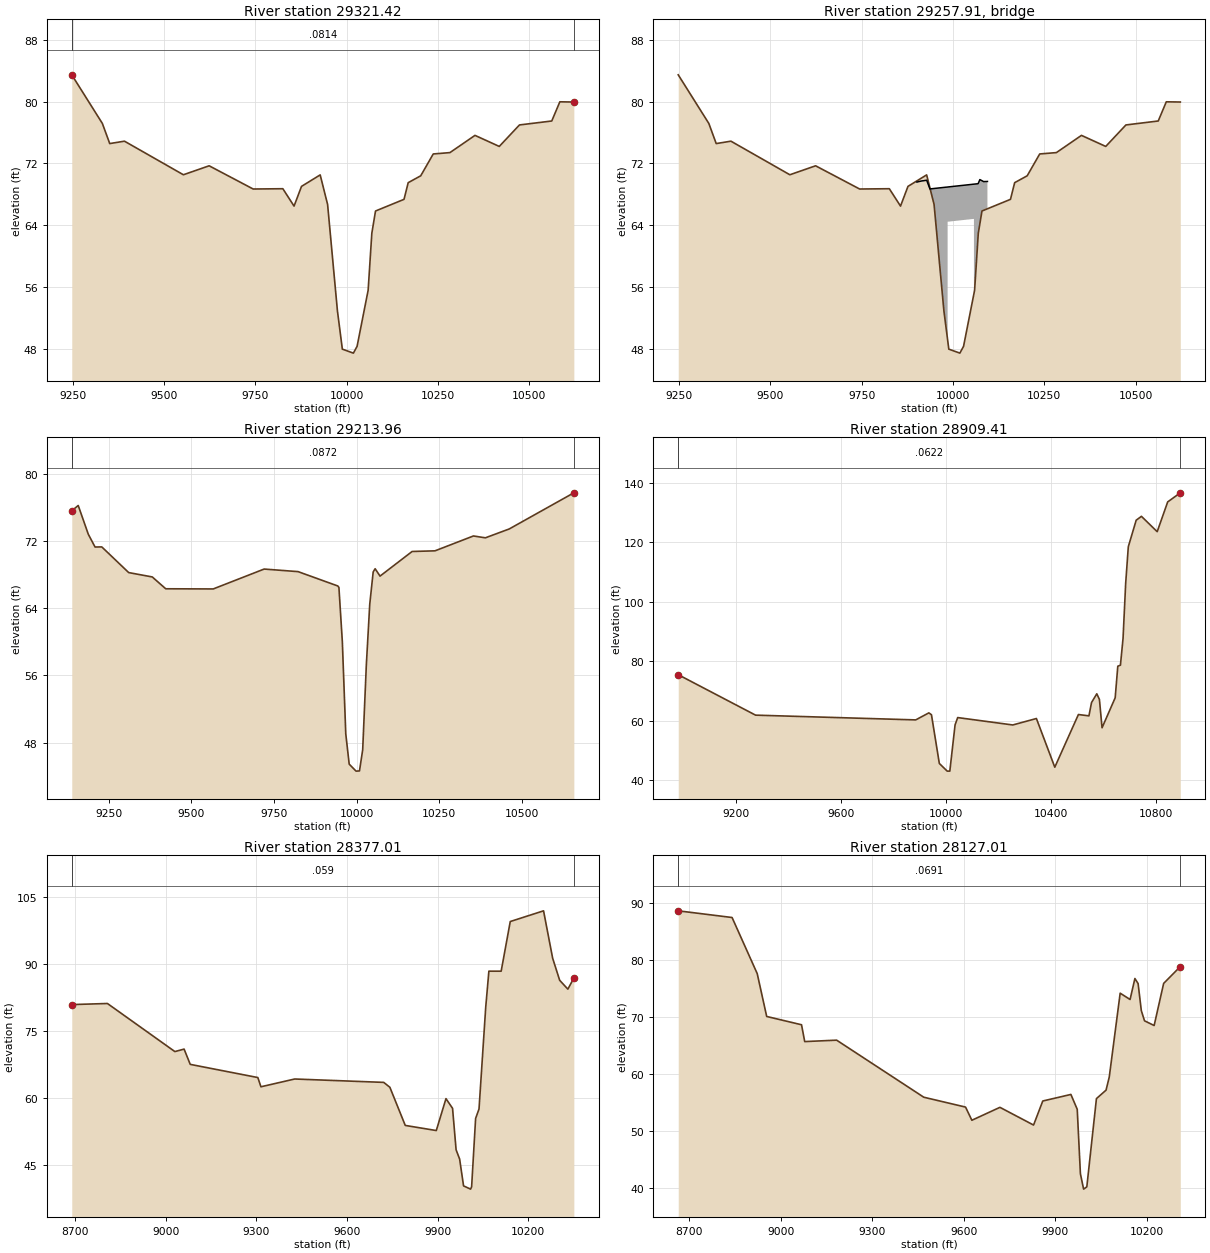
Type RM Length L Ch R = 1 ,29321.42,107.459300,107.459300,107.459300
XS GIS Cut Line= 6
785221.915342391856264.803984761785743.098356754 856203.77187705
785906.256379306856169.735600829786059.689751506856149.205783442
786288.719969153856022.547969624786529.675194502855909.093715549
#Sta/Elev= 30
9247.92683.485779331.684 77.18489351.84674.57692 9392.1774.887939553.46670.53671
9623.95971.697789744.50368.688849825.747 68.72679856.393 66.47649876.82469.03122
  9927.970.51968 9948.2266.687969975.107 52.90419988.57747.9405310018.8447.42371
10028.9348.30518 10059.255.5744710069.2962.9600910079.3865.83901 10157.467.35083
10168.8369.5119110203.1170.40141 10237.4  73.232 10283.173.4074510351.6775.63936
10418.1374.2072610473.3976.9907510561.8277.5036410583.9279.9887510622.2579.96228
#Mann= 3 , 0 , 0
9247.926  0.0814       09247.926  0.0814       010622.25  0.0814       0
#XS Ineff= 2 , 0
       09896.823         10113.1       0
Bank Sta=9247.926,10622.25
Exp/Cntr=0.3,0.1

Type RM Length L Ch R = 3 ,29257.91,,,
BEGIN DESCRIPTION:
END DESCRIPTION:
Bridge Culvert--1,0,-1,-1, 0
Deck Dist Width WeirC Skew NumUp NumDn MinLoCord MaxHiCord MaxSubmerge Is_Ogee
24.229650,59.000000,2.6,0, 14, 14, , , 0.95, 0, 0,0,,
 9901.33 9907.23 9915.93 9917.62 9928.02 9936.83 9985.34 9985.3410057.3410057.34
10068.8010073.5610083.9610094.33
   69.59   69.66   69.75   69.75   69.83   68.70   68.95   68.95   69.32   69.32
   69.38   69.91   69.65   69.67
 -930.41 -930.34 -930.25 -930.25 -930.17 -931.30 -931.05   64.45   64.82 -930.68
 -930.62 -930.09 -930.35 -930.33
 9901.33 9907.23 9915.93 9917.62 9928.02 9936.83 9958.93 9958.9310030.9310030.93
10068.8010073.5610083.9610094.33
   69.59   69.66   69.75   69.75   69.83   68.70   68.81   68.81   69.19   69.19
   69.38   69.91   69.65   69.67
 -930.41 -930.34 -930.25 -930.25 -930.17 -931.30 -931.19   64.31   64.69 -930.81
 -930.62 -930.09 -930.35 -930.33
BR Coef=-1 , 0 , 0 ,, 0 ,,,0.8,0,1,0,
WSPro=,,,, 1 ,,,, 0 ,,,, 0 ,,,,-1 ,-1 ,-1 , 0 , 0 , 0 , 0 , 0
BC Design=,, 0 ,, 0 ,,,,,,

Type RM Length L Ch R = 1 ,29213.96,304.547900,304.547900,304.547900
XS GIS Cut Line= 6
785185.850131184856440.887074873785476.503184497856383.648734748
785937.797988117856274.352404982 786177.38132143856208.380182743
786356.200765848 856154.56073831786617.199276835 855978.84449853
#Sta/Elev= 30
9137.74175.570159157.25976.206959187.83572.786559208.21971.268979228.60371.28242
 9310.1468.228919381.48467.710189422.25266.303419566.03166.284279720.18468.64885
9822.95268.342599943.27166.637029946.629  66.4599957.00159.989359967.37449.05354
9977.74645.45435 9998.4944.6223710008.8644.6451510018.6147.1632110029.6157.23742
10039.9864.4650910050.3568.3022710056.2768.68772 10071.167.8109710168.2770.73854
 10237.670.8163810353.8972.5828910390.0672.3619310462.3973.4180210657.9277.71284
#Mann= 3 , 0 , 0
9137.741  0.0872       09137.741  0.0872       010657.92  0.0872       0
#XS Ineff= 2 , 0
       09870.732        10075.33       0
Bank Sta=9137.741,10657.92
Exp/Cntr=0.3,0.1

Type RM Length L Ch R = 1 ,28909.41,532.402800,532.402800,532.402800
XS GIS Cut Line= 4
785060.472505331856579.688799426 785969.51324147856543.687186107
 786367.78108874856545.937286958786973.058212548856521.186177805
#Sta/Elev= 30
8979.10175.46006 9273.8661.842079884.33860.239569934.34262.604469944.342 61.9827
9974.34345.5834510004.3442.9947210014.3442.9955510034.34 58.556210044.3461.02359
10254.3558.53407 10344.460.7070910414.4544.3190710504.5362.0524210544.5661.59741
10554.5766.0925210574.5969.03006 10584.667.12519 10594.657.5888310644.6567.68036
10654.6578.3153710664.6678.6673510674.6787.7172610684.68106.242410694.69118.5366
10724.71127.463210744.73128.775810804.78123.602710844.81133.628110892.91136.6878
#Mann= 3 , 0 , 0
8979.101  0.0622       08979.101  0.0622       010892.91  0.0622       0
#XS Ineff= 2 , 0
       09818.898        10228.02       0
Bank Sta=8979.101,10892.91
Exp/Cntr=0.3,0.1

Type RM Length L Ch R = 1 ,28377.01,249.999600,249.999600,249.999600
XS GIS Cut Line= 6
784718.496385733856790.601914569785853.349303573856995.825035855
785951.124370515 857026.71744886786015.046217173857075.846229091
786080.841404438 857099.05103372786334.647393869857086.925542453
#Sta/Elev= 30
 8689.2180.935758807.26781.177589030.542 70.43569061.06170.992189081.40867.57786
9305.21664.633199315.38962.570479427.29464.310069721.964 63.55259742.27762.45637
 9793.2153.937539895.90352.795029927.95159.923519949.74957.756999961.45648.49652
9973.16346.425519986.15740.4314210009.4939.7076410012.8840.2381110026.0755.49251
10037.3557.6112610059.5480.3539410070.0188.3991710110.6588.3935410140.77 99.4884
10250.97101.881210281.1291.28895 10304.386.3693710331.4484.3839210351.2586.85448
#Mann= 3 , 0 , 0
 8689.21   0.059       0 8689.21   0.059       010351.25   0.059       0
#XS Ineff= 2 , 0
       0                               0
Bank Sta=8689.21,10351.25
Exp/Cntr=0.3,0.1

Type RM Length L Ch R = 1 ,28127.01,1499.997400,1499.997400,1499.997400
XS GIS Cut Line= 6
784702.805404574857031.196958823785066.565216184857120.004152551
785603.149726838857298.542647555785725.223456502857324.639764994
785922.490035266857310.138513982786287.756989807 857198.07316689
#Sta/Elev= 30
 8663.8488.639148840.37387.466078922.82177.616338953.89170.094259068.093 68.6404
9078.54765.686029183.19665.935929468.94655.920849605.88454.187679626.60551.87566
9718.58254.143889828.87651.03609 9859.0855.254769951.27956.407999972.07553.79697
 9982.4842.490449992.98639.78743 10003.540.1887810035.03 55.674710066.5657.16115
10077.0859.4600510112.8774.1844510145.3373.0753410161.1776.7582510171.6875.86496
10182.1971.12144 10192.7 69.334810224.2368.5068210255.4175.8980610310.0478.85122
#Mann= 3 , 0 , 0
 8663.84  0.0691       0 8663.84  0.0691       010310.04  0.0691       0
#XS Ineff= 2 , 0
       0                               0
Bank Sta=8663.84,10310.04
Exp/Cntr=0.3,0.1

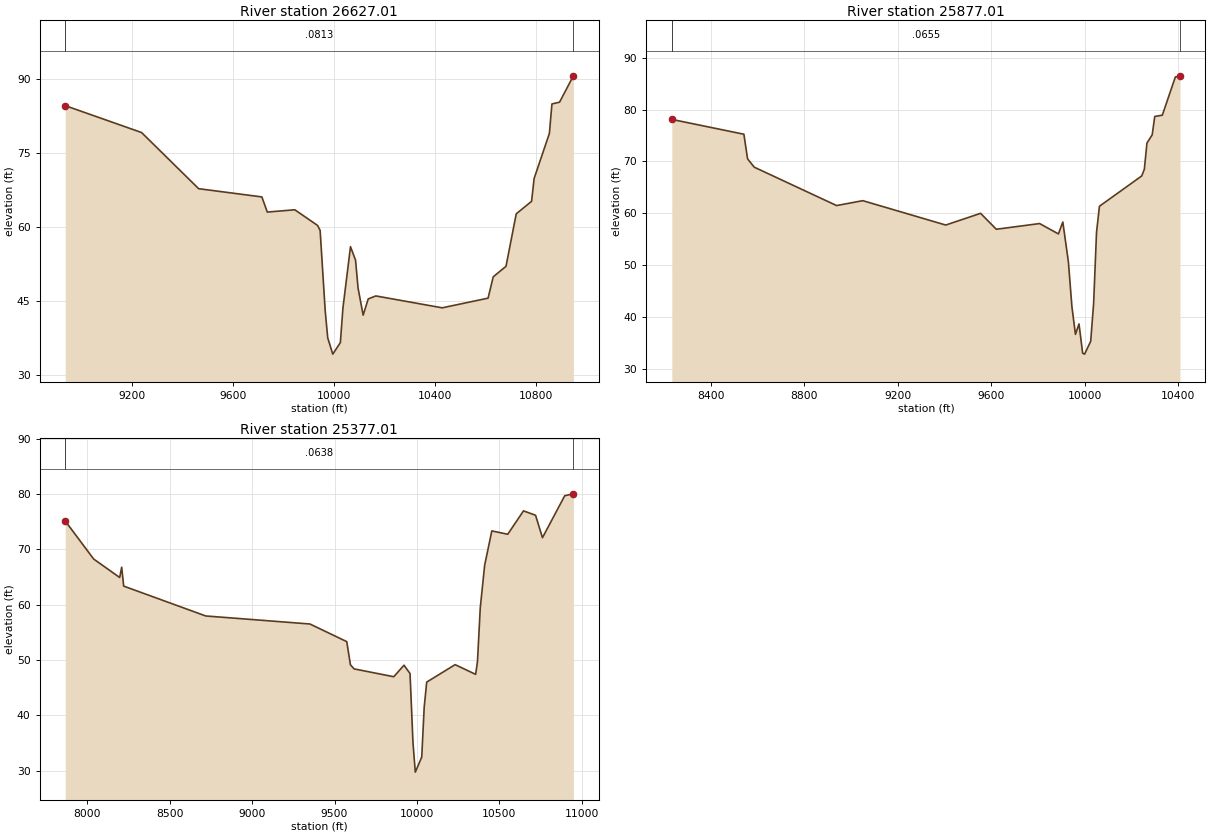
Type RM Length L Ch R = 1 ,26627.01,749.998700,749.998700,749.998700
XS GIS Cut Line= 6
784397.637533605857723.861325115785176.137204677858132.156377152
785466.181404352858132.272197366785740.031218708858097.314467922
785859.864448786858104.670760393786299.531923622858160.228460178
#Sta/Elev= 30
8936.95584.597339238.85779.140019464.69467.739999714.49766.068859736.02762.99621
9844.89163.46157  9934.960.279089944.90159.267519964.90343.001589974.90437.47436
9994.90634.1677710024.9236.5113310034.9243.4574610064.9255.9722810084.9353.24335
10094.9347.5495310114.97 42.083410135.0545.3662210165.18 45.976910427.6443.56459
10608.9445.5267910629.1849.8524210679.7851.9887610720.2662.6396310780.9365.18044
10790.99 69.818110851.3378.9579710861.3884.9370410891.5585.2984610946.1690.64595
#Mann= 3 , 0 , 0
8936.955  0.0813       08936.955  0.0813       010946.16  0.0813       0
#XS Ineff= 2 , 0
       0                10494.83       0
Bank Sta=8936.955,10946.16
Exp/Cntr=0.3,0.1

Type RM Length L Ch R = 1 ,25877.01,499.999100,499.999100,499.999100
XS GIS Cut Line= 6
784405.721265942857905.745302707785801.989055634858612.131188065
785925.208497852858485.802741796786082.207151592858367.840096861
786196.153459996858304.347068682786296.798251361858269.575351179
#Sta/Elev= 30
8232.30978.122968540.78575.26077  8556.570.509618585.08968.893758937.53561.48039
9049.604 62.42329404.71157.715029553.91459.977599621.15556.900499806.48858.00085
9887.12156.002119905.86358.302969929.73950.583389944.84241.902089959.94536.59619
9975.09538.610989990.78232.94819    999932.7773710025.0935.2494710037.6542.50506
10050.1356.3214310062.6261.3454610243.4967.20012 10254.768.4772110265.9273.55199
10288.3575.1420610299.4178.6918810331.7378.9361810387.45 86.315710407.4286.54244
#Mann= 3 , 0 , 0
8232.309  0.0655       08232.309  0.0655       010407.42  0.0655       0
#XS Ineff= 2 , 0
       0                               0
Bank Sta=8232.309,10407.42
Exp/Cntr=0.3,0.1

Type RM Length L Ch R = 1 ,25377.01,1615.488100,1615.488100,1615.488100
XS GIS Cut Line= 6
784502.726053923858111.880477265785273.871177763858642.066210672
786019.433413267859012.139495239786561.831697702858617.958715275
786872.840608567858491.292454526787165.606537622858406.973452346
#Sta/Elev= 30
7866.85875.131058039.51468.254498197.275  64.9168209.41166.774728221.54663.36004
8719.10157.965589350.98356.514789574.26553.327879596.59449.139099618.92248.40324
9859.26246.989539921.51649.068019958.05547.558429975.87535.061089989.91929.75221
   1002932.4714510043.8741.47434 10059.146.0149610231.4549.1701710355.8147.41868
10366.95 49.702410383.8859.4276910410.5667.1430210454.0573.3323910550.5472.72816
10646.1176.9544510719.2576.1592310761.0472.10423 10896.2 79.693310948.5680.03336
#Mann= 3 , 0 , 0
7866.858  0.0638       07866.858  0.0638       010948.56  0.0638       0
#XS Ineff= 2 , 0
       09721.829        10140.99       0
Bank Sta=7866.858,10948.56
Exp/Cntr=0.3,0.1