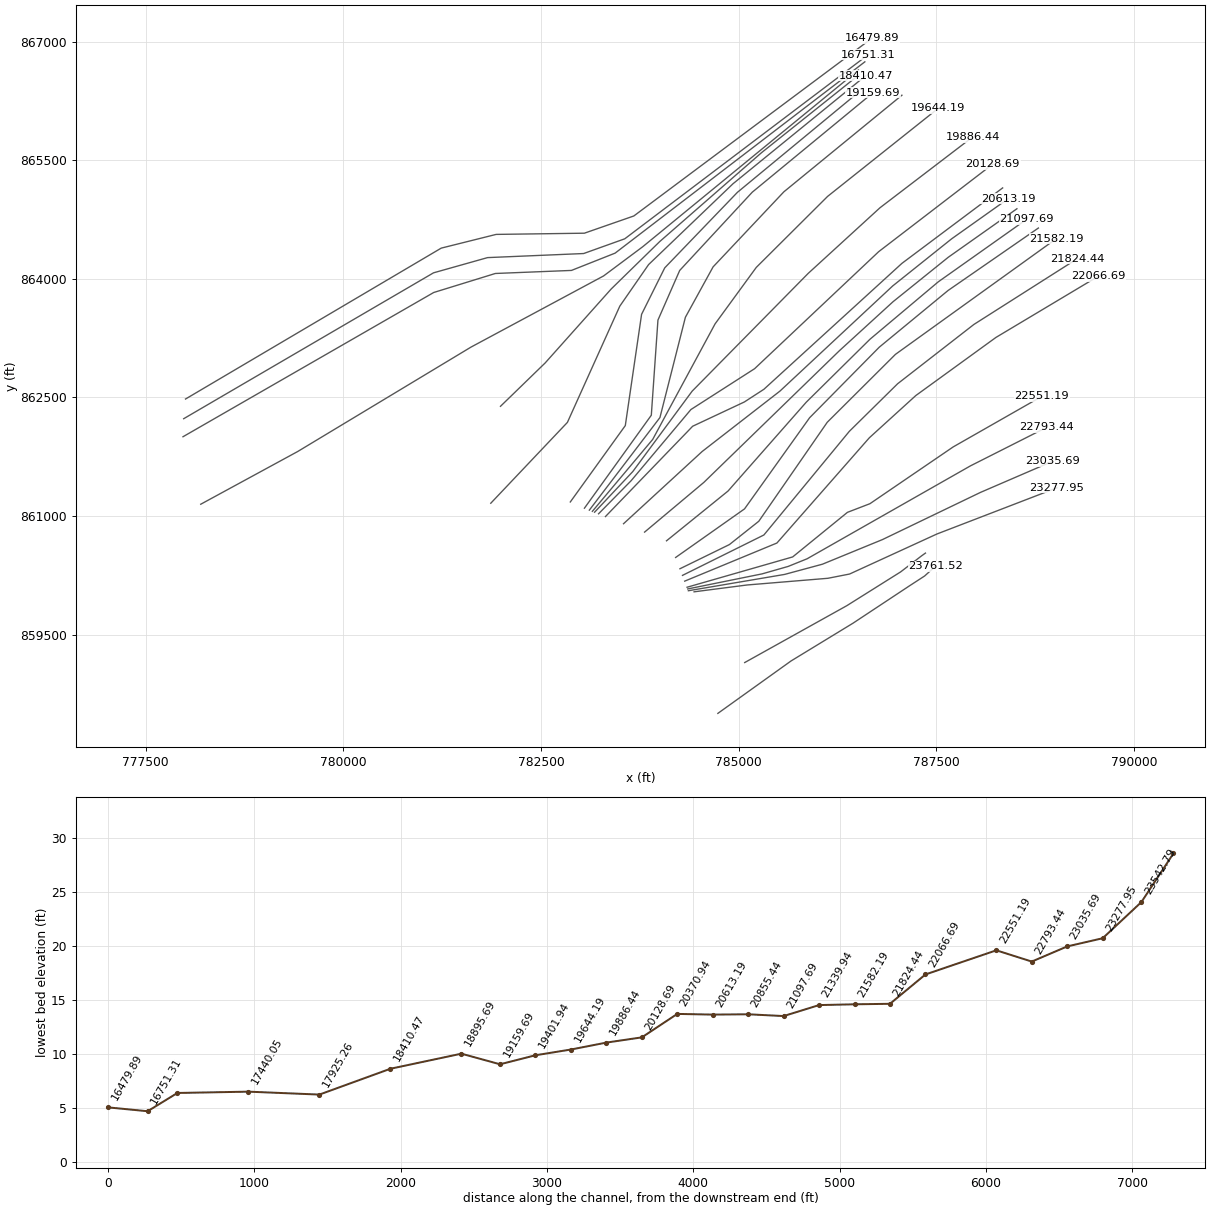
HEC-RAS study 15937_ras.prj: 15937

--- 15937_ras.g01 (geometry) --- (continued)

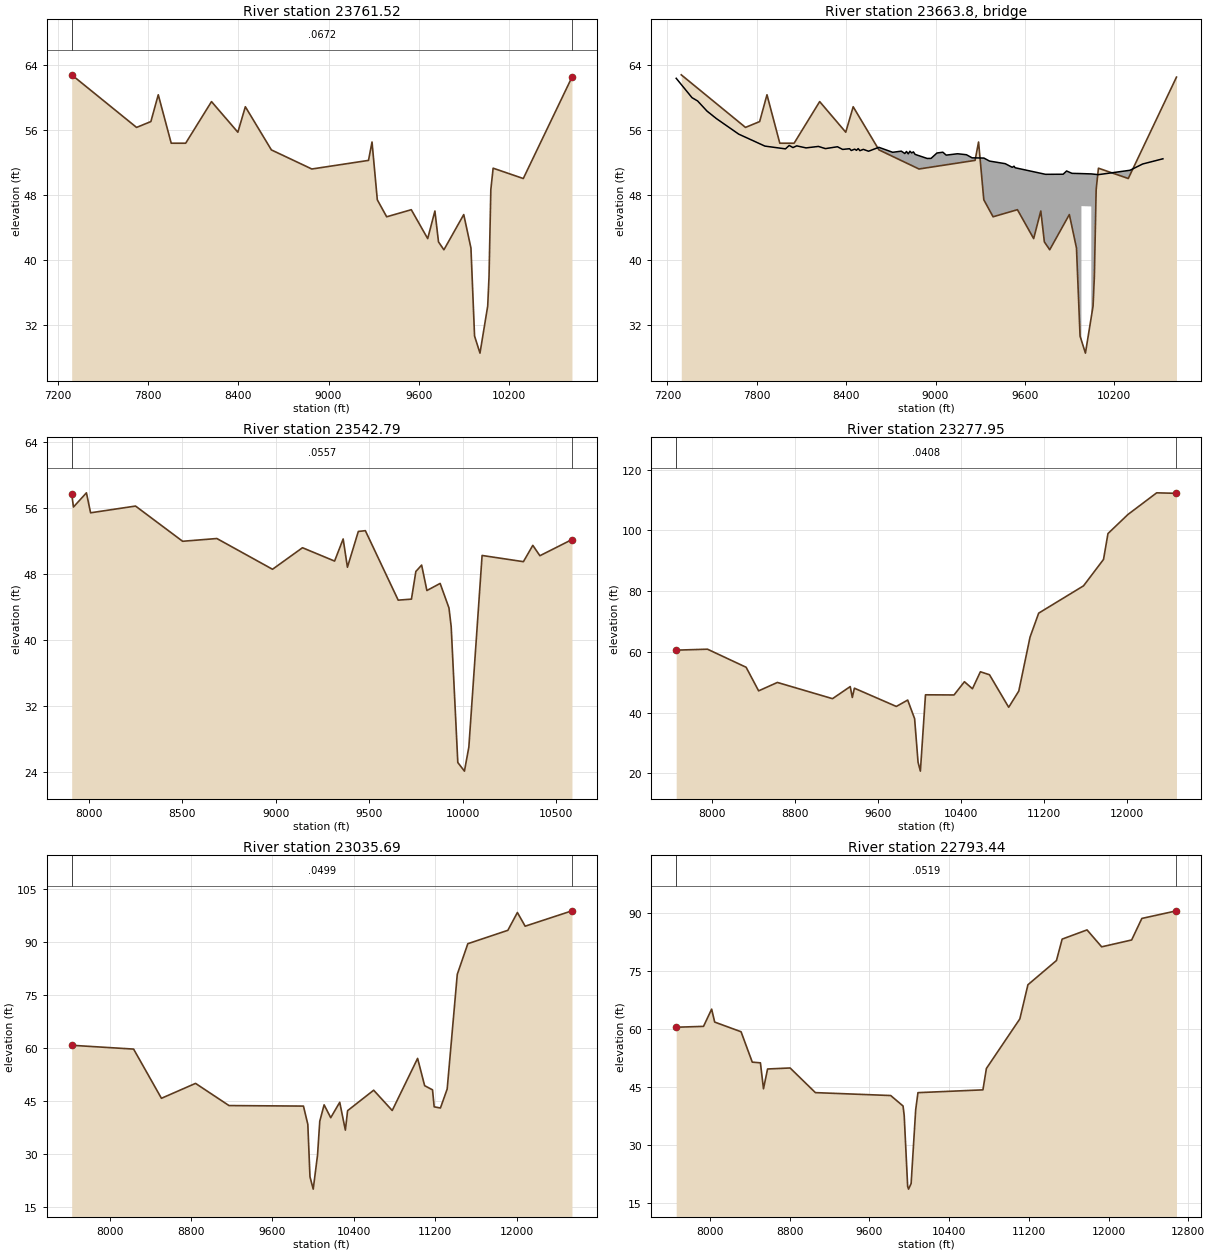
Type RM Length L Ch R = 1 ,23761.52,218.739400,218.739400,218.739400
XS GIS Cut Line= 6
784737.154291689858503.941495582785662.741644174859166.807547152
786446.376826406859644.486112416787164.874074489860119.806860387
787352.027896315860241.360373512 787488.71423009860364.513406917
#Sta/Elev= 30
7292.94862.785537724.13956.317927819.19557.035797868.395 60.33357954.49454.37606
8050.46254.373788222.21159.492238397.29255.728868447.15458.860638620.06853.55375
8889.04551.203349265.56952.261599288.99254.522569324.12647.414639386.42745.32535
9549.92146.198659658.94642.643379706.85946.037529730.81542.23582 9766.7541.26955
 9898.5145.599849946.42341.483019970.43730.6612210006.4928.5601310057.7734.34461
10066.5837.97195 10078.648.6713810093.8251.3035710294.2750.03309 10617.862.50239
#Mann= 3 , 0 , 0
7292.948  0.0672       07292.948  0.0672       0 10617.8  0.0672       0
#XS Ineff= 2 , 0
       09867.735        10125.66       0
Bank Sta=7292.948,10617.8
Exp/Cntr=0.3,0.1

Type RM Length L Ch R = 3 , 23663.8,,,
BEGIN DESCRIPTION:
END DESCRIPTION:
Bridge Culvert--1,0,-1,-1, 0
Deck Dist Width WeirC Skew NumUp NumDn MinLoCord MaxHiCord MaxSubmerge Is_Ogee
46.019700,126.700000,2.6,0, 60, 60, , , 0.95, 0, 0,0,,
 7258.78 7364.78 7402.66 7465.42 7528.17 7678.78 7854.49 7992.55 8017.65 8042.75
 8067.85 8130.61 8214.11 8260.47 8341.59 8376.27 8422.71 8434.29 8457.47 8469.06
 8480.65 8492.24 8515.41 8550.18 8619.71 8712.42 8770.36 8793.54 8805.12 8816.71
 8828.30 8839.89 8851.48 8863.07 8944.18 8969.94 9009.52 9049.10 9071.66 9148.05
 9207.42 9245.48 9324.83 9362.36 9468.14 9515.15 9526.90 9534.18 9738.46 9856.77
 9880.11 9916.09 9979.57 9979.5710045.8710045.8710093.8510305.9610390.6710526.69
   62.36   59.98   59.57   58.33   57.41   55.49   54.02   53.68   54.10   53.84
   54.05   53.80   53.98   53.71   53.94   53.61   53.70   53.48   53.65   53.50
   53.71   53.46   53.62   53.39   53.87   53.26   53.40   53.11   53.36   53.07
   53.39   53.18   53.31   53.00   52.50   52.51   53.17   53.27   52.91   53.08
   52.96   52.58   52.55   52.18   51.86   51.41   51.55   51.36   50.55   50.56
   50.96   50.67   50.64   50.64   50.60   50.60   50.51   51.05   51.82   52.46
 -937.64 -940.02 -940.43 -941.67 -942.59 -944.51 -945.98 -946.32 -945.90 -946.16
 -945.95 -946.20 -946.02 -946.29 -946.06 -946.39 -946.30 -946.52 -946.35 -946.50
 -946.29 -946.54 -946.38 -946.61 -946.13 -946.74 -946.60 -946.89 -946.64 -946.93
 -946.61 -946.82 -946.69 -947.00 -947.50 -947.49 -946.83 -946.73 -947.09 -946.92
 -947.04 -947.42 -947.45 -947.82 -948.14 -948.59 -948.45 -948.64 -949.45 -949.44
 -949.04 -949.33 -949.36   46.64   46.60 -949.40 -949.49 -948.95 -948.18 -947.54
 7258.78 7364.78 7402.66 7465.42 7528.17 7678.78 7854.49 7992.55 8017.65 8042.75
 8067.85 8130.61 8214.11 8260.47 8341.59 8376.27 8422.71 8434.29 8457.47 8469.06
 8480.65 8492.24 8515.41 8550.18 8619.71 8712.42 8770.36 8793.54 8805.12 8816.71
 8828.30 8839.89 8851.48 8863.07 8944.18 8969.94 9009.52 9049.10 9071.66 9148.05
 9207.42 9245.48 9324.83 9362.36 9468.14 9515.15 9526.90 9534.18 9738.46 9856.77
 9880.11 9916.09 9965.89 9965.8910032.1910032.1910093.8510305.9610390.6710526.69
   62.36   59.98   59.57   58.33   57.41   55.49   54.02   53.68   54.10   53.84
   54.05   53.80   53.98   53.71   53.94   53.61   53.70   53.48   53.65   53.50
   53.71   53.46   53.62   53.39   53.87   53.26   53.40   53.11   53.36   53.07
   53.39   53.18   53.31   53.00   52.50   52.51   53.17   53.27   52.91   53.08
   52.96   52.58   52.55   52.18   51.86   51.41   51.55   51.36   50.55   50.56
   50.96   50.67   50.64   50.64   50.61   50.61   50.51   51.05   51.82   52.46
 -937.64 -940.02 -940.43 -941.67 -942.59 -944.51 -945.98 -946.32 -945.90 -946.16
 -945.95 -946.20 -946.02 -946.29 -946.06 -946.39 -946.30 -946.52 -946.35 -946.50
 -946.29 -946.54 -946.38 -946.61 -946.13 -946.74 -946.60 -946.89 -946.64 -946.93
 -946.61 -946.82 -946.69 -947.00 -947.50 -947.49 -946.83 -946.73 -947.09 -946.92
 -947.04 -947.42 -947.45 -947.82 -948.14 -948.59 -948.45 -948.64 -949.45 -949.44
 -949.04 -949.33 -949.36   46.64   46.61 -949.39 -949.49 -948.95 -948.18 -947.54
BR Coef=-1 , 0 , 0 ,, 0 ,,,0.8,0,1,0,
WSPro=,,,, 1 ,,,, 0 ,,,, 0 ,,,,-1 ,-1 ,-1 , 0 , 0 , 0 , 0 , 0
BC Design=,, 0 ,, 0 ,,,,,,

Type RM Length L Ch R = 1 ,23542.79,264.840100,264.840100,264.840100
XS GIS Cut Line= 5
785076.671049803 859146.59821631786367.748999178859865.702786773
787049.108823895860293.454736277 787313.43947944860496.043924838
787362.352905124860530.982086048
#Sta/Elev= 30
7908.42557.685027917.95856.070567987.34457.790388009.53155.369268249.90756.18705
8501.731 51.91828684.87552.253298982.48448.525989142.73551.136479314.43349.52002
9360.219 52.20129383.11248.77176 9441.3653.108029478.97553.203159654.58144.78428
9725.425 44.90699749.039 48.25839779.89849.034159808.07645.951329878.91946.81039
9926.14943.835939937.95641.582859973.37825.10921 10008.824.0633810032.4126.97626
10103.2650.1993610324.1849.4473510374.5751.4252710412.3750.1672910583.9152.12711
#Mann= 3 , 0 , 0
7908.425  0.0557       07908.425  0.0557       010583.91  0.0557       0
#XS Ineff= 2 , 0
       09866.734        10115.87       0
Bank Sta=7908.425,10583.91
Exp/Cntr=0.3,0.1

Type RM Length L Ch R = 1 ,23277.95,242.250300,242.250300,242.250300
XS GIS Cut Line= 6
784436.410715133860041.140347734785107.692787528860127.616436854
786128.710425705860212.210628644786403.058742583860266.167877719
787507.489892781860772.361004934789024.345645219861356.128259838
#Sta/Elev= 30
7654.68460.57427 7956.3760.88693 8328.8954.937488449.422 47.15998630.20149.93082
9161.68944.586779332.34848.57483 9352.4444.97702 9372.5948.034039776.83942.02508
9886.41144.129049953.00738.003659986.30523.6476910008.6720.7139210057.8645.85895
10333.1945.8090110433.1850.1693610510.5447.8582510587.2753.4529910674.9752.46494
10860.0141.7489710957.4247.1036411065.6764.8562311149.0172.7636511581.4881.76655
11774.1290.4744511816.9398.98282 12009.3105.266212286.59112.407612477.35112.2433
#Mann= 3 , 0 , 0
7654.684  0.0408       07654.684  0.0408       012477.35  0.0408       0
#XS Ineff= 2 , 0
       09839.634        10154.91       0
Bank Sta=7654.684,12477.35
Exp/Cntr=0.3,0.1

Type RM Length L Ch R = 1 ,23035.69,242.250400,242.250400,242.250400
XS GIS Cut Line= 6
784364.472632945860054.822535023785580.536218286 860261.00689806
786058.979556918 860390.17540434786818.360420227860701.607867718
788058.511025757861298.493995354788969.017718464861691.415495798
#Sta/Elev= 30
7626.66660.730378235.571 59.6482 8509.1245.701378844.33949.929159173.49543.64162
9905.40843.494649948.35438.313489969.53723.44889 10001.319.95852 10043.829.59319
10065.7839.1902610108.4443.8522110173.5540.2057910262.0244.5698810317.3636.67955
 10339.542.1993710595.7747.9954410778.0142.2392211027.6557.0122611096.9449.27488
11174.4748.0993411190.4843.28516   1125242.9512111318.4648.3345311417.6180.83088
11521.3289.5140411914.9493.3146712008.78 98.359112085.0194.4816712545.31 98.8368
#Mann= 3 , 0 , 0
7626.666  0.0499       07626.666  0.0499       012545.31  0.0499       0
#XS Ineff= 2 , 0
       09729.003        10145.57       0
Bank Sta=7626.666,12545.31
Exp/Cntr=0.3,0.1

Type RM Length L Ch R = 1 ,22793.44,242.250300,242.250300,242.250300
XS GIS Cut Line= 6
784355.822982281860077.351857647785297.204269707860268.158848047
785626.596411496860362.340029389785865.263830751 860458.63710326
787931.786818266861634.088645995 788897.91552797862122.294770539
#Sta/Elev= 30
7660.37960.386317934.74960.609418016.24365.063958046.80361.717358311.65859.21421
8424.00351.366588505.84651.185978536.62744.484988577.66849.597198803.84949.85904
9057.74443.490519813.49442.73922 9937.4540.034899949.01237.553469983.69619.25417
 9992.8218.55757 10018.520.0073110064.2939.0644610087.0943.4814310739.14 44.2059
10773.9449.7291311109.7962.54538 11190.771.3582611477.1177.6193811534.2883.15246
11784.0385.5309211930.9181.1586212231.8382.9294412334.1388.49508 12681.890.46094
#Mann= 3 , 0 , 0
7660.379  0.0519       07660.379  0.0519       0 12681.8  0.0519       0
#XS Ineff= 2 , 0
       09673.099        10171.95       0
Bank Sta=7660.379,12681.8
Exp/Cntr=0.3,0.1

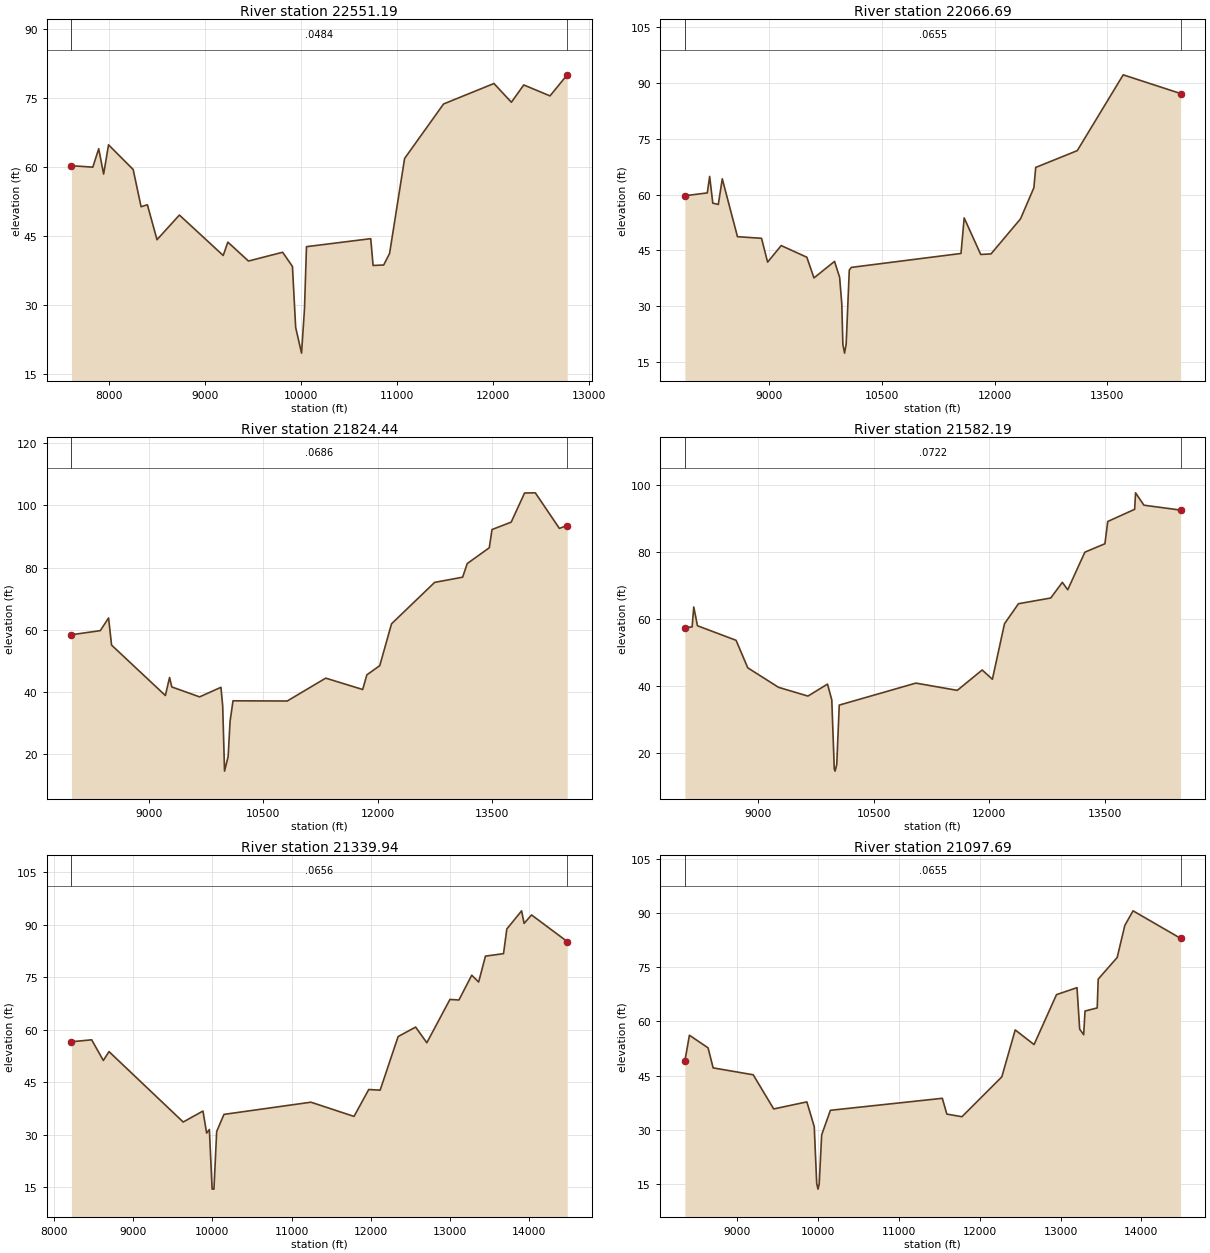
Type RM Length L Ch R = 1 ,22551.19,484.500700,484.500700,484.500700
XS GIS Cut Line= 6
784347.527622461860098.958376288785683.290994823860482.369662523
786375.707927912861046.104910985  786660.3295708861155.528081596
 787713.51496309861873.842150658788833.519661069 862512.53372395
#Sta/Elev= 30
7611.92360.295117834.51859.989927895.93163.989167947.10958.481097998.28664.84127
 8254.7659.476178337.27351.393788402.96451.822398503.09944.23139 8736.2649.58849
9192.86140.801829240.94243.706359455.90839.596829811.90941.505429914.14338.41798
9947.453 25.181210008.8219.5970710039.3629.1781510060.1342.7180810729.46 44.4568
10754.0238.6404510864.2238.7317810925.8841.2574811082.4661.8787411488.2773.71235
 12013.178.1540412194.6874.0853512323.6277.8416212596.8575.4663112776.1780.03997
#Mann= 3 , 0 , 0
7611.923  0.0484       07611.923  0.0484       012776.17  0.0484       0
#XS Ineff= 2 , 0
       09564.378        10172.62       0
Bank Sta=7611.923,12776.17
Exp/Cntr=0.3,0.1

Type RM Length L Ch R = 1 ,22066.69,242.250300,242.250300,242.250300
XS GIS Cut Line= 6
784317.885763317860176.165079251785484.158815324860658.300259799
786652.573479712861988.778930977787239.788923502862522.585977256
788253.742811441863257.982446581789548.565354139864032.034381703
#Sta/Elev= 30
7874.05259.696888172.81960.456918204.26664.893068246.19657.701598319.57257.35922
8372.38264.247938574.77448.686528895.21848.254698975.99641.841989157.073 46.2964
9498.68943.155499593.54137.594649867.43542.042669935.34137.749629963.95230.61663
9978.55719.67995   1000117.3646410022.2219.7640810063.9139.6999810090.5640.42276
11551.7244.1719711593.9653.7323711814.3543.90615   1195144.0450912344.0953.47749
12522.2661.8520412546.6667.3115413100.1471.8307513711.9892.2213214476.6687.18662
#Mann= 3 , 0 , 0
7874.052  0.0655       07874.052  0.0655       014476.66  0.0655       0
#XS Ineff= 2 , 0
       0 9690.04        10629.27       0
Bank Sta=7874.052,14476.66
Exp/Cntr=0.3,0.1

Type RM Length L Ch R = 1 ,21824.44,242.250300,242.250300,242.250300
XS GIS Cut Line= 6
784289.937325329860248.961010724785319.209052145860759.775911421
 786399.45318839862070.227590531787009.722389013862671.717679396
787974.731798202863422.075366631789283.909357429864254.502035931
#Sta/Elev= 30
7989.07558.429668366.82159.749118474.97663.824618514.39855.108959218.56438.92851
9273.74444.713619302.91841.673859666.95238.487259946.04941.55961 9969.0635.64447
9993.32314.6512210040.5819.3753610065.7630.6727110104.2337.2248610814.1537.15887
11317.8844.5013811801.7740.8535911856.5945.5599412025.4848.5123912179.5161.93917
12743.6675.2335613110.3576.9099813171.0581.2842113459.3286.3562113495.0392.20313
13746.1494.57795 13921.3103.928114062.14103.988414376.8192.5718514479.5793.48228
#Mann= 3 , 0 , 0
7989.075  0.0686       07989.075  0.0686       014479.57  0.0686       0
#XS Ineff= 2 , 0
       09709.906        10819.07       0
Bank Sta=7989.075,14479.57
Exp/Cntr=0.3,0.1

Type RM Length L Ch R = 1 ,21582.19,242.250400,242.250400,242.250400
XS GIS Cut Line= 6
784257.735784888860332.834790498784883.175311506860638.578772038
785254.579532146860933.163045391786120.616489857 862185.30692488
 786982.99398309863044.045881733789019.023247302864508.320790112
#Sta/Elev= 30
 8049.0657.421438143.07957.624638164.62763.578738212.48557.975848713.39453.63756
8865.25545.424299264.48339.606399646.03236.99605  9899.740.569719955.31135.86005
9987.62915.286459998.40214.6054110019.87 16.620210052.11 34.308811046.13 40.8654
11583.7638.7019711906.5144.7794712038.9142.0156412196.0658.5689612377.18 64.5472
12796.3566.2566112946.4570.9335113016.5568.7123213238.5179.9225513499.1782.44337
13535.5489.0802313884.65 92.718313896.6397.6332214004.8493.9431714481.1992.48145
#Mann= 3 , 0 , 0
 8049.06  0.0722       0 8049.06  0.0722       014481.19  0.0722       0
#XS Ineff= 2 , 0
       09685.892        11006.96       0
Bank Sta=8049.06,14481.19
Exp/Cntr=0.3,0.1

Type RM Length L Ch R = 1 ,21339.94,242.250300,242.250300,242.250300
XS GIS Cut Line= 6
784203.009771675860475.376964495785074.396752328861089.743122146
785897.365726501862242.276778325786778.192113966863134.621042296
787648.210630685863851.582678154788790.302323818864641.392068431
#Sta/Elev= 30
8220.16756.602428475.724  57.1618622.84351.259838694.64853.791629631.87833.68915
9881.56536.824279927.849 30.53869962.52831.547229997.20714.5416510020.2414.53345
10054.7530.9905510146.9235.86928 11245.239.3495111789.9335.2922811975.5542.96777
12119.8942.7893612346.9558.0885612568.0960.7931412709.6456.3251313001.7668.68789
13115.07  68.51913277.1275.6071513364.08 73.6524 13450.381.0493413678.5281.75543
13719.9188.7776113906.9493.9800913938.4590.3993814032.8292.80029 14483.185.21626
#Mann= 3 , 0 , 0
8220.167  0.0656       08220.167  0.0656       0 14483.1  0.0656       0
#XS Ineff= 2 , 0
       09743.121        11198.48       0
Bank Sta=8220.167,14483.1
Exp/Cntr=0.3,0.1

Type RM Length L Ch R = 1 ,21097.69,242.250300,242.250300,242.250300
XS GIS Cut Line= 6
784087.771299392860686.033986479784865.910036683861315.655335814
785855.462667435862439.443593085786660.267197251863234.631032929
787524.239051431863960.970344037788642.999275357864752.657237738
#Sta/Elev= 30
8352.92449.026098409.31556.165938639.86852.674898702.88347.11836 9198.2845.20798
9451.89635.738489861.891 37.69689953.43830.839839983.954 15.06269999.89113.51706
10014.4714.9102910044.9828.5504110153.3835.3650811537.7838.6907911593.4234.30999
11780.7333.58399 12273.344.6194112439.3257.6357612672.41  53.58312950.06  67.423
 13203.769.3517113236.7357.8601913286.2756.3112413302.78 62.870613453.4463.73709
13465.9871.7182113700.8977.7243713794.9986.5908413897.07 90.646914485.4183.01732
#Mann= 3 , 0 , 0
8352.924  0.0655       08352.924  0.0655       014485.41  0.0655       0
#XS Ineff= 2 , 0
       09757.519        11316.64       0
Bank Sta=8352.924,14485.41
Exp/Cntr=0.3,0.1

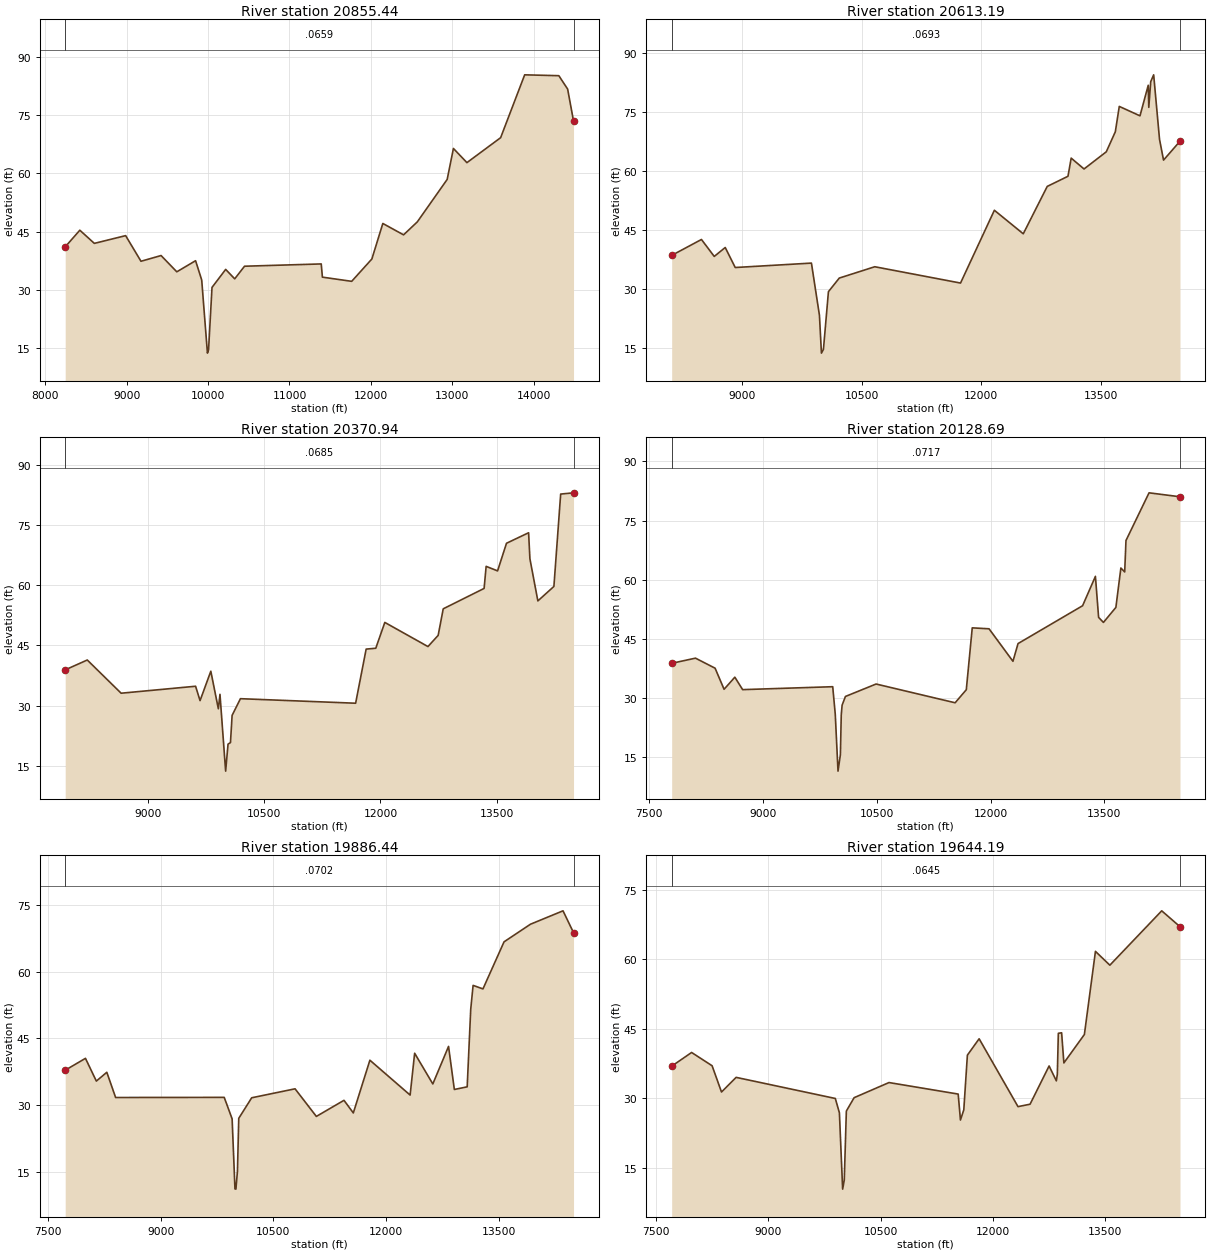
Type RM Length L Ch R = 1 ,20855.44,242.250300,242.250300,242.250300
XS GIS Cut Line= 6
783810.629242778860796.278340489 784559.86227867861424.649904013
786273.170247406863089.167712077786952.707074761 863709.80728437
787651.110003918864271.952209726788518.773319334864885.104990527
#Sta/Elev= 30
8243.68341.068758423.40545.35586 8601.7441.96655 8986.4543.959879174.93737.35429
 9421.9338.829939615.19634.636399846.00237.498539921.384 32.52099991.56613.68208
10005.6114.5627810047.7530.61546 10215.835.2562810326.89 32.826510447.4936.07688
11390.2236.6680311404.5733.2635311764.5732.1835412012.52 37.945212147.1847.09321
12402.0944.1628612570.5647.4949412937.9758.4422213014.7266.4265413180.7762.77459
13595.0169.2041613890.4385.4023514310.1385.1795814418.3981.7351514490.8373.50021
#Mann= 3 , 0 , 0
8243.683  0.0659       08243.683  0.0659       014490.83  0.0659       0
#XS Ineff= 2 , 0
       09751.004        11408.74       0
Bank Sta=8243.683,14490.83
Exp/Cntr=0.3,0.1

Type RM Length L Ch R = 1 ,20613.19,242.250400,242.250400,242.250400
XS GIS Cut Line= 6
783544.400867939860902.181340426784538.814644307 861815.68961978
785522.187340945 862579.31439884786947.828130335863908.841836974
787692.954230338864504.543728665788407.084310859 865011.42575857
#Sta/Elev= 30
8117.40538.548868490.977 42.60938651.54138.29161  8789.2 40.56438914.55335.46512
9870.52536.590399970.76523.308979995.82513.6536410020.9914.6040610083.6329.30596
10219.4732.7731110664.7735.6629111740.6431.50625 12165.150.0496912527.4544.05732
12828.3556.1331113088.3558.7096713128.5563.3354413289.91 60.572213568.8864.94748
13682.2270.0506813731.8876.5124813991.5474.1120314095.2281.90567 14101.976.26835
14126.4382.8198214163.2184.5595614236.5668.1292314287.0262.8287114493.4167.64396
#Mann= 3 , 0 , 0
8117.405  0.0693       08117.405  0.0693       014493.41  0.0693       0
#XS Ineff= 2 , 0
       0 9791.55        11486.44       0
Bank Sta=8117.405,14493.41
Exp/Cntr=0.3,0.1

Type RM Length L Ch R = 1 ,20370.94,242.250300,242.250300,242.250300
XS GIS Cut Line= 6
783315.935333461860993.062658012784418.481018752862134.957079962
785072.580396056862442.033340618785319.323272824862602.263032004
787064.515011579864194.428676099788338.531119436865148.753337607
#Sta/Elev= 30
 7926.9838.927558212.02541.378818649.421 33.11259611.46134.846649669.15131.26559
9808.26238.593539905.48829.241449926.51532.83696  9999.613.71613 10030.820.44328
10062.03  20.81210083.1527.5880910190.8531.7497111678.9830.6208311815.0544.09166
11939.4144.3118212056.1550.73532 12613.644.7238212745.3447.5106112810.7754.12089
   1333959.2006813365.2164.6920113512.86  63.56513628.1470.4411813913.7673.05901
13930.6166.5840414033.42 56.089514240.6559.6935414328.0582.6889714494.1882.99825
#Mann= 3 , 0 , 0
 7926.98  0.0685       0 7926.98  0.0685       014494.18  0.0685       0
#XS Ineff= 2 , 0
       09762.329        11515.61       0
Bank Sta=7926.98,14494.18
Exp/Cntr=0.3,0.1

Type RM Length L Ch R = 1 ,20128.69,242.250300,242.250300,242.250300
XS GIS Cut Line= 6
783228.599121004861027.804134801783639.386429489861445.149166092
784396.484779835862346.275348589785201.854311168862862.647342995
786770.761070162864342.422299907788213.570154279865449.750207722
#Sta/Elev= 30
7795.71138.856448109.478 40.16558368.08537.619098486.51232.27651 8628.4135.34165
8731.07432.189939918.44332.93077 9952.14 25.9309 9988.2411.54712 10019.615.71594
10030.8925.7215310042.1828.2556510086.1230.4605510490.19 33.611411532.0428.86005
11679.2232.1681711757.6247.8386211979.1847.5983112294.0339.3663412361.3943.85883
 13212.153.4427513381.15 60.881813423.1350.4994213486.61 49.214413650.8753.01567
 13716.762.9994813767.1362.0014513783.95 69.958614088.0982.0428714495.98  81.045
#Mann= 3 , 0 , 0
7795.711  0.0717       07795.711  0.0717       014495.98  0.0717       0
#XS Ineff= 2 , 0
       09694.569        11554.86       0
Bank Sta=7795.711,14495.98
Exp/Cntr=0.3,0.1

Type RM Length L Ch R = 1 ,19886.44,242.250400,242.250400,242.250400
XS GIS Cut Line= 6
783178.271467954861047.823974669783661.249386549861561.622000664
 784412.46707651 862579.13932465785879.477616131864067.767426237
786787.662867218864898.029739365787959.115984112865792.656886861
#Sta/Elev= 30
7727.86237.819297997.58540.488778142.51335.37196 8281.9737.356068399.188 31.6794
9845.37831.708069950.63926.878899988.54611.1124810001.1411.0644410021.67 15.1255
10038.9326.9940110211.3131.6166810788.7933.6343911072.34 27.422811440.3131.04507
 11564.628.2090811785.3340.0715212321.0332.2280912381.1841.6400512623.22 34.7284
12832.7143.17346 12909.933.4844513080.89 34.079713128.1551.5410113159.6556.90568
13290.9756.1140113571.7666.7050613923.92 70.669114357.0973.6818614497.0768.77244
#Mann= 3 , 0 , 0
7727.862  0.0702       07727.862  0.0702       014497.07  0.0702       0
#XS Ineff= 2 , 0
       09678.907        11719.64       0
Bank Sta=7727.862,14497.07
Exp/Cntr=0.3,0.1

Type RM Length L Ch R = 1 ,19644.19,242.250300,242.250300,242.250300
XS GIS Cut Line= 6
783150.244748563861058.972724929783913.297741294861968.499420926
 784701.75449723863429.083210677785223.097664744  864143.7119091
786125.663144886865042.061675191787521.822740138866153.756149605
#Sta/Elev= 30
7706.377 36.94487973.06439.908478247.03137.043398372.87631.374558568.25734.53855
9894.89229.982029949.40526.88948 9992.7710.4226610014.52 12.355410042.3927.26588
10146.0430.1531410612.8733.4178111538.0130.9327111568.2425.3354411612.9627.52754
11660.9339.3297211818.0442.8636812337.8528.2211212499.18 28.746212753.69 36.9963
12850.5933.7865312863.8635.2085312877.1244.0457212921.0644.1551812951.4937.65473
13225.4743.7831613373.4961.7229913566.3558.7437514259.7970.4728614504.1867.05217
#Mann= 3 , 0 , 0
7706.377  0.0645       07706.377  0.0645       014504.18  0.0645       0
#XS Ineff= 2 , 0
       09669.898        11795.16       0
Bank Sta=7706.377,14504.18
Exp/Cntr=0.3,0.1

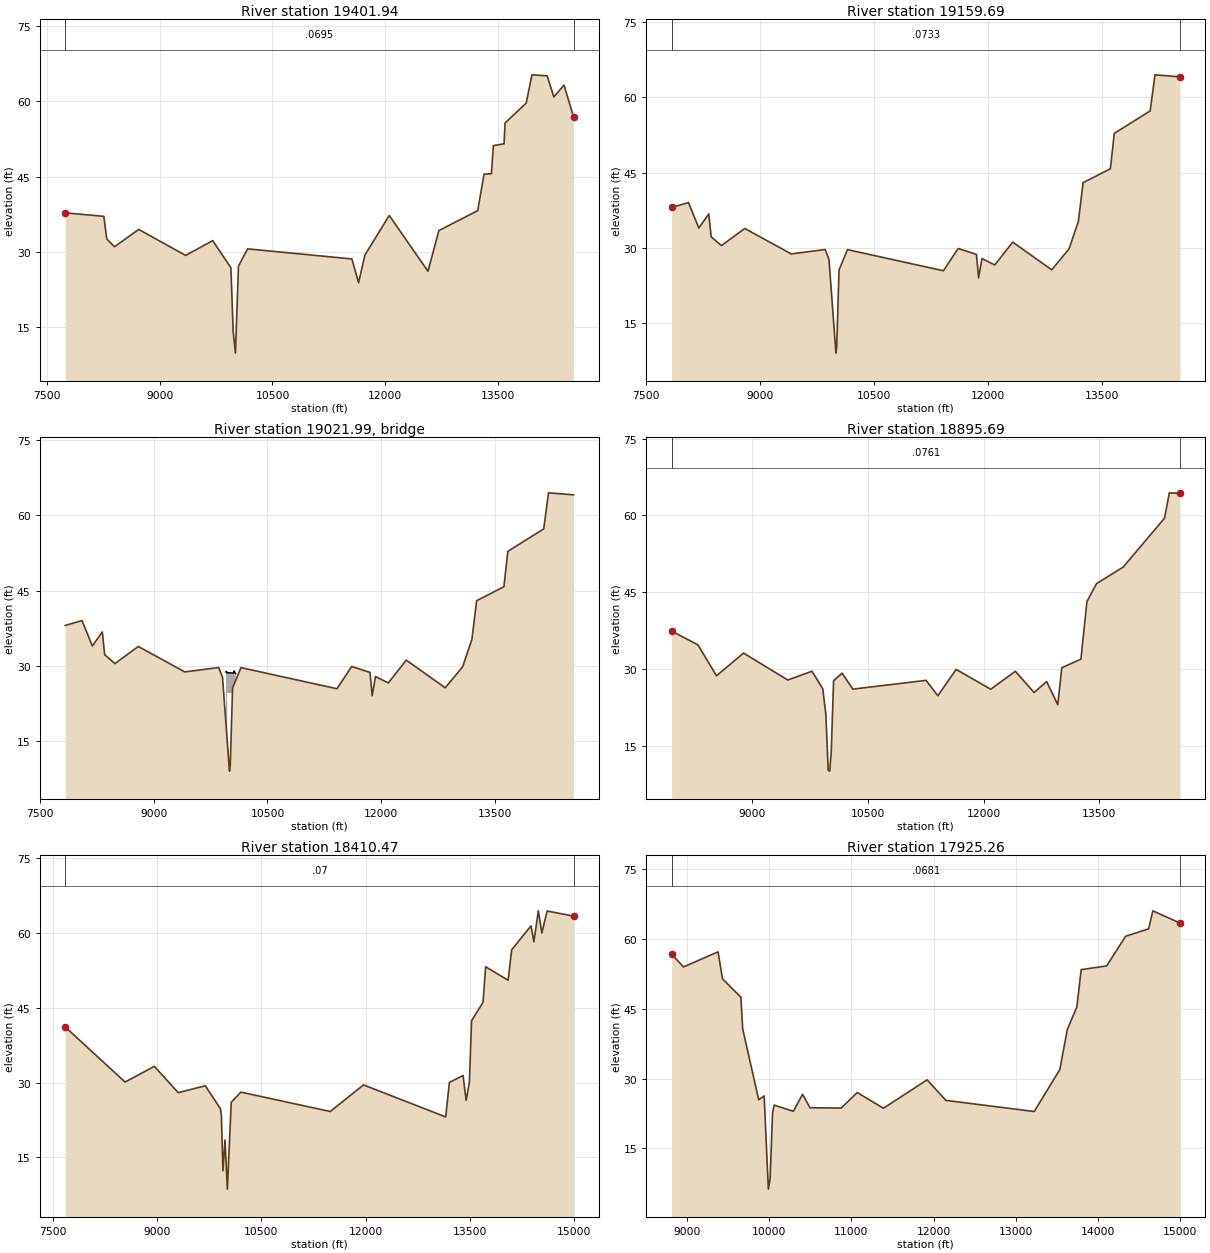
Type RM Length L Ch R = 1 ,19401.94,242.250300,242.250300,242.250300
XS GIS Cut Line= 6
783112.009771675861074.182218507784004.700736284862244.789083168
784326.676060915863513.150282577784676.815255612864150.013365179
785572.201841503865099.676386833787064.644335359866321.076639429
#Sta/Elev= 30
7743.03537.820078256.615 37.13048295.96332.621018398.73631.072488721.15334.52052
 9344.8229.344389704.755 32.28759947.13226.893299977.33614.21995 10007.69.892972
10047.97 27.220410169.1930.6507111556.5528.6438811645.4523.9023111730.0529.43128
12053.66 37.297812568.6726.1896912713.8234.2902313230.3638.2636613314.4545.52786
13412.5945.5970913438.51 51.204113580.97 51.567213593.7955.70267 13875.659.67998
13951.6165.3000714154.3265.1070714242.3160.8948414378.4563.2513714504.8456.92431
#Mann= 3 , 0 , 0
7743.035  0.0695       07743.035  0.0695       014504.84  0.0695       0
#XS Ineff= 2 , 0
       09703.449        11931.26       0
Bank Sta=7743.035,14504.84
Exp/Cntr=0.3,0.1

Type RM Length L Ch R = 1 ,19159.69,264.000000,264.000000,264.000000
XS GIS Cut Line= 6
783049.959915698861098.865034133783895.648738325862274.112800568
783979.473429561863477.259741694784254.466581225864104.863443464
785172.213111341865094.673025995786697.030974209866350.889868006
#Sta/Elev= 30
7833.79438.045978055.61639.013138191.302 33.96738323.04936.757358354.133 32.2151
8489.45530.461658797.464 33.86449410.03628.801129856.97529.670199907.27927.71557
9998.868 9.0578810009.1310.2999410039.8325.6044110150.7229.6544211415.4925.45098
11610.29  29.88211850.7928.7068611879.6624.0583611923.31  27.88512092.4126.60624
12329.2131.1478312842.7625.6390913071.5329.8035413194.4135.28573 13256.442.97416
13616.1145.74587 13667.852.7928814140.6857.25849   1420464.4392514533.7264.03994
#Mann= 3 , 0 , 0
7833.794  0.0733       07833.794  0.0733       014533.72  0.0733       0
#XS Ineff= 2 , 0
       09804.275        12115.91       0
Bank Sta=7833.794,14533.72
Exp/Cntr=0.3,0.1

Type RM Length L Ch R = 3 ,19021.99,,,
BEGIN DESCRIPTION:
END DESCRIPTION:
Bridge Culvert--1,0,-1,-1, 0
Deck Dist Width WeirC Skew NumUp NumDn MinLoCord MaxHiCord MaxSubmerge Is_Ogee
112.300000,39.400000,2.6,0, 12, 12, , , 0.95, 0, 0,0,,
 9952.94 9959.28 9964.05 9969.12 9969.1210036.1210036.1210054.9610059.3110069.31
10079.3110080.02
   28.79   28.90   28.64   28.63   28.63   28.60   28.60   28.59   28.98   28.75
   28.47   28.45
 -971.21 -971.10 -971.36 -971.37   24.63   24.60 -971.40 -971.41 -971.02 -971.25
 -971.53 -971.55
 9952.94 9959.28 9964.05 9973.32 9973.3210040.3210040.3210054.9610059.3110069.31
10079.3110080.02
   28.79   28.90   28.64   28.63   28.63   28.60   28.60   28.59   28.98   28.75
   28.47   28.45
 -971.21 -971.10 -971.36 -971.37   24.63   24.60 -971.40 -971.41 -971.02 -971.25
 -971.53 -971.55
BR Coef=-1 , 0 , 0 ,, 0 ,,,0.8,0,1,0,
WSPro=,,,, 1 ,,,, 0 ,,,, 0 ,,,,-1 ,-1 ,-1 , 0 , 0 , 0 , 0 , 0
BC Design=,, 0 ,, 0 ,,,,,,

Type RM Length L Ch R = 1 ,18895.69,485.214700,485.214700,485.214700
XS GIS Cut Line= 6
782871.186002076861177.262337744783566.783046454862143.113189965
783772.612092614863550.215423644784065.497828841864138.010614976
784984.551224917865092.949910194786504.498995334866348.695604905
#Sta/Elev= 30
7957.09737.402738297.69334.713038537.92728.669478888.62833.110759462.27327.84126
9775.37429.558059915.48326.14447 9955.5421.10694 9985.59 10.203910005.6210.03835
10025.6613.9478910055.7127.7077210165.7929.1676310305.9926.0627611254.6727.77762
 11406.6 24.7696 11644.429.9170412092.1726.0402112411.71 29.552112654.4225.41282
12817.4327.5423912960.95 23.024713013.8130.2447913261.6431.9269213339.2943.18215
13463.7646.68037 13808.749.9107614344.4259.4528214407.47 64.424214545.5564.32415
#Mann= 3 , 0 , 0
7957.097  0.0761       07957.097  0.0761       014545.55  0.0761       0
#XS Ineff= 2 , 0
       09821.623        12226.22       0
Bank Sta=7957.097,14545.55
Exp/Cntr=0.3,0.1

Type RM Length L Ch R = 1 ,18410.47,485.214600,485.214600,485.214600
XS GIS Cut Line= 6
781865.685931626861161.453295549782834.659158398862183.676930957
783497.232916711 863653.75981062783861.290378638864179.234305042
784929.151774967865201.809825085786607.158716689 866568.42930443
#Sta/Elev= 30
7676.74641.172558538.38930.127758960.40233.272969303.18327.995369692.82829.37916
9910.054 24.79829924.71823.474069947.19512.327179976.93318.5276710010.468.643754
10066.2726.0627410205.0128.1018211491.2224.2180611970.3429.5503713153.3323.13144
13206.18 30.049713403.03 31.435313447.6426.4377613494.2830.1046313525.51 42.4121
13689.9446.10594 13728.653.2548514051.6950.5426314103.0456.6631414381.2661.45651
14422.5658.2617314486.22 64.472514537.14 60.025314613.0264.4362514993.0863.41434
#Mann= 3 , 0 , 0
7676.746    0.07       07676.746    0.07       014993.08    0.07       0
#XS Ineff= 2 , 0
       0 9770.93        12405.52       0
Bank Sta=7676.746,14993.08
Exp/Cntr=0.3,0.1

Type RM Length L Ch R = 1 ,17925.26,485.214700,485.214700,485.214700
XS GIS Cut Line= 6
781988.267307705862386.957734635782553.407490663 862935.46173241
783388.060538575863870.316795529784001.277467712864469.679502627
 785289.55020303865594.498835552786517.993179015866575.626015442
#Sta/Elev= 30
8815.28656.735438959.46154.023049379.47957.263749433.05651.469889657.08247.50911
 9678.8240.707649873.86325.479559939.93526.291469991.0376.25621910013.058.667255
10041.8222.5209310061.4624.3225510295.0822.98834   1040726.6446410496.9823.74843
10877.0423.6830411072.0427.0298711390.2323.6426311921.9129.7501812149.7225.33368
13224.3922.9381913535.5931.9599113626.4740.5427113743.3245.4468213795.2653.43894
14105.0954.2404714335.52  60.60514615.2662.2046814666.6866.0778614996.9863.45196
#Mann= 3 , 0 , 0
8815.286  0.0681       08815.286  0.0681       014996.98  0.0681       0
#XS Ineff= 2 , 0
       0                12445.28       0
Bank Sta=8815.286,14996.98
Exp/Cntr=0.3,0.1

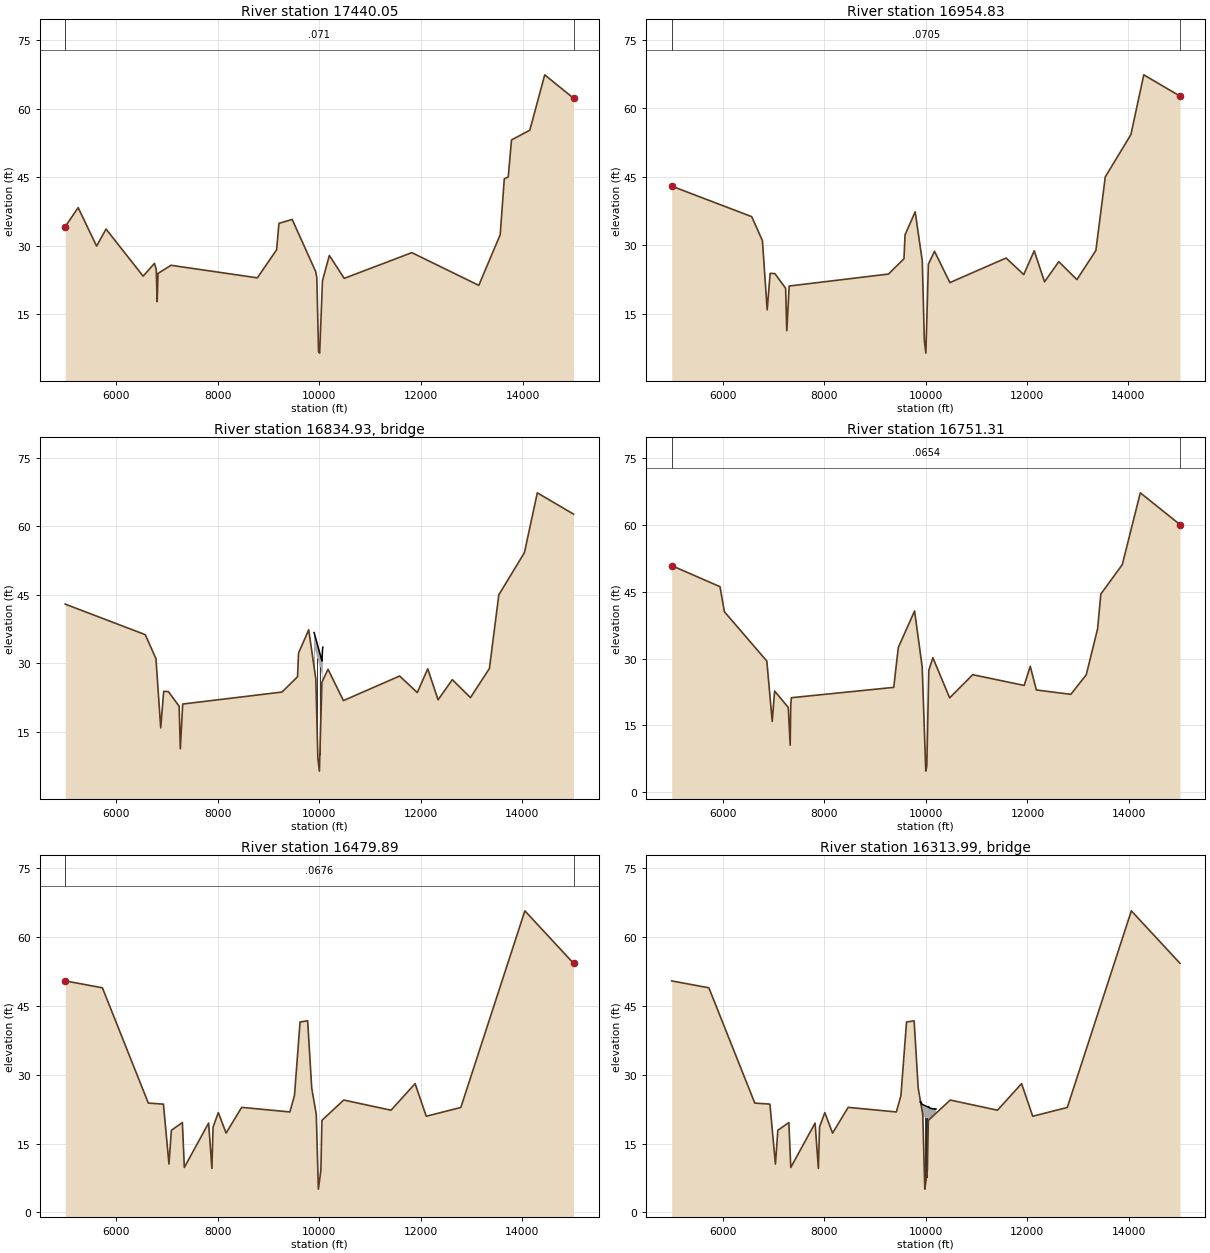
Type RM Length L Ch R = 1 ,17440.05,485.214600,485.214600,485.214600
XS GIS Cut Line= 6
778197.780440338861148.684369847779424.379858536861815.532154876
781616.499015588863136.344184869783292.162199109864035.657362988
783786.308774457864404.396171007786514.720372874866640.175596973
#Sta/Elev= 30
4998.54934.188545253.11638.368445616.36929.95035 5802.4133.67633 6532.35 23.3715
6755.00526.171436789.96524.838586808.03917.785996824.92523.963527080.01525.74966
8779.40222.999439158.54329.133769204.317 34.92039465.13435.784999927.69424.36986
9949.96123.085029983.362 6.86094 10005.66.52647910061.1522.3657410196.1727.90172
10489.0622.8872111819.7228.51506 13136.821.3570513558.3232.4353213638.6844.65526
13716.4545.0847413780.9353.1770914140.9655.3107714434.6867.4268815001.4162.31098
#Mann= 3 , 0 , 0
4998.549   0.071       04998.549   0.071       015001.41   0.071       0
#XS Ineff= 2 , 0
       09344.661        12385.18       0
Bank Sta=4998.549,15001.41
Exp/Cntr=0.3,0.1

Type RM Length L Ch R = 1 ,16954.83,203.520000,203.520000,203.520000
XS GIS Cut Line= 6
  777973.4083215862002.175673172781144.134641707863826.328513384
781923.498865694864066.748373166782885.836674988864105.310811669
783437.993266761864324.086930215 786595.90367341866743.108018994
#Sta/Elev= 30
4995.46642.950346573.72436.267216784.65831.015866878.40715.874056936.99923.86574
7030.74823.803947241.68220.602247265.11911.309167311.99321.086419270.10823.70953
9575.50227.05256 9595.6332.257049796.15737.333299936.34226.535019976.5039.202018
10006.626.40449310056.8225.8709810177.0328.6949410480.3921.83933 11588.127.21561
11936.8223.5949512142.9828.7978512346.28 22.012212627.1326.4171912984.58 22.4993
13358.2728.85658 13543.944.9777414048.8554.2176114302.7567.3042415016.81 62.6448
#Mann= 3 , 0 , 0
4995.466  0.0705       04995.466  0.0705       015016.81  0.0705       0
#XS Ineff= 2 , 0
       09664.167        12239.78       0
Bank Sta=4995.466,15016.81
Exp/Cntr=0.3,0.1

Type RM Length L Ch R = 3 ,16834.93,,,
BEGIN DESCRIPTION:
END DESCRIPTION:
Bridge Culvert--1,0,-1,-1, 0
Deck Dist Width WeirC Skew NumUp NumDn MinLoCord MaxHiCord MaxSubmerge Is_Ogee
72.760000,58.000000,2.6,0, 10, 10, , , 0.95, 0, 0,0,,
 9900.31 9905.87 9920.36 9920.3610057.7010059.1410062.7610062.7610069.1410075.86
   36.74   36.59   36.01   36.01   30.48   31.17   31.88   31.88   33.14   33.54
 -963.26 -963.41 -963.99   33.01   27.48   28.17   28.88 -968.12 -966.86 -966.46
 9900.31 9905.87 9907.54 9907.5410049.9410049.9410057.7010059.1410069.1410075.86
   36.74   36.59   36.52   36.52   30.80   30.80   30.48   31.17   33.14   33.54
 -963.26 -963.41 -963.48   33.52   27.80 -969.20 -969.52 -968.83 -966.86 -966.46
Pier Skew, UpSta & Num, DnSta & Num=  ,9967.32, 2 ,9954.51, 2 , 0 , 0 , 0 ,,
    3.00    3.00
 -965.88   34.12
    3.00    3.00
 -965.37   34.63
Pier Skew, UpSta & Num, DnSta & Num=  ,10015.79, 2 ,10002.97, 2 , 0 , 0 , 0 ,,
    3.00    3.00
 -967.83   32.17
    3.00    3.00
 -967.32   32.68
BR Coef=-1 , 0 , 0 ,, 0 ,,,0.8,0,1,0,
WSPro=,,,, 1 ,,,, 0 ,,,, 0 ,,,,-1 ,-1 ,-1 , 0 , 0 , 0 , 0 , 0
BC Design=,, 0 ,, 0 ,,,,,,

Type RM Length L Ch R = 1 ,16751.31,271.422700,271.422700,271.422700
XS GIS Cut Line= 6
777982.252624315862230.175309858781141.626694586  864074.9898215
781824.864254448864267.391298923783039.817642319864318.934250015
783559.919724104864505.171503907786640.225571667866835.317221913
#Sta/Elev= 30
4993.07150.870335945.33846.132636031.10140.512916867.264  29.4346973.42315.88521
7020.605  22.7037289.422 19.02057326.898 10.54717338.63119.573967350.36521.20349
9366.16523.523539456.77832.487339777.24340.67972 9927.2628.074559997.2684.715793
10017.275.76470810057.2727.3642610137.2830.1852810467.8921.1687310921.8526.37016
11935.2123.9595412055.1128.2527612175.3622.9413712854.3721.9578413158.8326.36974
13381.5536.6790713445.1844.4817513867.1751.0767614222.6167.2108515004.2260.07976
#Mann= 3 , 0 , 0
4993.071  0.0654       04993.071  0.0654       015004.22  0.0654       0
#XS Ineff= 2 , 0
       09674.594        12116.73       0
Bank Sta=4993.071,15004.22
Exp/Cntr=0.3,0.1

Type RM Length L Ch R = 1 ,16479.89,343.365100,343.365100,343.365100
XS GIS Cut Line= 6
778005.381619164862479.083326597781239.000464339864387.368651287
781933.564964792864560.815588271783049.026371476864576.070416166
783674.592046285 864793.96767754786683.734632001 867040.22695892
#Sta/Elev= 30
4991.13550.397435724.19548.89877 6629.1123.804576927.10823.575327035.95610.53309
 7083.3717.881927300.55619.567187338.5469.7941077817.41219.456497882.1329.578193
7905.18818.600078008.94221.72704  8161.817.27376 8469.5422.874639418.81721.86956
9509.25125.449159619.45841.454899769.48641.70651 9849.5327.054959939.65821.27659
9979.7355.07408710029.829.10425610049.8620.0423810480.4724.4652411411.8422.25197
11887.1528.0379712106.4620.9357712787.7422.8506214050.0965.6510915008.8654.22837
#Mann= 3 , 0 , 0
4991.135  0.0676       04991.135  0.0676       015008.86  0.0676       0
#XS Ineff= 2 , 0
       09676.702        11890.41       0
Bank Sta=4991.135,15008.86
Exp/Cntr=0.3,0.1

Type RM Length L Ch R = 3 ,16313.99,,,
BEGIN DESCRIPTION:
END DESCRIPTION:
Bridge Culvert--1,0,-1,-1, 0
Deck Dist Width WeirC Skew NumUp NumDn MinLoCord MaxHiCord MaxSubmerge Is_Ogee
106.682550,130.000000,2.6,0, 28, 28, , , 0.95, 0, 0,0,,
 9889.57 9895.56 9905.56 9915.57 9925.57 9926.11 9947.83 9947.8310045.8310045.83
10051.8810055.5910065.5910075.5910085.5910095.5910098.0210105.6010115.6010125.61
10135.6210145.6210155.6310165.6410175.6410185.6510195.6610200.10
   24.06   24.07   24.08   23.66   23.61   23.54   23.43   23.43   22.93   22.93
   22.90   23.03   22.80   22.79   22.66   22.64   22.63   22.61   22.67   22.60
   22.56   22.53   22.54   22.51   22.57   22.49   22.51   22.53
 -975.94 -975.93 -975.92 -976.34 -976.39 -976.46 -976.57   20.93   20.43 -977.07
 -977.10 -976.97 -977.20 -977.21 -977.34 -977.36 -977.37 -977.39 -977.33 -977.40
 -977.44 -977.47 -977.46 -977.49 -977.43 -977.51 -977.49 -977.47
 9889.57 9895.56 9905.56 9915.57 9925.57 9926.11 9950.82 9950.8210048.8210048.82
10051.8810055.5910065.5910075.5910085.5910095.5910098.0210105.6010115.6010125.61
10135.6210145.6210155.6310165.6410175.6410185.6510195.6610200.10
   24.06   24.07   24.08   23.66   23.61   23.54   23.41   23.41   22.91   22.91
   22.90   23.03   22.80   22.79   22.66   22.64   22.63   22.61   22.67   22.60
   22.56   22.53   22.54   22.51   22.57   22.49   22.51   22.53
 -975.94 -975.93 -975.92 -976.34 -976.39 -976.46 -976.59   20.91   20.41 -977.09
 -977.10 -976.97 -977.20 -977.21 -977.34 -977.36 -977.37 -977.39 -977.33 -977.40
 -977.44 -977.47 -977.46 -977.49 -977.43 -977.51 -977.49 -977.47
Pier Skew, UpSta & Num, DnSta & Num=  ,9980.00, 2 ,9982.99, 2 , 0 , 0 , 0 ,,
    3.00    3.00
 -976.74   23.26
    3.00    3.00
 -976.75   23.25
Pier Skew, UpSta & Num, DnSta & Num=  ,10013.66, 2 ,10016.65, 2 , 0 , 0 , 0 ,,
    3.00    3.00
 -976.91   23.09
    3.00    3.00
 -976.92   23.08
BR Coef=-1 , 0 , 0 ,, 0 ,,,0.8,0,1,0,
WSPro=,,,, 1 ,,,, 0 ,,,, 0 ,,,,-1 ,-1 ,-1 , 0 , 0 , 0 , 0 , 0
BC Design=,, 0 ,, 0 ,,,,,,