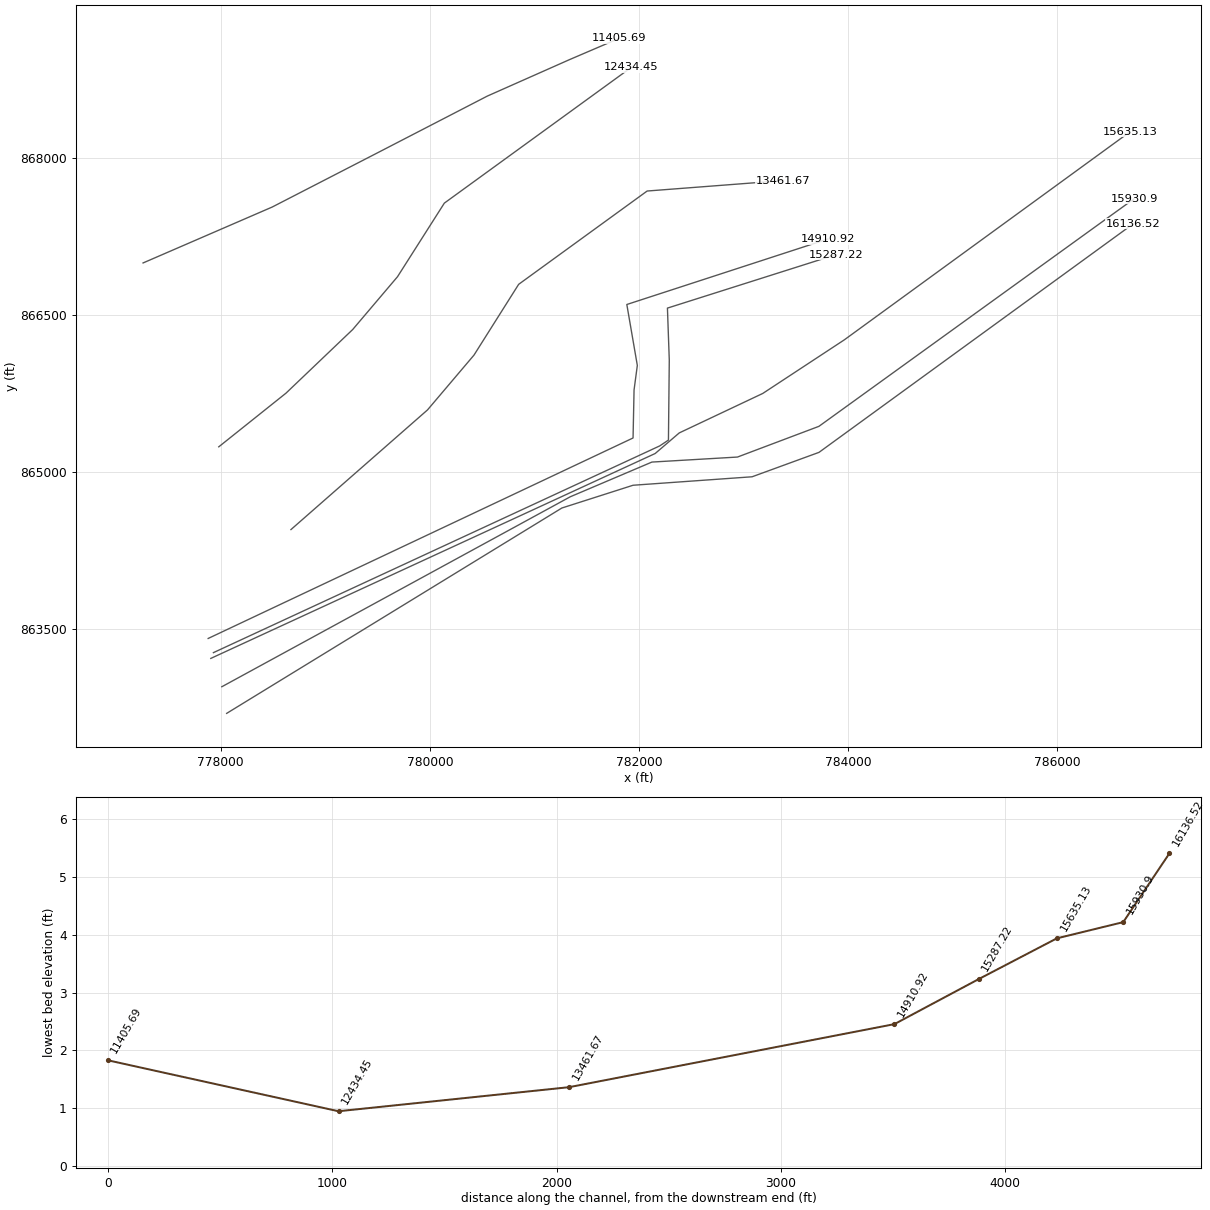
HEC-RAS study 15937_ras.prj: 15937

--- 15937_ras.g01 (geometry) --- (continued)

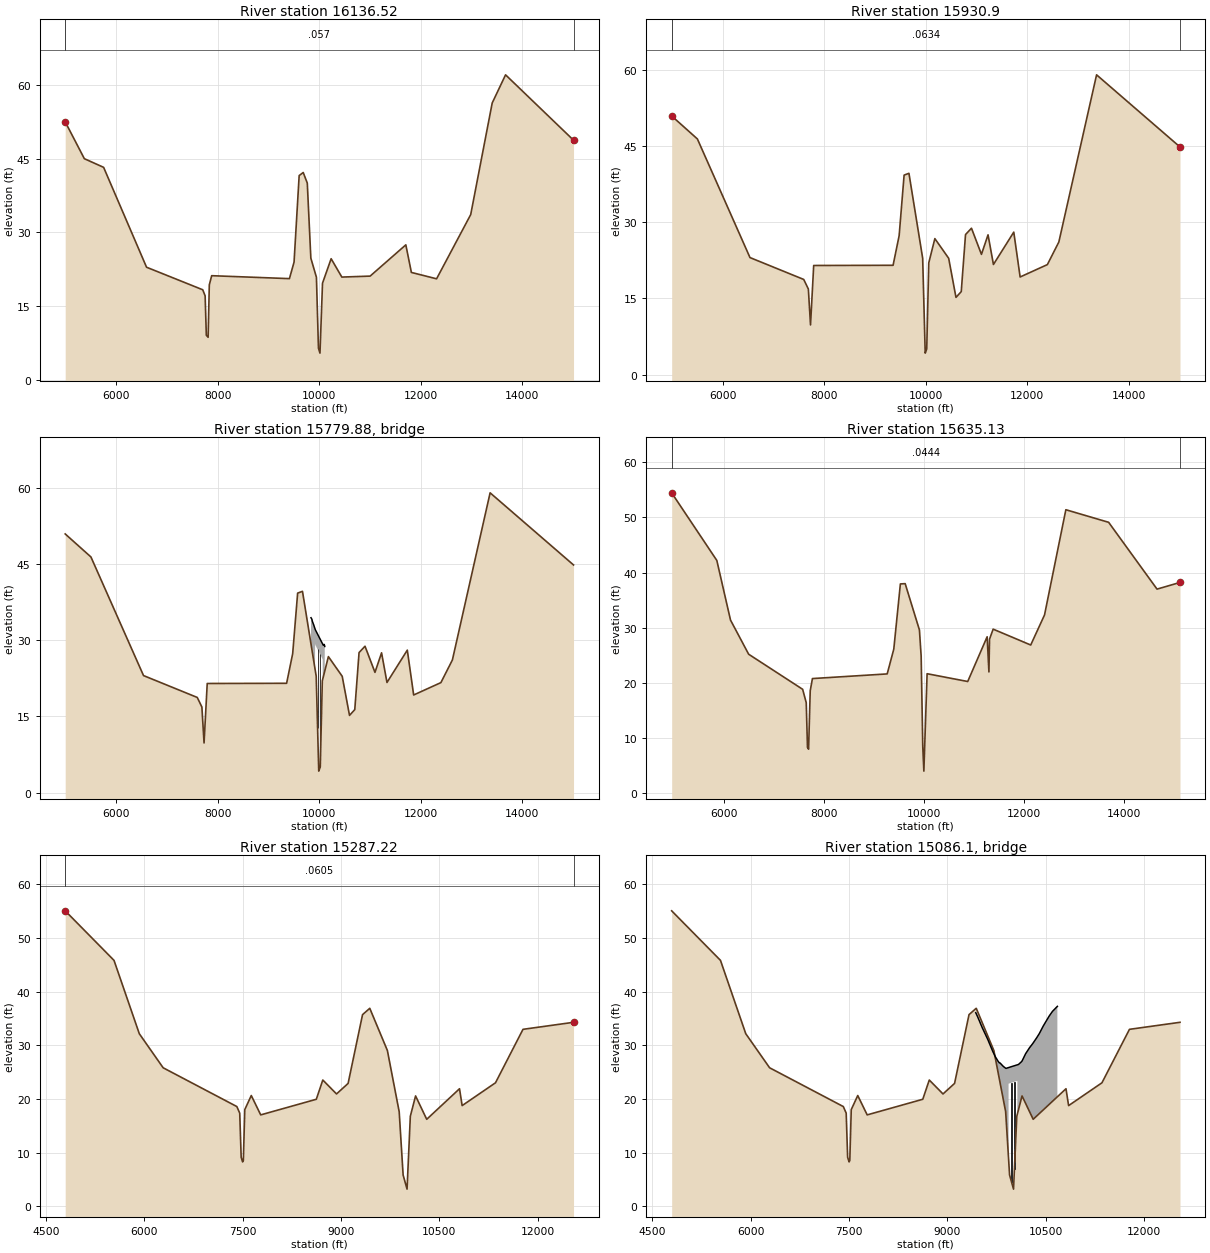
Type RM Length L Ch R = 1 ,16136.52,205.627100,205.627100,205.627100
XS GIS Cut Line= 6
778056.093609578862690.720964855781261.305627757  864654.4412977
781942.062454736864872.034565491783080.185644972864953.044861704
783719.795190451865186.461646927786723.305911837867371.083236102
#Sta/Elev= 30
4989.75752.494075366.98544.985525747.02143.222096593.43722.888967700.937 18.3017
7748.15917.065967771.6589.0344827806.9078.6287677830.40619.296367877.40421.16644
9409.67320.567979501.00623.926939601.68441.548829681.86942.173419761.92340.01467
9831.93824.741599941.96320.848969981.9866.386488   100125.40357210062.03 19.6423
10232.1224.6225310442.8620.88421 11000.821.0821911704.49 27.446611813.8121.82902
12310.81 20.533912983.3233.6043913407.1556.32542 13670.562.0560115010.24 48.7487
#Mann= 3 , 0 , 0
4989.757   0.057       04989.757   0.057       015010.24   0.057       0
#XS Ineff= 2 , 0
       09646.335        11520.11       0
Bank Sta=4989.757,15010.24
Exp/Cntr=0.3,0.1

Type RM Length L Ch R = 1 , 15930.9,295.768000,295.768000,295.768000
XS GIS Cut Line= 6
778009.753640205862945.340338156 781341.79197222864761.903404713
782122.181101292 865093.71918416782940.358045012 865141.69387342
 783719.21857217865435.378887102786731.559975028867610.499783158
#Sta/Elev= 30
4993.09850.891245500.18146.362266536.56323.019737595.75718.715627686.88416.83441
7729.5659.7645037792.21521.463479356.68421.500659476.21527.331029574.01339.24837
9669.26739.602539939.94522.888839990.0124.21616310020.045.04279310060.0821.98072
10180.1526.7523810452.57 22.876210596.3715.1840710700.26 16.323810784.4327.54386
10901.76 28.798211098.1823.6531811228.1527.4980911334.6821.6603311735.4428.02766
11860.6719.2010212397.4221.6356412623.8326.0878913367.3958.9836915011.3844.78739
#Mann= 3 , 0 , 0
4993.098  0.0634       04993.098  0.0634       015011.38  0.0634       0
#XS Ineff= 2 , 0
       09618.249        11261.45       0
Bank Sta=4993.098,15011.38
Exp/Cntr=0.3,0.1

Type RM Length L Ch R = 3 ,15779.88,,,
BEGIN DESCRIPTION:
END DESCRIPTION:
Bridge Culvert--1,0,-1,-1, 0
Deck Dist Width WeirC Skew NumUp NumDn MinLoCord MaxHiCord MaxSubmerge Is_Ogee
118.884000,58.000000,2.6,0, 20, 20, , , 0.95, 0, 0,0,,
 9837.36 9845.31 9855.31 9865.31 9875.31 9885.31 9895.31 9905.31 9915.31 9917.59
 9917.59 9918.88 9922.8810067.5910067.5910078.7410085.5210095.5310105.5510108.55
   34.40   34.27   34.09   33.67   33.41   33.14   32.87   32.54   32.26   32.19
   32.19   32.16   32.03   29.22   29.22   29.01   29.01   29.16   28.93   28.75
 -965.60 -965.73 -965.91 -966.33 -966.59 -966.86 -967.13 -967.46 -967.74 -967.81
   29.19   29.16   29.03   26.22 -970.78 -970.99 -970.99 -970.84 -971.07 -971.25
 9837.36 9845.31 9855.31 9865.31 9875.31 9885.31 9895.31 9905.31 9915.31 9918.88
 9922.88 9923.18 9923.1810073.1810073.1810078.7410085.5210095.5310105.5510108.55
   34.40   34.27   34.09   33.67   33.41   33.14   32.87   32.54   32.26   32.16
   32.03   32.03   32.03   29.12   29.12   29.01   29.01   29.16   28.93   28.75
 -965.60 -965.73 -965.91 -966.33 -966.59 -966.86 -967.13 -967.46 -967.74 -967.84
 -967.97 -967.97   29.03   26.12 -970.88 -970.99 -970.99 -970.84 -971.07 -971.25
Pier Skew, UpSta & Num, DnSta & Num=  ,9967.09, 2 ,9972.68, 2 , 0 , 0 , 0 ,,
    3.00    3.00
 -968.82   31.18
    3.00    3.00
 -968.93   31.07
Pier Skew, UpSta & Num, DnSta & Num=  ,10018.09, 2 ,10023.68, 2 , 0 , 0 , 0 ,,
    3.00    3.00
 -969.81   30.19
    3.00    3.00
 -969.92   30.08
BR Coef=-1 , 0 , 0 ,, 0 ,,,0.8,0,1,0,
WSPro=,,,, 1 ,,,, 0 ,,,, 0 ,,,,-1 ,-1 ,-1 , 0 , 0 , 0 , 0 , 0
BC Design=,, 0 ,, 0 ,,,,,,

Type RM Length L Ch R = 1 ,15635.13,347.906800,347.906800,347.906800
XS GIS Cut Line= 6
777904.372909784863216.319359139782153.484108478865175.566680744
782383.665791929865372.440527946783182.361334026865749.976703301
783962.452386975 866262.70320937786693.690583885868251.554428577
#Sta/Elev= 30
4946.52354.473085850.88542.198116125.48231.362896488.87325.162987570.38418.79407
 7642.0316.364397667.1428.2511387689.1657.9196237722.20118.531467766.24820.74392
9263.86121.588459396.00326.086039528.14537.928529624.22937.981019909.74729.56846
9944.32824.806279976.8048.3483799998.449 3.9361410063.5521.6239610877.2920.21046
11266.2628.3350411302.0221.9523611313.9427.8927311386.4529.71874 12139.326.83888
12415.7732.2977512843.0451.4038513700.0249.1187914669.5636.9870215129.5438.19944
#Mann= 3 , 0 , 0
4946.523  0.0444       04946.523  0.0444       015129.54  0.0444       0
#XS Ineff= 2 , 0
       09567.924        10748.95       0
Bank Sta=4946.523,15129.54
Exp/Cntr=0.3,0.1

Type RM Length L Ch R = 1 ,15287.22,376.304700,376.304700,376.304700
XS GIS Cut Line= 6
777929.463559985863271.518789321782196.825849712865248.229062572
782280.307698369865303.807304129782288.353409767866068.149888188
782270.636699229866565.946030363783879.823857903867076.129006714
#Sta/Elev= 30
4795.28855.030925539.77945.810465925.50632.15991 6289.1925.819827413.30718.60227
 7457.3917.373887479.4319.1538377501.4738.3016537512.4938.5729177534.53518.03396
7633.72220.653037777.54717.050328625.589 19.95668724.77623.53981 8934.1720.94712
9110.50222.908049330.91735.709839441.12436.88872 9709.7329.03559 9889.7417.64293
9949.7435.86074310009.753.23264310059.75 16.795510139.7520.5787810309.7616.22789
10810.0521.9155110850.0718.7767111358.6623.0240811778.2832.9733512549.15 34.2818
#Mann= 3 , 0 , 0
4795.288  0.0605       04795.288  0.0605       012549.15  0.0605       0
#XS Ineff= 2 , 0
       09388.802        10356.59       0
Bank Sta=4795.288,12549.15
Exp/Cntr=0.3,0.1

Type RM Length L Ch R = 3 , 15086.1,,,
BEGIN DESCRIPTION:
END DESCRIPTION:
Bridge Culvert--1,0,-1,-1, 0
Deck Dist Width WeirC Skew NumUp NumDn MinLoCord MaxHiCord MaxSubmerge Is_Ogee
111.852350,152.600000,2.6,0, 27, 27, , , 0.95, 0, 0,0,,
 9433.53 9463.47 9533.47 9613.47 9693.48 9733.48 9773.48 9793.48 9803.48 9853.49
 9893.52 9934.52 9934.5210067.5210067.5210085.5610133.7010143.7110193.7510253.79
10303.8110363.8410403.8510463.8810553.9210603.9610678.74
   36.07   35.28   33.26   31.19   28.86   27.85   27.05   26.73   26.72   26.08
   25.70   25.86   25.86   26.37   26.37   26.44   26.98   27.17   28.43   29.55
   30.34   31.42   32.20   33.61   35.45   36.32   37.25
 -963.93 -964.72 -966.74 -968.81 -971.14 -972.15 -972.95 -973.27 -973.28 -973.92
 -974.30 -974.14   22.86   23.37 -973.63 -973.56 -973.02 -972.83 -971.57 -970.45
 -969.66 -968.58 -967.80 -966.39 -964.55 -963.68 -962.75
 9433.53 9463.47 9533.47 9613.47 9693.48 9733.48 9773.48 9793.48 9803.48 9853.49
 9893.52 9938.33 9938.3310071.3310071.3310085.5610133.7010143.7110193.7510253.79
10303.8110363.8410403.8510463.8810553.9210603.9610678.74
   36.07   35.28   33.26   31.19   28.86   27.85   27.05   26.73   26.72   26.08
   25.70   25.88   25.88   26.39   26.39   26.44   26.98   27.17   28.43   29.55
   30.34   31.42   32.20   33.61   35.45   36.32   37.25
 -963.93 -964.72 -966.74 -968.81 -971.14 -972.15 -972.95 -973.27 -973.28 -973.92
 -974.30 -974.12   22.88   23.39 -973.61 -973.56 -973.02 -972.83 -971.57 -970.45
 -969.66 -968.58 -967.80 -966.39 -964.55 -963.68 -962.75
Pier Skew, UpSta & Num, DnSta & Num=  ,9978.36, 2 ,9982.16, 2 , 0 , 0 , 0 ,,
    3.00    3.00
 -973.97   26.03
    3.00    3.00
 -973.96   26.04
Pier Skew, UpSta & Num, DnSta & Num=  ,10023.69, 2 ,10027.50, 2 , 0 , 0 , 0 ,,
    3.00    3.00
 -973.80   26.20
    3.00    3.00
 -973.78   26.22
BR Coef=-1 , 0 , 0 ,, 0 ,,,0.8,0,1,0,
WSPro=,,,, 1 ,,,, 0 ,,,, 0 ,,,,-1 ,-1 ,-1 , 0 , 0 , 0 , 0 , 0
BC Design=,, 0 ,, 0 ,,,,,,

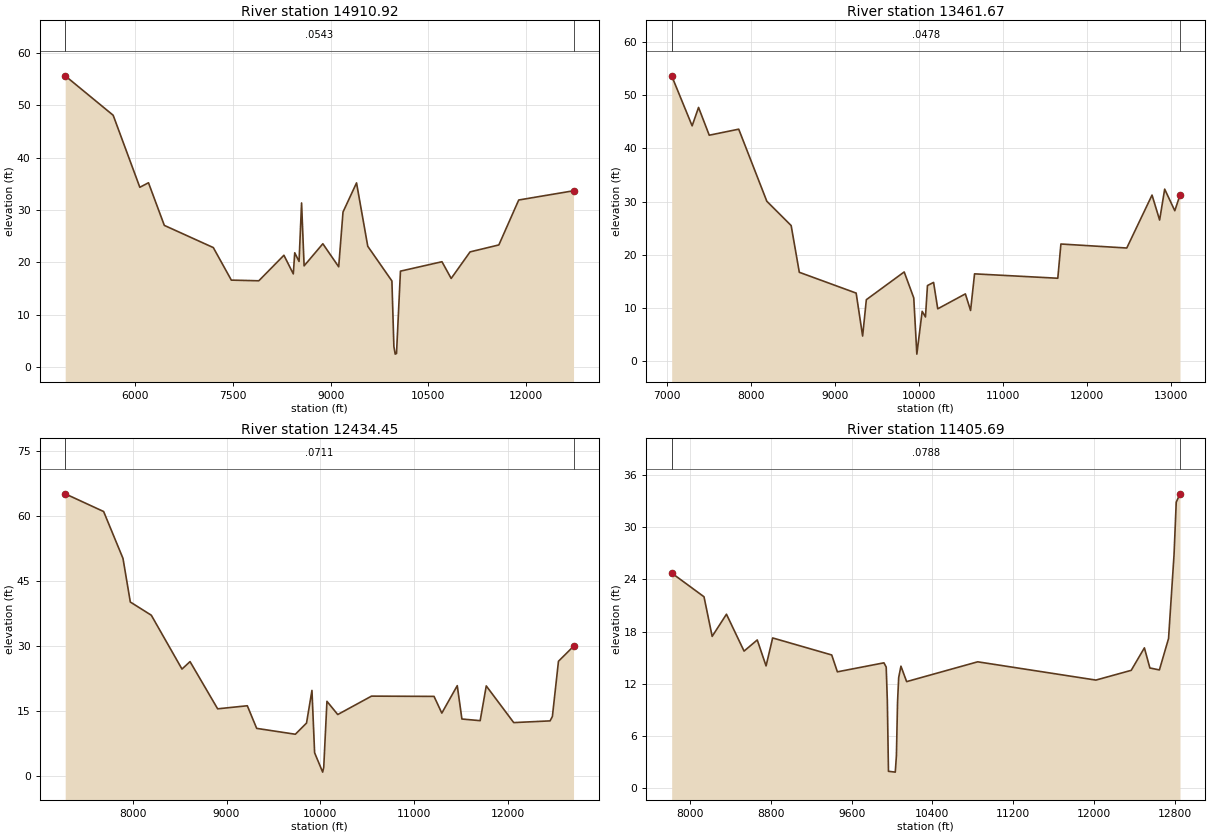
Type RM Length L Ch R = 1 ,14910.92,1449.246600,1449.246600,1449.246600
XS GIS Cut Line= 6
777879.282259703863407.008299828781941.978110254865324.079958305
781951.547854125865783.427665904781982.797854125866017.802665934
781882.375847489866600.458106056783804.719007462867226.338707656
#Sta/Elev= 30
 4927.5155.652485663.62248.115576072.74634.344186205.435 35.21196448.69827.06158
7200.60222.818697477.03716.600757898.80516.472678284.22821.354348427.97417.79132
8450.08921.828168516.43320.165428554.93131.350098593.83519.324628881.32823.55156
9124.59119.145029190.93529.617819398.52235.186829570.75223.070329941.364 16.4375
9971.6293.9097139991.8062.45349210011.98 2.5765610072.5118.31566 10709.720.11529
10850.82 16.919511140.8921.9964411582.5923.3255511887.5731.9166812728.6133.67937
#Mann= 3 , 0 , 0
 4927.51  0.0543       0 4927.51  0.0543       012728.61  0.0543       0
#XS Ineff= 2 , 0
       09456.895        10274.74       0
Bank Sta=4927.51,12728.61
Exp/Cntr=0.3,0.1

Type RM Length L Ch R = 1 ,13461.67,1027.219900,1027.219900,1027.219900
XS GIS Cut Line= 6
778670.813643873864448.198621124779976.429523468865592.291954696
780420.942699999866116.515395984780848.171424896866793.319460586
782076.728992283867685.420550093783376.763601333867785.290568739
#Sta/Elev= 30
7059.71853.594477303.26344.208617379.615 47.66187506.86842.450267857.77943.58217
8192.08830.05345 8481.6625.49357 8578.7616.722669255.21412.819099332.2914.754806
9376.38211.579659826.897  16.7879940.81711.918659977.4451.36462210040.829.399452
10080.138.34018210103.8414.2332610176.6114.8251710226.219.87016510555.04 12.6695
10616.839.55489910664.3616.4298711654.9315.6057611692.0122.0300412475.6121.27902
12776.4931.2143412866.7626.5282212926.9332.3289913047.2928.2785413109.2331.21586
#Mann= 3 , 0 , 0
7059.718  0.0478       07059.718  0.0478       013109.23  0.0478       0
#XS Ineff= 2 , 0
       09447.906        10856.03       0
Bank Sta=7059.718,13109.23
Exp/Cntr=0.3,0.1

Type RM Length L Ch R = 1 ,12434.45,1028.757800,1028.757800,1028.757800
XS GIS Cut Line= 6
 777980.62423259865239.470489323778623.675694346865752.925394937
779261.438073665866361.360724419 779689.69443813866866.050533384
 780137.51154685867569.772582695781927.097745568868869.257311776
#Sta/Elev= 30
7281.47965.114947690.72461.034837896.83450.226577975.10740.168248198.53537.12651
8525.279 24.71078611.04326.428038905.16915.545929221.19416.250699320.85911.03586
9732.841 9.683269851.77112.261939909.56719.792359937.8825.41347210023.710.949058
10035.08 2.0477710069.2117.2750910184.24 14.227410543.9318.4722411210.0118.40906
11292.7814.5579311457.1820.8845711506.6113.1960611701.2412.8137111766.1320.82605
12058.6412.3690212445.8412.7638112470.5613.7928712535.1826.50716 12695.629.96222
#Mann= 3 , 0 , 0
7281.479  0.0711       07281.479  0.0711       0 12695.6  0.0711       0
#XS Ineff= 2 , 0
       09237.035        11417.54       0
Bank Sta=7281.479,12695.6
Exp/Cntr=0.3,0.1

Type RM Length L Ch R = 1 ,11405.69,265.373700,265.373700,265.373700
XS GIS Cut Line= 6
777256.820128143866997.704852834778491.684800535867532.418981299
 779490.21173656868046.453557834780547.823106676868592.984573111
781333.646079957868941.582734227 781809.27577439869145.424031809
#Sta/Elev= 30
7817.45724.728068137.80921.997388218.67217.442958360.33719.990198534.69315.74975
 8665.4617.031998752.63814.047128818.02117.262099403.04215.304589459.27913.36454
9920.41714.399529942.91113.917719954.15910.047959965.4061.92422310032.891.830025
10044.143.74033510055.389.90538810066.6312.7028410089.1314.0133810145.36 12.2392
10849.3714.5169512020.5712.4156512370.4513.5359712501.0116.1225312555.4113.80851
12649.6513.5824912740.3617.1932212794.76 26.824712816.5232.8744912853.81 33.8367
#Mann= 3 , 0 , 0
7817.457  0.0788       07817.457  0.0788       012853.81  0.0788       0
#XS Ineff= 2 , 0
       09139.315        11629.54       0
Bank Sta=7817.457,12853.81
Exp/Cntr=0.3,0.1