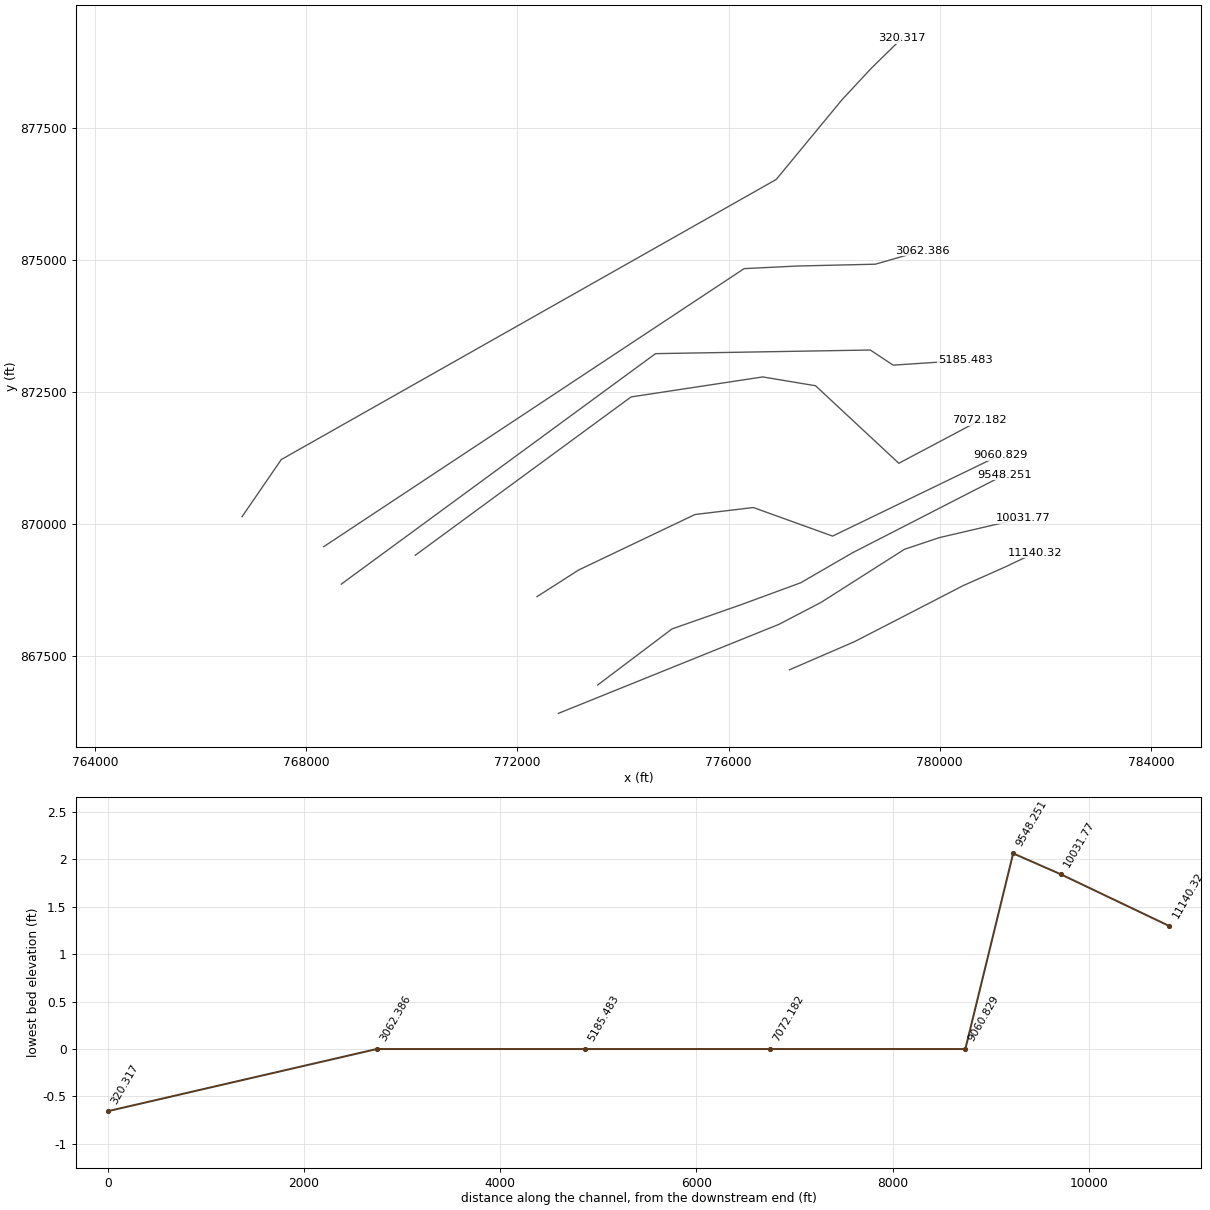
HEC-RAS study 15937_ras.prj: 15937

--- 15937_ras.g01 (geometry) --- (continued)

Type RM Length L Ch R = 3 ,11318.83,,,
BEGIN DESCRIPTION:
END DESCRIPTION:
Bridge Culvert--1,0,-1,-1, 0
Deck Dist Width WeirC Skew NumUp NumDn MinLoCord MaxHiCord MaxSubmerge Is_Ogee
111.836850,41.700000,2.6,0, 60, 60, , , 0.95, 0, 0,0,,
 7851.39 8001.01 8022.16 8043.32 8075.06 8127.95 8159.68 8191.42 8202.00 8212.57
 8233.73 8276.04 8413.56 8424.14 8498.19 8519.34 8529.92 8551.08 8561.66 8582.81
 8593.39 8603.97 8614.55 8635.70 8678.02 8688.60 8699.17 8752.07 8845.99 8883.18
 9050.15 9072.41 9150.33 9373.40 9440.76 9530.58 9586.71 9609.99 9631.62 9642.85
 9698.98 9777.57 9829.98 9901.01 9922.18 9959.18 9959.1810061.1810061.1810158.16
10214.0810270.5210281.8110293.1010304.3910446.3610496.3010575.3210631.7610870.65
   20.04   18.66   18.10   17.95   18.03   17.48   17.45   18.13   17.22   17.62
   16.73   16.07   15.34   15.07   15.18   14.89   15.12   14.56   15.03   14.57
   15.00   14.54   14.81   14.57   14.85   14.54   14.82   14.41   14.73   14.47
   14.58   14.34   14.65   14.58   14.28   14.91   14.63   14.81   14.47   14.75
   14.51   14.94   14.74   15.08   14.72   14.60   14.60   14.27   14.27   14.74
   14.52   14.67   14.41   14.63   14.26   14.63   14.17   14.25   13.90   13.53
 -979.96 -981.34 -981.90 -982.05 -981.97 -982.52 -982.55 -981.87 -982.78 -982.38
 -983.27 -983.93 -984.66 -984.93 -984.82 -985.11 -984.88 -985.44 -984.97 -985.43
 -985.00 -985.46 -985.19 -985.43 -985.15 -985.46 -985.18 -985.59 -985.27 -985.53
 -985.42 -985.66 -985.35 -985.42 -985.72 -985.09 -985.37 -985.19 -985.53 -985.25
 -985.49 -985.06 -985.26 -984.92 -985.28 -985.40   11.60   11.27 -985.73 -985.26
 -985.48 -985.33 -985.59 -985.37 -985.74 -985.37 -985.83 -985.75 -986.10 -986.47
 7851.39 8001.01 8022.16 8043.32 8075.06 8127.95 8159.68 8191.42 8202.00 8212.57
 8233.73 8276.04 8413.56 8424.14 8498.19 8519.34 8529.92 8551.08 8561.66 8582.81
 8593.39 8603.97 8614.55 8635.70 8678.02 8688.60 8699.17 8752.07 8845.99 8883.18
 9050.15 9072.41 9150.33 9373.40 9440.76 9530.58 9586.71 9609.99 9631.62 9642.85
 9698.98 9777.57 9829.98 9901.01 9922.18 9959.84 9959.8410061.8410061.8410158.16
10214.0810270.5210281.8110293.1010304.3910446.3610496.3010575.3210631.7610870.65
   20.04   18.66   18.10   17.95   18.03   17.48   17.45   18.13   17.22   17.62
   16.73   16.07   15.34   15.07   15.18   14.89   15.12   14.56   15.03   14.57
   15.00   14.54   14.81   14.57   14.85   14.54   14.82   14.41   14.73   14.47
   14.58   14.34   14.65   14.58   14.28   14.91   14.63   14.81   14.47   14.75
   14.51   14.94   14.74   15.08   14.72   14.60   14.60   14.26   14.26   14.74
   14.52   14.67   14.41   14.63   14.26   14.63   14.17   14.25   13.90   13.53
 -979.96 -981.34 -981.90 -982.05 -981.97 -982.52 -982.55 -981.87 -982.78 -982.38
 -983.27 -983.93 -984.66 -984.93 -984.82 -985.11 -984.88 -985.44 -984.97 -985.43
 -985.00 -985.46 -985.19 -985.43 -985.15 -985.46 -985.18 -985.59 -985.27 -985.53
 -985.42 -985.66 -985.35 -985.42 -985.72 -985.09 -985.37 -985.19 -985.53 -985.25
 -985.49 -985.06 -985.26 -984.92 -985.28 -985.40   11.60   11.26 -985.74 -985.26
 -985.48 -985.33 -985.59 -985.37 -985.74 -985.37 -985.83 -985.75 -986.10 -986.47
Pier Skew, UpSta & Num, DnSta & Num=  ,9992.68, 2 ,9993.34, 2 , 0 , 0 , 0 ,,
    3.00    3.00
 -985.50   14.50
    3.00    3.00
 -985.50   14.50
Pier Skew, UpSta & Num, DnSta & Num=  ,10027.68, 2 ,10028.34, 2 , 0 , 0 , 0 ,,
    3.00    3.00
 -985.61   14.39
    3.00    3.00
 -985.61   14.39
BR Coef=-1 , 0 , 0 ,, 0 ,,,0.8,0,1,0,
WSPro=,,,, 1 ,,,, 0 ,,,, 0 ,,,,-1 ,-1 ,-1 , 0 , 0 , 0 , 0 , 0
BC Design=,, 0 ,, 0 ,,,,,,

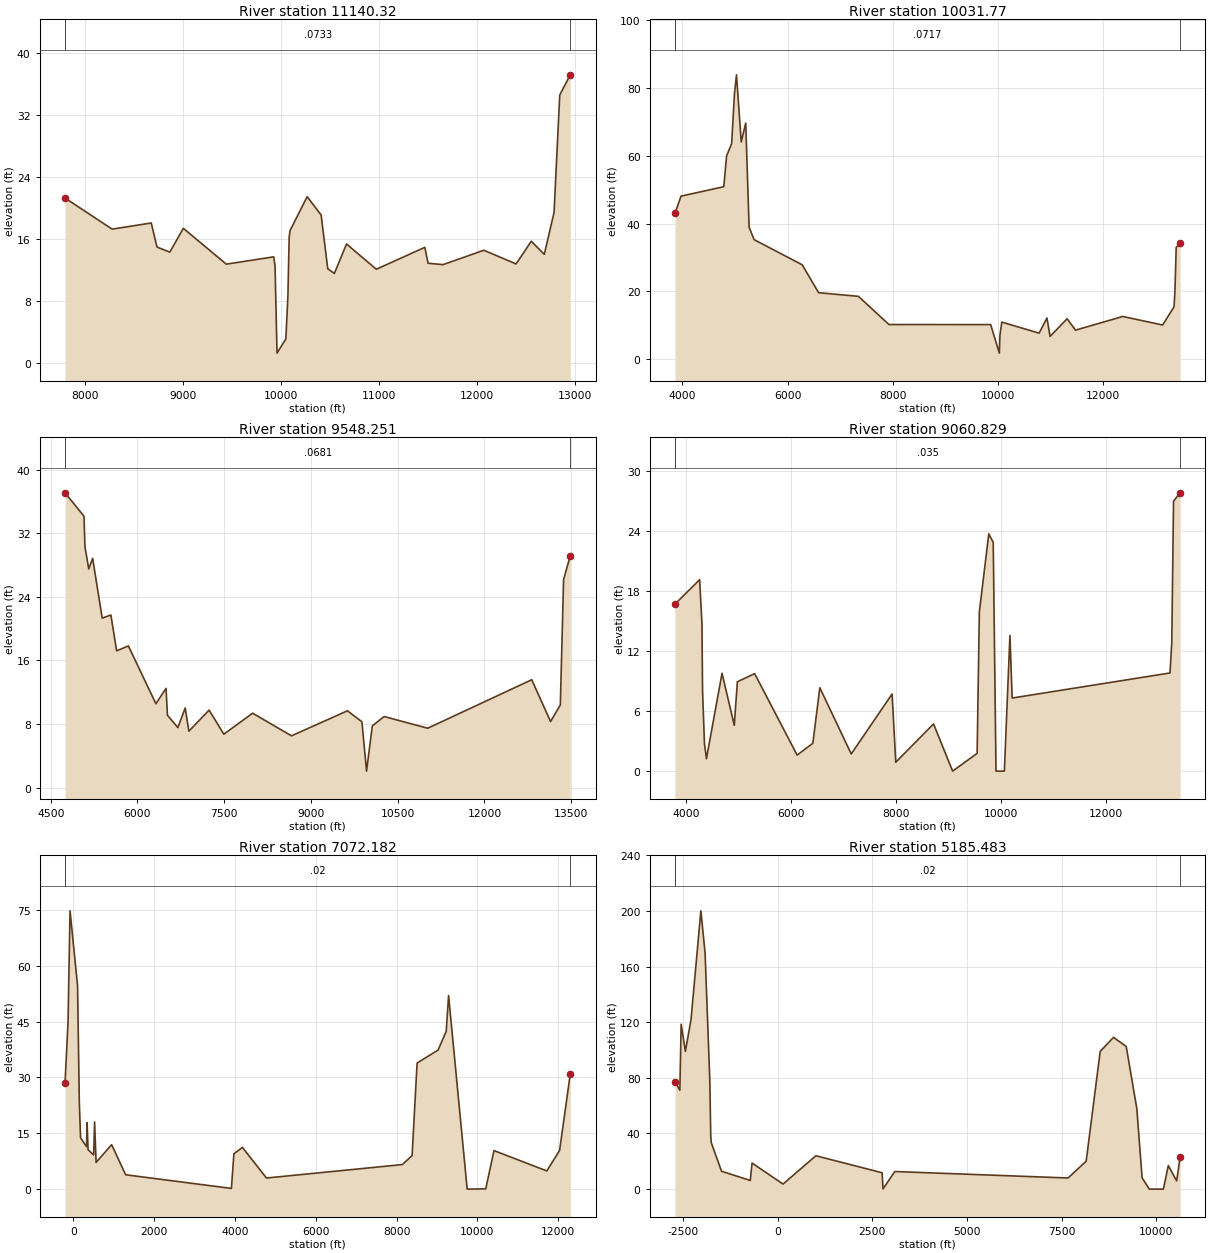
Type RM Length L Ch R = 1 ,11140.32,1108.551800,1108.551800,1108.551800
XS GIS Cut Line= 6
777154.233871251 867235.61238277778387.566108346867769.662944749
779384.573766619868282.915407881780443.471146315868830.110981166
781230.941575289869179.439968497781804.374147445869450.803022578
#Sta/Elev= 30
7797.82221.267298278.13617.265498677.09218.05669 8735.8214.955378866.58714.30333
 9004.2517.368419442.60512.753739926.23813.697269940.00912.47248 9959.981.297092
10049.963.117847 10071.18.670124 10083.7 16.218710092.9517.0867410267.7221.44815
10409.9919.0791110477.5312.1649910545.0611.5601610668.8815.35123 10972.812.10029
11467.7114.9194311500.53 12.871311653.6912.69422 12069.414.5450812398.51 12.7837
 12553.415.7027212686.1514.0208112785.7219.40103 12843.934.5424212950.9837.13689
#Mann= 3 , 0 , 0
7797.822  0.0733       07797.822  0.0733       012950.98  0.0733       0
#XS Ineff= 2 , 0
       09116.431        11623.69       0
Bank Sta=7797.822,12950.98
Exp/Cntr=0.3,0.1

Type RM Length L Ch R = 1 ,10031.77,483.515500,483.515500,483.515500
XS GIS Cut Line= 6
772776.498025001866410.170968416 776953.84218171868096.471149995
777756.719691686868515.570523169 779331.90074021869518.006592458
779990.383983687869739.077153033781578.191181354870109.105783347
#Sta/Elev= 30
3857.64643.001893973.577 48.08444786.18450.85973 4839.7259.917434936.08463.55131
 4989.6278.307515027.87383.812555118.10664.046175203.76369.600625268.00638.91411
5363.63935.25931 6277.4527.866386589.53719.644267347.14518.567927927.82510.26466
9861.74810.24483 10026.81.84432810038.56 7.1573510073.8510.9805610783.337.732237
 10932.512.1788210991.746.76437611315.7611.9752111474.97 8.6087312374.1412.64176
13132.7310.1219413348.9515.4805213365.7219.7679513390.1732.9615113465.5934.29255
#Mann= 3 , 0 , 0
3857.646  0.0717       03857.646  0.0717       013465.59  0.0717       0
#XS Ineff= 2 , 0
       09534.071        12115.17       0
Bank Sta=3857.646,13465.59
Exp/Cntr=0.3,0.1

Type RM Length L Ch R = 1 ,9548.251,487.422000,487.422000,487.422000
XS GIS Cut Line= 6
 773520.84953472866947.913177088 774929.67688939868010.418564975
776238.867554069868469.663457811777366.416581988868884.354741603
778343.168779492 869449.84285596 781237.52780351870934.740421742
#Sta/Elev= 30
4748.26337.114235075.57734.173355092.18530.329625158.61627.524235225.04628.86534
5391.12321.330085540.59121.728485640.23717.213175843.14517.832176319.09910.55356
6494.45112.491296518.4759.1065076698.6317.550739  6825.810.011996889.3847.092231
7239.0999.7509797493.4366.716135 7992.019.3597758663.2676.5084989631.5199.662171
  9881.38.2772739961.1352.06361810060.937.76450610266.048.93947211019.077.465904
12817.3413.5733213143.288.30588213311.8710.4053913368.06 26.1832 13483.329.18786
#Mann= 3 , 0 , 0
4748.263  0.0681       04748.263  0.0681       0 13483.3  0.0681       0
#XS Ineff= 2 , 0
       09502.044        12167.74       0
Bank Sta=4748.263,13483.3
Exp/Cntr=0.3,0.1

Type RM Length L Ch R = 1 ,9060.829,1988.647000,1988.647000,1988.647000
XS GIS Cut Line= 6
772371.852566302868621.757617682773161.034083277869126.833788559
 775364.56894654870177.756349027776469.441447943870309.846536294
777971.009114653869768.485385016781147.551035434871304.974775523
#Sta/Elev= 30
3792.31416.671634262.10519.118684306.57514.692564317.7588.0354314354.0662.744197
4391.9621.2407954688.7789.774658 4922.024.5779644980.5548.9226925309.7889.734481
 6118.561.5998126417.6952.7792996550.6448.3271367148.913 1.715537926.3697.700688
7996.8670.8913248716.1534.7131249079.007       09545.8071.7756479588.06615.90646
9767.66623.694019852.18422.844079905.112       010064.24       010170.32 13.5551
10212.757.29808413218.169.80196513251.7412.8335113285.3226.95541 13411.327.79046
#Mann= 3 , 0 , 0
3792.314   0.035       03792.314   0.035       0 13411.3   0.035       0
#XS Ineff= 2 , 0
       07851.062        12052.77       0
Bank Sta=3792.314,13411.3
Exp/Cntr=0.3,0.1

Type RM Length L Ch R = 1 ,7072.182,1886.699700,1886.699700,1886.699700
XS GIS Cut Line= 6
  770065.4922681869406.151553601774153.452526256872405.041318238
776647.266119972872783.848446399777648.014878854872616.776347309
779225.307452604871147.927209571780757.968889896871960.422429355
#Sta/Elev= 30
-204.77228.59648-130.96944.84643-81.359974.73185104.673754.63479148.311823.29108
179.087213.77981 327.91411.40049340.316317.85037365.1208  10.578503.34239.178181
526.349918.03323563.55667.167201 948.02611.934051295.2893.8554273912.1610.191929
3974.1729.495461 4185.0111.204674780.3182.9841828141.3736.5919418384.0558.999157
8507.80333.865049027.62937.349789229.12242.395739286.69251.998579747.248       0
 10207.80.07941510410.0210.3504411717.514.88679312034.4310.3806312298.11 30.8836
#Mann= 3 , 0 , 0
-204.772    0.02       0-204.772    0.02       012298.11    0.02       0
#XS Ineff= 2 , 0
       05951.841        11059.24       0
Bank Sta=-204.772,12298.11
Exp/Cntr=0.3,0.1

Type RM Length L Ch R = 1 ,5185.483,2123.096600,2123.096600,2123.096600
XS GIS Cut Line= 5
768662.699436337868858.512072787774616.870390207          873225
778685.304702401873293.712198377779117.539507121 873006.90682736
780487.399495453873097.992311805
#Sta/Elev= 30
-2712.3177.32666-2582.97 71.0792-2548.24118.5101-2436.6499.02571-2287.83121.8995
-2027.41 200.042 -1915.8169.4744-1791.7978.22246-1766.9938.34534-1754.5933.54053
-1481.7712.84406-722.8866.226564-675.72118.74397142.73253.6342761010.78923.99452
2759.30411.764152784.1050.1919293094.12612.653427669.9068.0065548149.97420.08077
8520.02798.98649 8872.01109.08769208.044102.52549487.05957.933059627.368   8.105
9817.788       0 10188.6       010318.8916.9210610539.385.89111110631.9822.88385
#Mann= 3 , 0 , 0
-2712.31    0.02       0-2712.31    0.02       010631.98    0.02       0
#XS Ineff= 2 , 0
       05563.997        10374.01       0
Bank Sta=-2712.31,10631.98
Exp/Cntr=0.3,0.1

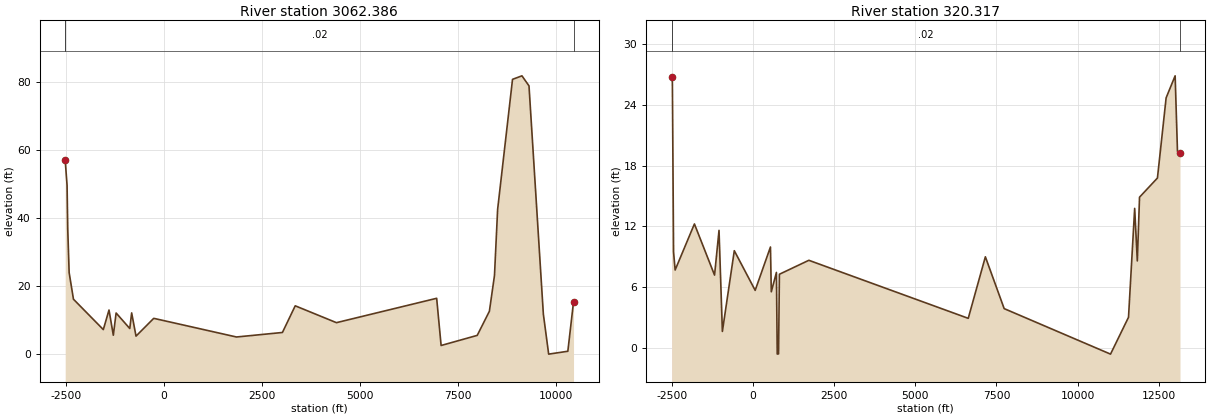
Type RM Length L Ch R = 1 ,3062.386,2742.069100,2742.069100,2742.069100
XS GIS Cut Line= 5
768331.243199203869568.775438077          776295874835.548159197
777306.717668325          874885778780.006484392874919.426123447
 779674.53096617875176.677817937
#Sta/Elev= 30
-2519.0656.93229-2471.52 49.6263-2454.6136.92531-2418.6423.95461-2308.36 16.1408
-1546.977.214966-1401.9512.96079-1291.675.561488-1220.6612.08495-872.0557.531615
-824.09812.11318-713.0685.293252-260.61310.520331849.4615.0359463021.373  6.3633
3347.68314.202094399.1279.2477836955.22516.41134 7068.782.5336997989.8785.510791
 8300.0112.597488430.046 23.12118510.06842.533888890.17280.767579130.23781.80431
9310.28678.854639676.62411.750519811.8930.00003210300.940.84280510446.1315.36724
#Mann= 3 , 0 , 0
-2519.06    0.02       0-2519.06    0.02       010446.13    0.02       0
#XS Ineff= 2 , 0
       06884.231                       0
Bank Sta=-2519.06,10446.13
Exp/Cntr=0.3,0.1

Type RM Length L Ch R = 1 , 320.317,0.000000,0.000000,0.000000
XS GIS Cut Line= 6
766784.048563487870136.886943873767526.296680908  871218.4484864
776901.654363971876523.781445381778150.190119962 878035.95971711
 778704.02301341878631.710596605779283.779863409879198.319972025
#Sta/Elev= 30
   -251226.75785-2490.0326.24087-2453.659.451242-2405.14 7.67082-1810.8512.23287
-1190.247.167876-1052.3611.59578-948.9521.591117 -581.279.58304562.175135.657029
533.26879.949181559.27015.515175717.11017.430436742.0133-0.64913782.6228-0.63335
809.03077.2513591716.6438.6333676630.4022.8871217158.3278.9794477737.5533.849373
11016.44-0.6561711570.96 2.9925511760.6713.7701811842.398.57057911910.4814.88163
12462.4716.7774612730.5424.7172313008.2126.8959913080.4119.4011113157.9819.22072
#Mann= 3 , 0 , 0
   -2512    0.02       0   -2512    0.02       013157.98    0.02       0
#XS Ineff= 2 , 0
       08933.766        10932.32       0
Bank Sta=-2512,13157.98
Exp/Cntr=0.3,0.1